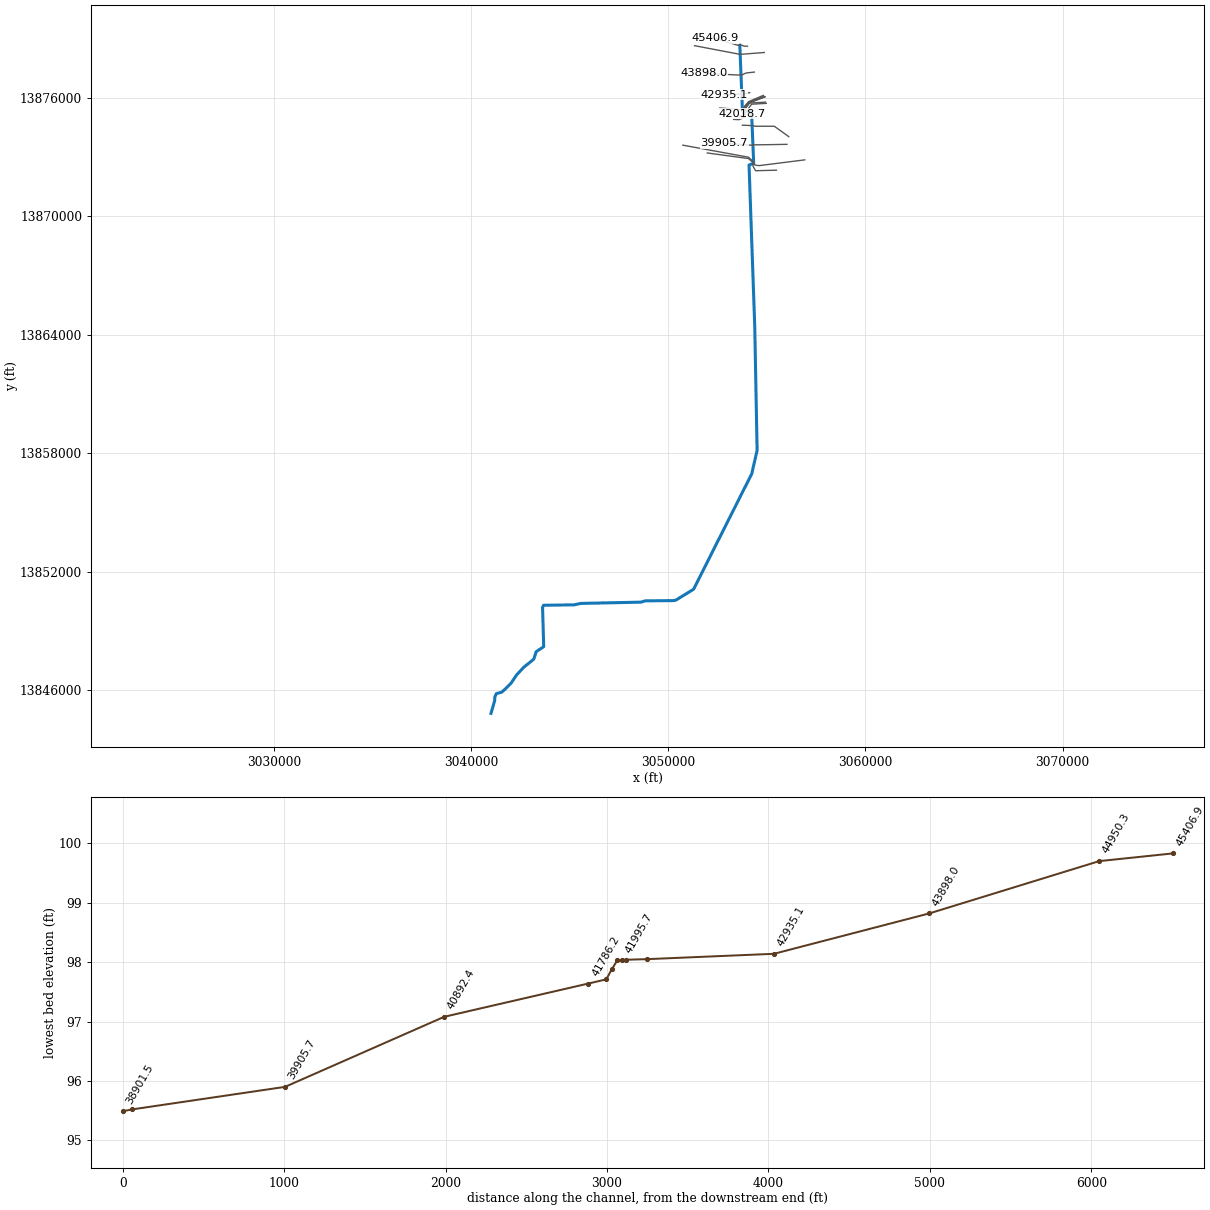
--- W167-00-00pp.prj (project) ---

Proj Title=W167-00-00
Current Plan=p01
Default Exp/Contr=.3,.1
English Units
Geom File=g01
Flow File=f03
Flow File=f01
Plan File=p03
Plan File=p01
Y Axis Title=Elevation
X Axis Title(PF)=Main Channel Distance
X Axis Title(XS)=Station
BEGIN DESCRIPTION:
Buffalo Bayou Watershed
Turkey Creek
HCFCD Unit W167-00-00
Flood Hazard Model
10, 2, 1, 0.2% Event
Filename W167-00-00.prj
Prepared by:  Watershed Concepts  Date:
Reviewed by:                      Date:
STATUS FINAL
(As-built Bridge at 27121.5)
END DESCRIPTION:
DSS Export Rating Curves= 0
DSS Export Rating Curve Sorted= 0
DSS Export Volume Flow Curves= 0
DXF OffsetX= 0
DXF OffsetY= 0
DXF ScaleX= 1
DXF ScaleY= 10

--- W167-00-00pp.p01 (plan) ---

Plan Title=FEMA Effective MP
Version=Version 3.0.1  Mar 2001
Short Identifier=Eff+LOMR MP
Geom File=g01
Flow File=f01
Subcritical Flow
K Sum by GR= 0
Std Step Tol= 0.01
Critical Tol= 0.01
Num of Std Step Trials= 20
Max Error Tol= 0.3
Flow Tol Ratio= 0.001
Split Flow NTrial= 30
Split Flow Tol= 0.02
Split Flow Ratio= 0.02
Log Output Level= 0
Friction Slope Method= 1
Unsteady Friction Slope Method= 2
Parabolic Critical Depth
Global Vel Dist= 0 , 0 , 0
Global Log Level= 0
CheckData=True
Encroach Param=-1 ,0,0, 0
BEGIN DESCRIPTION:
FEMA Effective June 2007 + LOMR 11-06-3712P
END DESCRIPTION:
Computation Interval=1HOUR
Output Interval=1HOUR
Run HTab= 0
Run UNet= 0
Run PostProcess= 0
UNET Theta= 1
UNET ZTol= 0.02
UNET ZSATol= 0.1
UNET MxIter= 20
UNET MaxInSteps= 20
UNET DtIC= 0
UNET DtMin= 0
UNET MaxCRTS= 20
UNET WFStab= 2
UNET SFStab= 1
UNET WFX= 1
UNET SFX= 1
UNET Convert EG Bridges=-1
UNET Use Existing IB Tables=-1
Instantaneous Interval=1HOUR
Write IC File= 0
IC Time=0
Write Velocity= 0
Write Detailed= 0

--- W167-00-00pp.p03 (plan) ---

Plan Title=FEMA Effective FW
Version=Version 3.0.1  Mar 2001
Short Identifier=Eff+LOMR FW
Geom File=g01
Flow File=f03
Subcritical Flow
K Sum by GR= 0
Std Step Tol= 0.01
Critical Tol= 0.01
Num of Std Step Trials= 20
Max Error Tol= 0.3
Flow Tol Ratio= 0.001
Split Flow NTrial= 30
Split Flow Tol= 0.02
Split Flow Ratio= 0.02
Log Output Level= 0
Friction Slope Method= 1
Unsteady Friction Slope Method= 2
Parabolic Critical Depth
Global Vel Dist= 0 , 0 , 0
Global Log Level= 0
CheckData=True
Encroach Param=-1 ,,, 2
Encroach River=W167-00-00
Encroach Reach=Reach - 1
Encroach Node=45406.9
       1  4976.8  5020.2
Encroach Node=44950.3
       1  4978.5  5023.9
Encroach Node=43898.0
       1  4978.5  5026.9
Encroach Node=42935.1
       1  4978.4  5024.7
Encroach Node=42147.8
       1  4977.3  5020.1
Encroach Node=42018.7
       1  4977.3  5020.1
Encroach Node=42007.2
       1  4977.3  5020.1
Encroach Node=41995.7
       1  4977.3  5020.1
Encroach Node=41964.6
       1  4977.3  5020.1
Encroach Node=41948.7
       1  4977.3  5020.1
Encroach Node=41932.8
       1  4977.3  5020.1
Encroach Node=41896.2
       1  4975.9  5022.5
Encroach Node=41786.2
       1    4981  5026.6
Encroach Node=40892.4
       1    4981  5026.6
Encroach Node=39905.7
       1  4977.9  5029.4
Encroach Node=38956.2
       1    4950 5031.94
Encroach Node=38901.5
       1    4950  5027.4
Encroach Node=38884.5
       1    4950  5027.4
Encroach Node=38867.5
       1    4950  5027.4
Encroach Node=38833.5
       1    4955 5033.73
Encroach Node=38721.3
       1    4880    5080
Encroach Node=38694.6
       1    4900    5100
Encroach Node=38667.9
       1    4900    5100
Encroach Node=38640.8
       1  4923.2    5100
Encroach Node=37921.1
       1    4950  5027.8
Encroach Node=36975.9
       1  4974.1  5038.1
Encroach Node=36861.9
       1    4850    5150
Encroach Node=36832.1
       1    4850    5150
Encroach Node=36802.3
       1    4850    5150
Encroach Node=36642.0
       1    4890    5200
Encroach Node=35978.3
       1 4965.61    5225
Encroach Node=34924.0
       1 4979.39    5200
Encroach Node=33942.7
       1  4977.7 5094.93
Encroach Node=32923.7
       1  4978.2  5017.9
Encroach Node=32136.8
       1  4973.8  5040.3
Encroach Node=32031.4
       1  4973.8  5040.3
Encroach Node=31972.1
       1  4973.8  5040.3
Encroach Node=31912.8
       1  4973.8  5040.3
Encroach Node=31770.7
       1    4983  5033.5
Encroach Node=31090.0
       1    4983  5033.5
Encroach Node=30077.7
       1  4973.4  5025.9
Encroach Node=29066.1
       1    4975  5026.6
Encroach Node=28098.6
       1  4977.9  5031.8
Encroach Node=27249.9
       1  4977.7  5022.6
Encroach Node=27138.3
       1  4977.7  5022.6
Encroach Node=27121.5
       1  4977.7  5022.6
Encroach Node=27104.7
       1  4977.7  5022.6
Encroach Node=26948.3
       1  4970.7  5032.7
Encroach Node=26421.6
       1  4970.7  5032.7
Encroach Node=25470.3
       1  4974.2  5032.6
Encroach Node=24500.9
       1  4973.1  5033.3
Encroach Node=23529.0
       1    4952  5037.6
Encroach Node=22547.9
       1  4956.1  5044.2
Encroach Node=21588.7
       1  4954.8  5031.2
Encroach Node=20620.2
       1    4951  5029.3
Encroach Node=19784.1
       1    4953  5030.7
Encroach Node=19645.6
       1    4953  5030.7
Encroach Node=19632.0
       1    4953  5030.7
Encroach Node=19618.4
       1    4953  5030.7
Encroach Node=19559.5
       1  4954.8  5025.9
Encroach Node=18549.7
       1  4959.2  5036.1
Encroach Node=17440.7
       1  4960.3  5032.9
Encroach Node=16418.9
       1  4962.7  5027.6
Encroach Node=15396.8
       1  4953.7  5035.1
Encroach Node=14478.5
       1    4959  5037.5
Encroach Node=13496.3
       1  4962.5  5036.9
Encroach Node=12568.1
       1  4958.1  5037.4
Encroach Node=11542.7
       1  4971.7  5033.8
Encroach Node=10483.1
       1  4973.2  5025.3
Encroach Node=9580.6
       1  4950.7  5059.1
Encroach Node=8663.1
       1  4940.2  5060.7
Encroach Node=7761.8
       1  4982.3  5039.5
Encroach Node=7674.3
       1  4982.3  5039.5
Encroach Node=7599.4
       1  4982.3  5039.5
Encroach Node=7524.5
       1  4982.3  5039.5
Encroach Node=7355.4
       1  4968.2    5068
Encroach Node=7062.5
       1  4968.2    5068
Encroach Node=6999.7
       1  4948.7  5048.5
Encroach Node=6766.2
       1  4948.7  5048.5
Encroach Node=6532.7
       1  4948.7  5048.5
Encroach Node=6391.8
       1    4960 5037.83
Encroach Node=5470.4
       1    4960    5040
Encroach Node=4448.2
       1  4984.8 5114.43
Encroach Node=3644.8
       1  4974.4  5019.5
Encroach Node=3526.6
       1    4900    5100
Encroach Node=3504.1
       1    4900    5100
Encroach Node=3481.6
       1    4868    5170
Encroach Node=3312.7
       1    4800    5120
Encroach Node=3096.6
       1    4830    5050
Encroach Node=2906.3
       1    4957    5033
Encroach Node=2862.1
       1    4957    5033
Encroach Node=2817.9
       1  4968.9    5033
Encroach Node=2799.3
       1  4968.9    5035
Encroach Node=2788.3
       1  4968.9    5035
Encroach Node=2777.3
       1  4968.9    5035
Encroach Node=2555.5
       1  4964.4  5044.1
Encroach Node=2414.2
       1  4964.4  5037.5
Encroach Node=2272.8
       1  4964.4  5037.5
Encroach Node=2247.8
       1  4964.4  5037.5
Encroach Node=2222.8
       1  4964.4  5037.5
Encroach Node=2000.0
       1  4964.4  5037.5
Encroach Reach=W167-00-00_0020
Encroach Node=45406.9
       1  4976.8  5020.2
Encroach Node=44950.3
       1  4978.5  5023.9
Encroach Node=43898.0
       1  4978.5  5026.9
Encroach Node=42935.1
       1  4978.4  5024.7
Encroach Node=42147.8
       1  4977.3  5020.1
Encroach Node=42018.7
       1  4977.3  5020.1
Encroach Node=42007.2
       1  4977.3  5020.1
Encroach Node=41995.7
       1  4977.3  5020.1
Encroach Node=41964.6
       1  4977.3  5020.1
Encroach Node=41948.7
       1  4977.3  5020.1
Encroach Node=41932.8
       1  4977.3  5020.1
Encroach Node=41896.2
       1  4972.9  5022.5
Encroach Node=41786.2
       1    4981  5026.6
Encroach Node=40892.4
       1    4981  5026.6
Encroach Node=39905.7
       1 4978.05 5029.25
Encroach Node=38956.2
       1    4950 5031.94
Encroach Node=38901.5
       1    4950  5027.4
Encroach Node=38884.5
       1    4950  5027.4
Encroach Node=38867.5
       1    4950  5027.4
Encroach Node=38833.5
       1    4955 5033.73
Encroach Node=38721.3
       1    4880    5080
Encroach Node=38694.6
       1    4900    5100
Encroach Node=38667.9
       1    4900    5100
Encroach Node=38640.8
       1  4923.2    5100
Encroach Node=37921.1
       1    4950  5027.8
Encroach Node=36975.9
       1  4974.1  5038.1
Encroach Node=36861.9
       1    4850    5150
Encroach Node=36832.1
       1    4850    5150
Encroach Node=36802.3
       1    4850    5150
Encroach Node=36642.0
       1    4890    5200
Encroach Node=35978.3
       1 4965.61    5225
Encroach Node=34924.0
       1 4979.39    5200
Encroach Node=33942.7
       1  4977.7 5094.93
Encroach Node=32923.7
       1  4978.2  5017.9
Encroach Node=32136.8
       1  4973.8  5040.3
Encroach Node=32031.4
       1  4973.8  5040.3
Encroach Node=31972.1
       1  4973.8  5040.3
Encroach Node=31912.8
       1  4973.8  5040.3
Encroach Node=31770.7
       1    4983  5033.5
Encroach Node=31090.0
       1    4983  5033.5
Encroach Node=30077.7
       1  4973.4  5025.9
Encroach Node=29066.1
       1    4975  5026.6
Encroach Node=28098.6
       1  4977.9  5031.8
Encroach Node=27249.9
       1  4977.7  5022.6
Encroach Node=27138.3
       1  4977.7  5022.6
Encroach Node=27121.5
       1  4977.7  5022.6
Encroach Node=27104.7
       1  4977.7  5022.6
Encroach Node=26948.3
       1  4970.7  5032.7
Encroach Node=26421.6
       1  4970.7  5032.7
Encroach Node=25470.3
       1  4974.2  5032.6
Encroach Node=24500.9
       1  4973.1  5033.3
Encroach Node=23529.0
       1    4952  5037.6
Encroach Node=22547.9
       1  4956.1  5044.2
Encroach Node=21588.7
       1  4954.8  5031.2
Encroach Node=20620.2
       1    4951  5029.3
Encroach Node=19784.1
       1    4953  5030.7
Encroach Node=19645.6
       1    4953  5030.7
Encroach Node=19632.0
       1    4953  5030.7
Encroach Node=19618.4
       1    4953  5030.7
Encroach Node=19559.5
       1  4954.8  5025.9
Encroach Node=18549.7
       1  4959.2  5036.1
Encroach Node=17440.7
       1  4960.3  5032.9
Encroach Node=16418.9
       1  4962.7  5027.6
Encroach Node=15396.8
       1  4953.7  5035.1
Encroach Node=14478.5
       1    4959  5037.5
Encroach Node=13496.3
       1  4962.5  5036.9
Encroach Node=12568.1
       1  4958.1  5037.4
Encroach Node=11542.7
       1  4971.7  5033.8
Encroach Node=10483.1
       1  4973.2  5025.3
Encroach Node=9580.6
       1  4950.7  5059.1
Encroach Node=8663.1
       1  4940.2  5060.7
Encroach Node=7761.8
       1  4982.3  5039.5
Encroach Node=7674.3
       1  4982.3  5039.5
Encroach Node=7599.4
       1  4982.3  5039.5
Encroach Node=7524.5
       1  4982.3  5039.5
Encroach Node=7355.4
       1  4968.2    5068
Encroach Node=7062.5
       1  4968.2    5068
Encroach Node=6999.7
       1  4948.7  5048.5
Encroach Node=6766.2
       1  4948.7  5048.5
Encroach Node=6532.7
       1  4948.7  5048.5
Encroach Node=6391.8
       1    4960 5037.83
Encroach Node=5470.4
       1    4960    5040
Encroach Node=4448.2
       1  4984.8 5114.43
Encroach Node=3644.8
       1  4974.4  5019.5
Encroach Node=3526.6
       1    4900    5100
Encroach Node=3504.1
       1    4900    5100
Encroach Node=3481.6
       1    4868    5170
Encroach Node=3312.7
       1    4800    5120
Encroach Node=3096.6
       1    4830    5050
Encroach Node=2906.3
       1    4957    5033
Encroach Node=2862.1
       1    4957    5033
Encroach Node=2817.9
       1  4968.9    5033
Encroach Node=2799.3
       1  4968.9    5035
Encroach Node=2788.3
       1  4968.9    5035
Encroach Node=2777.3
       1  4968.9    5035
Encroach Node=2555.5
       1  4964.4  5044.1
Encroach Node=2414.2
       1  4964.4  5037.5
Encroach Node=2272.8
       1  4964.4  5037.5
Encroach Node=2247.8
       1  4964.4  5037.5
Encroach Node=2222.8
       1  4964.4  5037.5
Encroach Node=2000.0
       1  4964.4  5037.5
BEGIN DESCRIPTION:
FEMA Effective June 2007 + LOMR 11-06-3712P
END DESCRIPTION:
Computation Interval=1HOUR
Output Interval=1HOUR
Run HTab= 0
Run UNet= 0
Run PostProcess= 0
UNET Theta= 1
UNET ZTol= 0.02
UNET ZSATol= 0.1
UNET MxIter= 20
UNET MaxInSteps= 20
UNET DtIC= 0
UNET DtMin= 0
UNET MaxCRTS= 20
UNET WFStab= 2
UNET SFStab= 1
UNET WFX= 1
UNET SFX= 1
UNET Convert EG Bridges=-1
UNET Use Existing IB Tables=-1
Instantaneous Interval=1HOUR
Write IC File= 0
IC Time=0
Write Velocity= 0
Write Detailed= 0

--- W167-00-00pp.f01 (steady flow) ---

Flow Title=FEMA Effective
Version=Version 3.0.1  Mar 2001
Number of Profiles= 4
Profile Names=10PCT_10yr,2PCT_50yr,1PCT_100yr,0.2PCT_500yr
River Rch & RM=W167-00-00,W167-00-00_0020 ,45406.9
     200     317     383     596
River Rch & RM=W167-00-00,W167-00-00_0020 ,41948.7
     201     318     385     599
River Rch & RM=W167-00-00,W167-00-00_0020 ,38884.5
     260     413     499     777
River Rch & RM=W167-00-00,W167-00-00_0020 ,36832.1
     300     476     576     896
River Rch & RM=W167-00-00,W167-00-00_0020 ,27138.3
     489     775     938    1459
River Rch & RM=W167-00-00,W167-00-00_0020 ,19645.6
     634    1006    1217    1893
River Rch & RM=W167-00-00,W167-00-00_0020 ,10483.1
     812    1288    1558    2423
River Rch & RM=W167-00-00,W167-00-00_0020 ,9580.6
     856    1354    1633    2509
River Rch & RM=W167-00-00,W167-00-00_0020 ,8663.1
     901    1422    1710    2597
River Rch & RM=W167-00-00,W167-00-00_0020 ,6999.7
    1005    1580    1889    2800
River Rch & RM=W167-00-00,W167-00-00_0020 ,5470.4
    1057    1658    1978    2901
River Rch & RM=W167-00-00,W167-00-00_0020 ,4448.2
    1107    1734    2064    2999
River Rch & RM=W167-00-00,W167-00-00_0020 ,2000.0
    1227    1915    2269    3232
Boundary for River Rch & Prof#=W167-00-00,W167-00-00_0020 , 1
Up Type= 0
Dn Type= 3
Dn Slope=.001
Boundary for River Rch & Prof#=W167-00-00,W167-00-00_0020 , 2
Up Type= 0
Dn Type= 3
Dn Slope=.001
Boundary for River Rch & Prof#=W167-00-00,W167-00-00_0020 , 3
Up Type= 0
Dn Type= 3
Dn Slope=.001
Boundary for River Rch & Prof#=W167-00-00,W167-00-00_0020 , 4
Up Type= 0
Dn Type= 3
Dn Slope=.001
DSS Import GetInterval= 0
DSS Import GetPeak= 0
DSS Import FillOption= 0

--- W167-00-00pp.f03 (steady flow) ---

Flow Title=Floodway
Program Version=3.13
Number of Profiles= 2
Profile Names=1PCT_100_YR,1PCT_Floodway_100yrFW
River Rch & RM=W167-00-00,W167-00-00_0020       ,45406.9
     383     383
River Rch & RM=W167-00-00,W167-00-00_0020       ,41948.7
     385     385
River Rch & RM=W167-00-00,W167-00-00_0020       ,38884.5
     499     499
River Rch & RM=W167-00-00,W167-00-00_0020       ,36832.1
     576     576
River Rch & RM=W167-00-00,W167-00-00_0020       ,27138.3
     938     938
River Rch & RM=W167-00-00,W167-00-00_0020       ,19645.6
    1217    1217
River Rch & RM=W167-00-00,W167-00-00_0020       ,10483.1
    1558    1558
River Rch & RM=W167-00-00,W167-00-00_0020       ,9580.6
    1633    1633
River Rch & RM=W167-00-00,W167-00-00_0020       ,8663.1
    1710    1710
River Rch & RM=W167-00-00,W167-00-00_0020       ,6999.7
    1889    1889
River Rch & RM=W167-00-00,W167-00-00_0020       ,5470.4
    1978    1978
River Rch & RM=W167-00-00,W167-00-00_0020       ,4448.2
    2064    2064
River Rch & RM=W167-00-00,W167-00-00_0020       ,2000.0
    2269    2269
Boundary for River Rch & Prof#=W167-00-00,W167-00-00_0020       , 1
Up Type= 0
Dn Type= 3
Dn Slope=0.001
Boundary for River Rch & Prof#=W167-00-00,W167-00-00_0020       , 2
Up Type= 0
Dn Type= 1
Dn Known WS=73.1
DSS Import GetInterval= 0
DSS Import GetPeak= 0
DSS Import FillOption= 0

--- W167-00-00pp.g01 (geometry) ---

Geom Title=W167-00-00
Version=Version 3.0.1  Mar 2001

River Reach=W167-00-00      ,W167-00-00_0020
Reach XY= 30
      3053628.47     13878676.54      3053762.75       13875323.
      3054167.25       13875327.        3054226.       13875239.
      3054332.25       13872690.        3054096.       13872608.
      3054384.75       13864458.      3054505.51     13858140.64
        3054233.       13856957.        3051285.       13851107.
      3050368.56     13850545.82      3050257.54     13850530.31
      3048828.67     13850518.79       3048611.5       13850453.
      3045558.75       13850388.       3045221.5       13850316.
        3043669.       13850295.       3043621.5       13850183.
      3043678.75       13848195.      3043295.75       13847941.
      3043175.75      13847563.3       3042674.5       13847158.
        3042302.       13846763.      3042018.75       13846340.
        3041715.       13846037.        3041542.       13845887.
        3041279.       13845819.      3041199.25       13845652.
       3041190.5       13845456.      3041004.25       13844816.

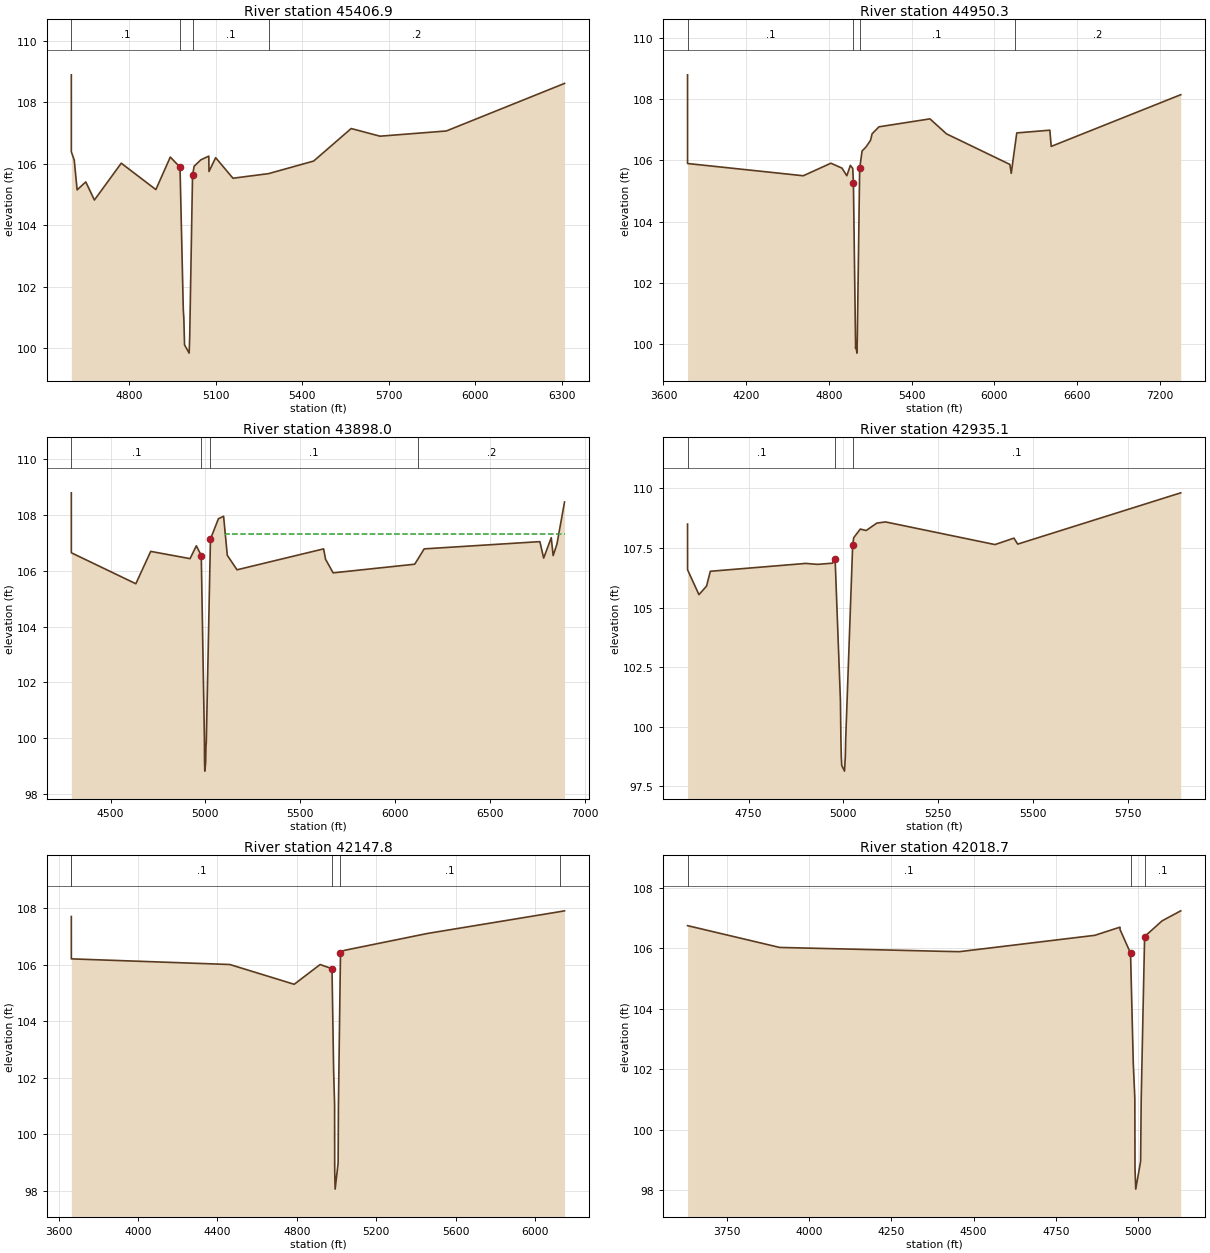
Type RM Length L Ch R = 1 ,45406.9 ,468.2,456.6,448.4
BEGIN DESCRIPTION:
Cross Section 45406.9
END DESCRIPTION:
XS GIS Cut Line= 6
      3054017.28     13878625.29      3053844.05     13878626.92
       3053723.1     13878680.43      3053627.79      13878676.5
      3053528.07     13878673.23      3052370.07     13879023.94
#Sta/Elev= 28
  4599.8   108.9  4599.9  106.39  4609.9  106.12  4619.9  105.15  4649.9  105.41
  4679.9  104.82    4773  106.02    4893  105.16  4943.1  106.22  4976.8  105.89
  4988.2  101.23    4990  100.98  4992.5   100.1  5008.5   99.83  5010.4  100.37
  5020.2  105.62  5025.7  105.92  5049.1  106.13  5076.6  106.25  5077.3  105.75
  5100.4   106.2  5160.4  105.53  5283.9  105.68  5440.4  106.09  5570.4  107.15
  5670.4   106.9  5900.4  107.07  6310.4  108.62
#Mann= 4 , 1 , 0
  4599.8      .1       0  4976.8     .04       0  5020.2      .1       0
  5283.9      .2       0
Bank Sta=4976.8,5020.2
XS Rating Curve= 0
Exp/Cntr=.3,.1

Type RM Length L Ch R = 1 ,44950.3 ,1001.7,1052.3,1134
BEGIN DESCRIPTION:
Cross Section 44950.3
END DESCRIPTION:
XS GIS Cut Line= 4
      3054866.99       13878306.       3053731.3     13878217.68
      3053591.61     13878221.94      3051332.03     13878651.43
#Sta/Elev= 30
  3774.9   108.8    3775   105.9    4615   105.5    4815  105.91  4895.3  105.75
  4930.8   105.5  4956.1  105.84  4973.7  105.74  4978.5  105.27  4993.5  100.19
  4994.7   99.85  4996.2   99.98  5003.8    99.7  5005.3   99.93  5006.6  100.16
  5023.9  105.74  5041.3  106.31  5069.6  106.44    5103  106.66  5113.9  106.87
  5163.9   107.1  5533.9  107.36  5653.9  106.87  6113.9  105.87  6123.9  105.58
  6148.3  106.39  6163.9   106.9  6403.9  106.99  6413.9  106.46  7353.9  108.15
#Mann= 4 , 1 , 0
  3774.9      .1       0  4978.5     .04       0  5023.9      .1       0
  6148.3      .2       0
#XS Ineff= 2 , 0
       0                  5533.9       0  107.36
Permanent Ineff=
       F       F
Bank Sta=4978.5,5023.9
XS Rating Curve= 0
Exp/Cntr=.3,.1

Type RM Length L Ch R = 1 ,43898.0 ,962.8,962.9,1122.7
BEGIN DESCRIPTION:
Cross Section 43898.0
END DESCRIPTION:
XS GIS Cut Line= 6
      3054365.49     13877314.01      3053949.35     13877268.01
      3053844.05     13877222.88      3053748.82     13877169.64
      3053517.55     13877166.29       3051792.9     13877247.57
#Sta/Elev= 30
  4293.4   108.8  4293.5  106.65  4633.5  105.54    4712   106.7  4919.4  106.44
  4952.5   106.9  4978.5  106.55  4995.1   99.97  4995.7   99.16  4997.1   98.82
  5001.4    99.1  5003.4   99.71    5005   99.86  5026.9  107.14  5068.8  107.87
  5096.2  107.96  5115.7  106.56    5167  106.04  5623.6  106.79  5633.6  106.42
  5673.6  105.93  6103.6  106.24  6121.2  106.43  6153.6  106.79  6763.6  107.05
  6783.6  106.46  6823.6  107.19  6833.6  106.55  6853.6  106.96  6893.6  108.47
#Mann= 4 , 1 , 0
  4293.4      .1       0  4978.5     .04       0  5026.9      .1       0
  6121.2      .2       0
#XS Ineff= 2 , 0
       0                  5105.7       0  107.32
Permanent Ineff=
       F       F
Bank Sta=4978.5,5026.9
XS Rating Curve= 0
Exp/Cntr=.3,.1

Type RM Length L Ch R = 1 ,42935.1 ,735.5,787.3,792.9
BEGIN DESCRIPTION:
Cross Section 42935.1
END DESCRIPTION:
XS GIS Cut Line= 4
       3054128.6     13876274.35      3053822.24      13876211.3
      3053624.51     13876201.84      3052835.49      13876161.2
#Sta/Elev= 26
  4589.2   108.5  4589.3  106.58  4619.3  105.54  4639.3   105.9  4649.3  106.52
  4901.1  106.85  4931.7  106.81  4971.8  106.86  4978.4  107.03  4992.4  101.11
  4993.6   99.59  4994.7   98.75  4995.8   98.38  5003.2   98.14  5005.4   98.79
  5006.3   99.48  5024.7  107.62  5027.5  107.93  5044.8  108.29  5060.3  108.23
  5088.3  108.54  5111.3  108.59    5400  107.64    5450  107.91    5460  107.66
    5890  109.81
#Mann= 3 , 1 , 0
  4589.2      .1       0  4978.4     .04       0  5024.7      .1       0
#XS Ineff= 2 , 0
       0  4649.3  106.52               0
Permanent Ineff=
       F       F
Bank Sta=4978.4,5024.7
XS Rating Curve= 0
Exp/Cntr=.3,.1

Type RM Length L Ch R = 1 ,42147.8 ,77.3,129.1,161.9
BEGIN DESCRIPTION:
Cross Section 42147.8-INTERPOLATED
END DESCRIPTION:
XS GIS Cut Line= 6
      3054818.18     13876132.34      3054083.44     13875819.69
      3053864.58     13875579.98      3053807.26     13875428.87
      3053718.67     13875413.24      3052611.68     13875495.11
#Sta/Elev= 18
  3663.6   107.7  3663.7   106.2  4462.2     106  4786.8   105.3  4917.5     106
  4977.3  105.85  4985.6  102.22  4990.3  101.06  4990.9   98.71  4993.1   98.05
  5008.1   98.97  5009.7  101.01  5015.5  104.05  5020.1   106.4  5039.1   106.5
  5459.1   107.1    6125  107.87  6149.1   107.9
#Mann= 5 , 1 , 0
  3663.6      .2       0  3663.7      .1       0  4977.3     .04       0
  5020.1      .1       0    6125      .2       0
#XS Ineff= 2 , 0
       0  4917.5     106               0
Permanent Ineff=
       F       F
Bank Sta=4977.3,5020.1
XS Rating Curve= 0
Exp/Cntr=.5,.3

Type RM Length L Ch R = 1 ,42018.7 ,23,23,23
BEGIN DESCRIPTION:
Upstream Section of Bridge/Culvert/Weir
END DESCRIPTION:
XS GIS Cut Line= 6
      3054836.95     13876074.34      3054078.85     13875773.22
      3053851.24     13875504.04      3053791.89     13875331.91
       3053793.5     13875216.26      3053761.76     13875204.06
#Sta/Elev= 25
    3630  106.75    3910  106.03    4410   105.9  4456.9  105.89  4799.7  106.34
  4868.5  106.43  4945.3   106.7  4945.4  106.62  4977.3  105.84  4982.3  103.65
  4985.6  102.21  4990.3  101.05 4990.75   99.29 4990.84   98.93  4990.9    98.7
  4993.1   98.04  5007.9   98.96 5008.04   99.12 5008.15   99.24  5009.7     101
  5011.8   102.1  5015.5  104.04  5020.1  106.39  5073.4  106.91    5130  107.24
#Mann= 3 , 1 , 0
    3630      .1       0  4977.3     .04       0  5020.1      .1       0
#XS Ineff= 2 , 0
       0  4990.2     101  5009.8       0     101
Permanent Ineff=
       F       F
Bank Sta=4977.3,5020.1
XS Rating Curve= 0
Exp/Cntr=.5,.3

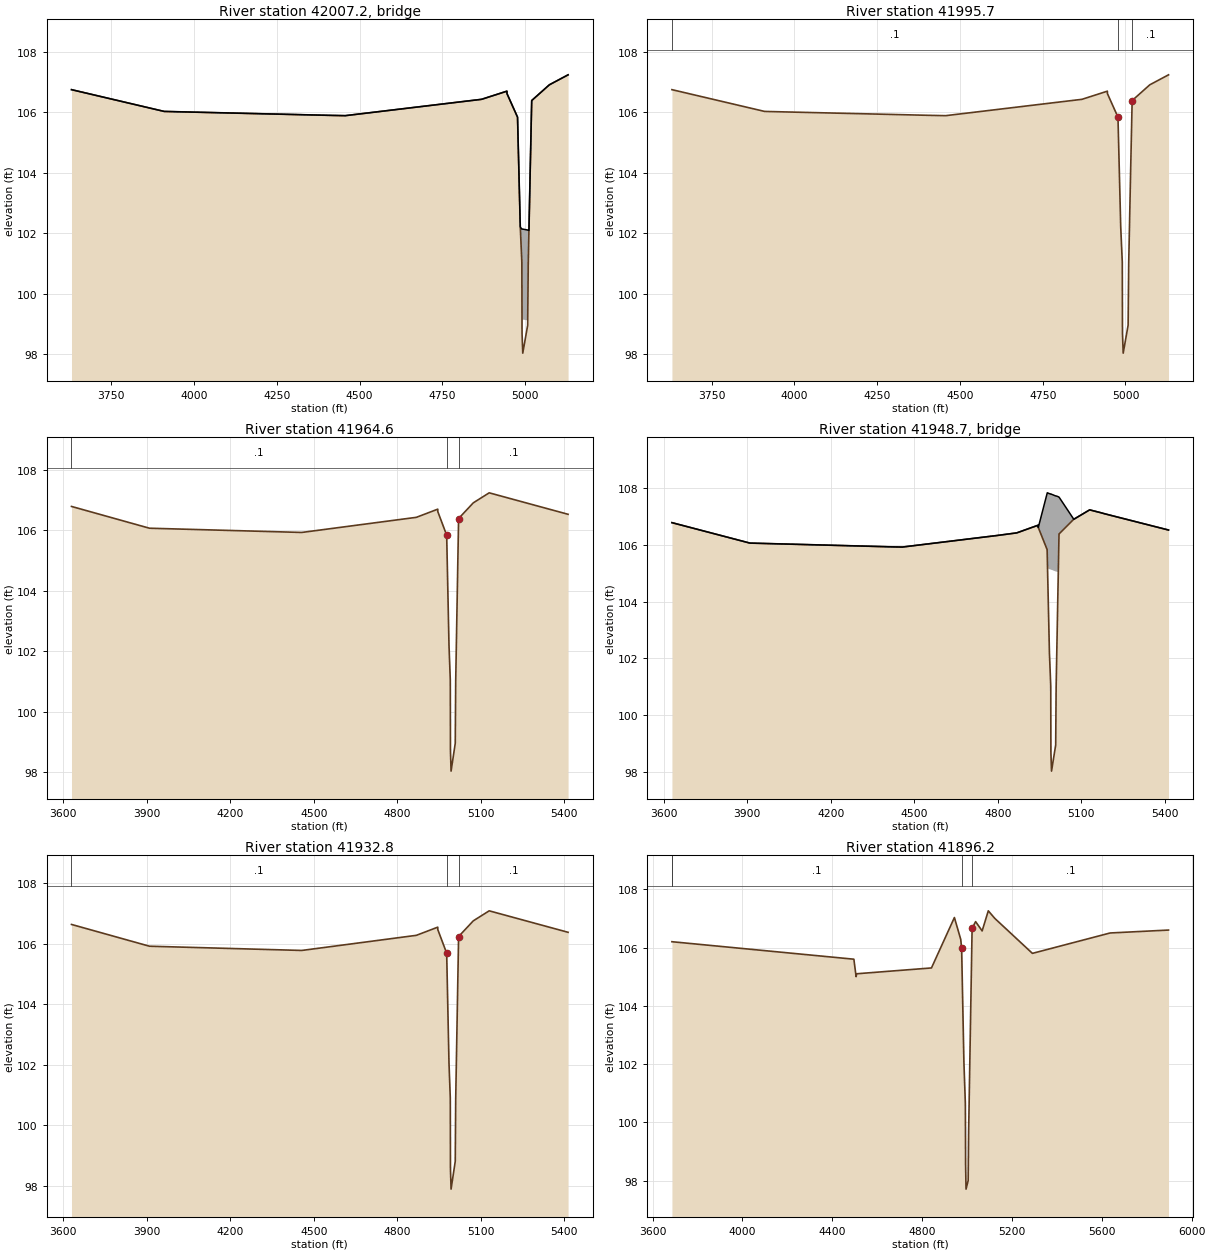
Type RM Length L Ch R = 3 ,42007.2 ,,,
BEGIN DESCRIPTION:
36" PIPELINE
END DESCRIPTION:
Bridge Culvert--1,0,-1,-1, 0
Deck Dist Width WeirC Skew NumUp NumDn MinLoCord MaxHiCord MaxSubmerge Is_Ogee
10,3,2.6,0, 25, 25, , , .95, 0, 1,1,,
    3630    3910    4410  4456.9  4799.7  4868.5  4945.3  4945.4  4977.3  4982.3
  4985.6  4990.3 4990.75 4990.84  4990.9  4993.1  5007.9 5008.04 5008.15  5009.7
  5011.8  5015.5  5020.1  5073.4    5130
  106.75  106.03   105.9  105.89  106.34  106.43   106.7  106.62  105.84  103.65
  102.21  102.14  102.14  102.14  102.14  102.14  102.11  102.11  102.11   102.1
   102.1  104.04  106.39  106.91  107.24
  106.75  106.03   105.9  105.89  106.34  106.43   106.7  106.62  105.84  103.65
  102.21  101.05   99.29   99.15   99.15   99.15   99.12   99.12   99.24     101
   102.1  104.04  106.39  106.91  107.24
    3630    3910    4410  4456.9  4799.7  4868.5  4945.3  4945.4  4977.3  4982.3
  4985.6  4990.3 4990.75 4990.84  4990.9  4993.1  5007.9 5008.04 5008.15  5009.7
  5011.8  5015.5  5020.1  5073.4    5130
  106.75  106.03   105.9  105.89  106.34  106.43   106.7  106.62  105.84  103.65
  102.21  102.14  102.14  102.14  102.14  102.14  102.11  102.11  102.11   102.1
   102.1  104.04  106.39  106.91  107.24
  106.75  106.03   105.9  105.89  106.34  106.43   106.7  106.62  105.84  103.65
  102.21  101.05   99.29   99.15   99.15   99.15   99.12   99.12   99.24     101
   102.1  104.04  106.39  106.91  107.24
BR Coef= 1 , 1 , 0 ,1.25, 0 ,,,.8,0,2,0,
WSPro=,,,, 1 ,,,, 0 ,,,, 0 ,,,,-1 ,-1 ,-1 , 0 , 0 , 0 , 0 , 0
BR U #Sta/Elev= 25
    3630  106.75    3910  106.03    4410   105.9  4456.9  105.89  4799.7  106.34
  4868.5  106.43  4945.3   106.7  4945.4  106.62  4977.3  105.84  4982.3  103.65
  4985.6  102.21  4990.3  101.05 4990.75   99.29 4990.84   98.93  4990.9    98.7
  4993.1   98.04  5007.9   98.96 5008.04   99.12 5008.15   99.24  5009.7     101
  5011.8   102.1  5015.5  104.04  5020.1  106.39  5073.4  106.91    5130  107.24
BR U #Mann= 3
    3630      .1  4977.3     .04  5020.1      .1
BR U Banks=4977.3,5020.1
BR D #Sta/Elev= 25
    3630  106.75    3910  106.03    4410   105.9  4456.9  105.89  4799.7  106.34
  4868.5  106.43  4945.3   106.7  4945.4  106.62  4977.3  105.84  4982.3  103.65
  4985.6  102.21  4990.3  101.05 4990.75   99.29 4990.84   98.93  4990.9    98.7
  4993.1   98.04  5007.9   98.96 5008.04   99.12 5008.15   99.24  5009.7     101
  5011.8   102.1  5015.5  104.04  5020.1  106.39  5073.4  106.91    5130  107.24
BR D #Mann= 3
    3630      .1  4977.3     .04  5020.1      .1
BR D Banks=4977.3,5020.1
BC Design=,, 0 ,, 0 ,,,,,,
BC HTab HWMax=107.24

Type RM Length L Ch R = 1 ,41995.7 ,31.1,31.1,31.1
BEGIN DESCRIPTION:
Downstream Section of Bridge/Culvert/Weir
END DESCRIPTION:
XS GIS Cut Line= 6
      3054859.94     13876074.83      3054101.85      13875773.7
      3053874.24     13875504.52      3053814.89     13875332.39
       3053816.5     13875216.74      3053784.75     13875204.54
#Sta/Elev= 25
    3630  106.74    3910  106.02    4410  105.89  4456.9  105.88  4799.7  106.33
  4868.5  106.42  4945.3  106.69  4945.4  106.61  4977.3  105.83  4982.3  103.64
  4985.6   102.2  4990.3  101.04 4990.75   99.28 4990.84   98.92  4990.9   98.69
  4993.1   98.03  5007.9   98.95 5008.04   99.11 5008.15   99.23  5009.7  100.99
  5011.8  102.09  5015.5  104.03  5020.1  106.38  5073.4   106.9    5130  107.23
#Mann= 3 , 1 , 0
    3630      .1       0  4977.3     .04       0  5020.1      .1       0
#XS Ineff= 2 , 0
       0  4990.2     101  5009.8       0     101
Permanent Ineff=
       F       F
Bank Sta=4977.3,5020.1
XS Rating Curve= 0
Exp/Cntr=.5,.3

Type RM Length L Ch R = 1 ,41964.6 ,31.8,31.8,31.8
BEGIN DESCRIPTION:
Upstream Section of Bridge/Culvert/Weir
END DESCRIPTION:
XS GIS Cut Line= 6
      3054881.55      13876059.4      3054091.52     13875758.36
      3053872.16     13875483.09      3053847.56     13875377.86
      3053848.44     13875168.32       3053601.9     13875062.94
#Sta/Elev= 17
    3630  106.78    3910  106.06  4456.9  105.92  4868.5  106.42  4945.3  106.69
  4945.4  106.61  4977.3  105.83  4985.6   102.2  4990.3  101.04  4990.9   98.69
  4993.1   98.03  5008.1   98.95  5009.7  100.99  5020.1  106.38    5073   106.9
    5130  107.23  5413.3  106.52
#Mann= 3 , 1 , 0
    3630      .1       0  4977.3     .04       0  5020.1      .1       0
#XS Ineff= 2 , 0
       0    4968  105.85    5028       0     106
Permanent Ineff=
       F       F
Bank Sta=4977.3,5020.1
XS Rating Curve= 0
Exp/Cntr=.5,.3

Type RM Length L Ch R = 3 ,41948.7 ,,,
BEGIN DESCRIPTION:
THOMAS STREET-ACCESS ROAD
Structure ID: W67-18
END DESCRIPTION:
Bridge Culvert--1,0,-1,-1, 0
Deck Dist Width WeirC Skew NumUp NumDn MinLoCord MaxHiCord MaxSubmerge Is_Ogee
10,11.8,2.6,0, 33, 33, , , .95, 0, 1,1,,
    3630    3910    4410  4456.9  4799.7  4868.5  4919.5  4945.3  4945.4  4945.6
  4977.3  4977.7 4978.61  4978.7  4978.8  4985.6  4990.3  4990.9  4993.1  5008.1
  5009.7  5015.5  5017.5 5017.59  5017.7    5020  5020.1    5073  5073.4    5130
  5166.1  5188.7  5413.3
  106.78  106.06  105.93  105.92  106.33  106.42   106.6  106.69  106.61  106.61
  107.81  107.83  107.83  107.83  107.83   107.8  107.79  107.78  107.78  107.72
  107.72   107.7  107.69  107.69  107.69  107.68  107.68   106.9   106.9  107.23
  107.14  107.08  106.52
  106.78  106.06  105.93  105.92  106.33  106.42   106.6  106.69  106.61  106.61
  105.83  105.66  105.26  105.22  105.17  105.14  105.13  105.12  105.12  105.06
  105.06  105.04  105.05   105.1  105.15  106.33  106.38   106.9   106.9  107.23
  107.14  107.08  106.52
    3630    3910    4410  4456.9  4799.7  4868.5  4919.5  4945.3  4945.4  4945.6
  4977.3  4977.7 4978.61  4978.7  4978.8  4985.6  4990.3  4990.9  4993.1  5008.1
  5009.7  5015.5  5017.5 5017.59  5017.7    5020  5020.1    5073  5073.4    5130
  5166.1  5188.7  5413.3
  106.74  106.02  105.89  105.88  106.29  106.38  106.57  106.66  106.58  106.58
  107.81  107.83  107.83  107.83  107.83   107.8  107.79  107.78  107.78  107.72
  107.72   107.7  107.69  107.69  107.69  107.68  107.68  106.89  106.89   107.2
  107.11  107.05  106.48
  106.69  105.97  105.84  105.83  106.24  106.33  106.51   106.6  106.52  106.52
  105.74  105.57  105.17  105.13  105.08  105.05  105.04  105.03  105.03  104.97
  104.97  104.95  104.96  105.01  105.06  106.24  106.29  106.81  106.81  107.14
  107.05  106.99  106.43
BR Coef= 1 , 1 , 0 ,1.25, 0 ,,,.8,-1,2,0,
WSPro=,,,, 1 ,,,, 0 ,,,, 0 ,,,,-1 ,-1 ,-1 , 0 , 0 , 0 , 0 , 0
BR U #Sta/Elev= 33
    3630  106.78    3910  106.06    4410  105.93  4456.9  105.92  4799.7  106.33
  4868.5  106.42  4919.5   106.6  4945.3  106.69  4945.4  106.61  4945.6  106.61
  4977.3  105.83  4977.7  105.66 4978.61  105.26  4978.7  105.22  4978.8  105.17
  4985.6   102.2  4990.3  101.04  4990.9   98.69  4993.1   98.03  5008.1   98.95
  5009.7  100.99  5015.5  104.03  5017.5  105.05 5017.59   105.1  5017.7  105.15
    5020  106.33  5020.1  106.38    5073   106.9  5073.4   106.9    5130  107.23
  5166.1  107.14  5188.7  107.08  5413.3  106.52
BR U #Mann= 3
    3630      .1  4977.3     .04  5020.1      .1
BR U Banks=4977.3,5020.1
BR D #Sta/Elev= 33
    3630  106.69    3910  105.97    4410  105.84  4456.9  105.83  4799.7  106.24
  4868.5  106.33  4919.5  106.51  4945.3   106.6  4945.4  106.52  4945.6  106.52
  4977.3  105.74  4977.7  105.57 4978.61  105.17  4978.7  105.13  4978.8  105.08
  4985.6  102.11  4990.3  100.95  4990.9    98.6  4993.1   97.94  5008.1   98.86
  5009.7   100.9  5015.5  103.94  5017.5  104.96 5017.59  105.01  5017.7  105.06
    5020  106.24  5020.1  106.29    5073  106.81  5073.4  106.81    5130  107.14
  5166.1  107.05  5188.7  106.99  5413.3  106.43
BR D #Mann= 3
    3630      .1  4977.3     .04  5020.1      .1
BR D Banks=4977.3,5020.1
BC Design=,, 0 ,, 0 ,,,,,,
BC HTab HWMax=107.23

Type RM Length L Ch R = 1 ,41932.8 ,36.6,36.6,36.6
BEGIN DESCRIPTION:
Downstream Section of Bridge/Culvert/Weir
END DESCRIPTION:
XS GIS Cut Line= 6
      3054913.34     13876060.08      3054123.32     13875759.04
      3053903.96     13875483.77      3053879.36     13875378.54
      3053880.24       13875169.      3053633.69     13875063.62
#Sta/Elev= 17
    3630  106.64    3910  105.92  4456.9  105.78  4868.5  106.28  4945.3  106.55
  4945.4  106.47  4977.3  105.69  4985.6  102.06  4990.3   100.9  4990.9   98.55
  4993.1   97.89  5008.1   98.81  5009.7  100.85  5020.1  106.24    5073  106.76
    5130  107.09  5413.3  106.38
#Mann= 3 , 1 , 0
    3630      .1       0  4977.3     .04       0  5020.1      .1       0
#XS Ineff= 2 , 0
       0    4968  105.85    5028       0     106
Permanent Ineff=
       F       F
Bank Sta=4977.3,5020.1
XS Rating Curve= 0
Exp/Cntr=.5,.3

Type RM Length L Ch R = 1 ,41896.2 ,108.5,110,111.2
BEGIN DESCRIPTION:
Cross Section 41896.2
END DESCRIPTION:
XS GIS Cut Line= 6
      3054932.85     13875791.37      3054112.02     13875741.01
      3053912.59     13875474.13      3053895.48     13875025.93
      3053573.19     13874900.04      3053313.77     13874917.73
#Sta/Elev= 23
  3686.1   106.2  4496.1   105.6  4506.1     105  4508.5   105.1  4841.6   105.3
  4943.7  107.03  4971.9  106.28  4975.9  105.97    4986  102.07  4992.4  100.65
    4993   99.74  4993.6   98.53  4995.5   97.71  5004.9      98    5007   99.65
  5022.5  106.66  5038.1  106.89  5067.2  106.57  5094.6  107.26  5123.6     107
    5291   105.8    5637   106.5    5897   106.6
#Mann= 4 , 1 , 0
  3686.1      .2       0  3686.1      .1       0  4975.9     .04       0
  5022.5      .1       0
Bank Sta=4975.9,5022.5
XS Rating Curve= 0
Exp/Cntr=.3,.1

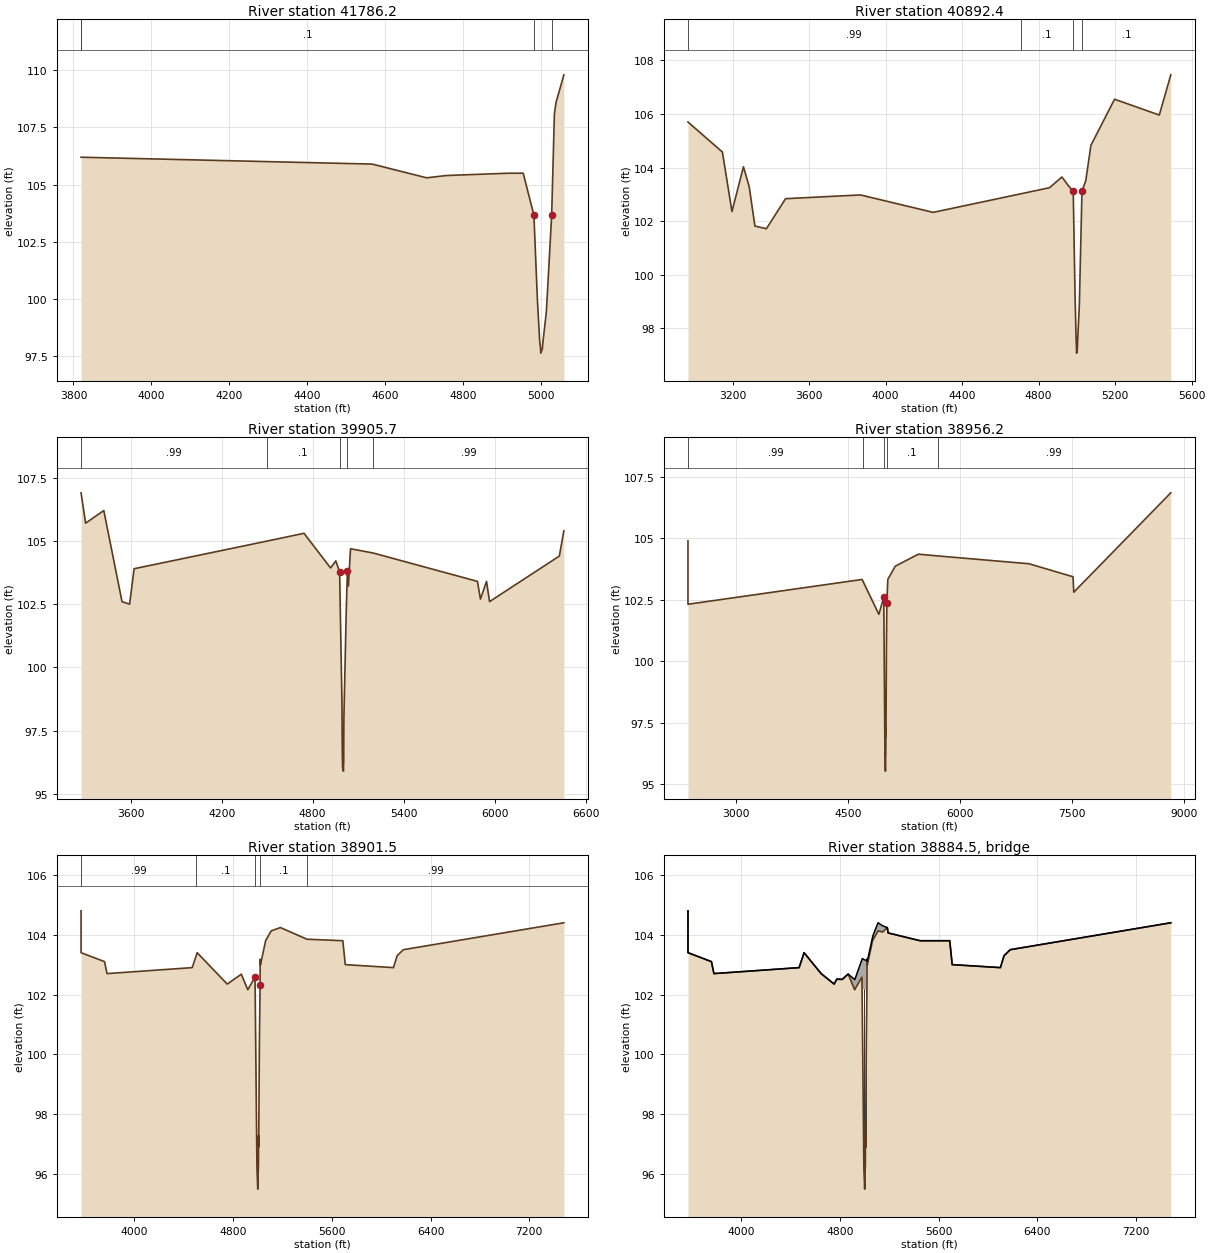
Type RM Length L Ch R = 1 ,41786.2 ,1548.6,893.8,831.7
BEGIN DESCRIPTION:
Cross Section 41786.2-INTERPOLATED
END DESCRIPTION:
XS GIS Cut Line= 5
       3054970.9     13875728.42       3054225.5     13875686.68
      3054019.17     13875406.87      3054025.96     13875282.79
       3054025.4     13875262.79
#Sta/Elev= 18
  3819.4   106.2    4566   105.9    4706   105.3    4756   105.4  4913.6   105.5
  4953.6   105.5    4981  103.67  4990.1   99.93  4995.9   98.16  4997.6   97.92
  4998.6   97.64  5002.6   97.82  5004.2   98.13    5013   99.45  5026.6  103.67
  5033.6   108.1  5037.9   108.6  5057.9   109.8
#Mann= 4 , 1 , 0
  3819.4      .2       0  3819.4      .1       0    4981     .04       0
  5026.6      .1       0
Bank Sta=4981,5026.6
XS Rating Curve= 0
Exp/Cntr=.3,.1

Type RM Length L Ch R = 1 ,40892.4 ,941.2,986.7,1066.6
BEGIN DESCRIPTION:
Cross Section 40892.4
END DESCRIPTION:
XS GIS Cut Line= 6
      3056110.56     13874043.75      3055377.21     13874568.38
      3054388.77     13874568.38      3054301.51     13874602.39
      3054255.53     13874602.75      3053761.97     13874621.46
#Sta/Elev= 28
  2967.2   105.7  3147.2  104.58  3197.2  102.36  3257.2  104.03  3287.2  103.29
  3317.2  101.82  3377.2  101.72  3477.2  102.84  3868.9  102.98  4248.9  102.33
  4705.5  103.02  4857.3  103.25  4921.8  103.65  4955.2  103.33    4981  103.11
  4990.1   99.37  4995.9    97.6  4997.6   97.36  4998.6   97.08  5002.6   97.26
  5004.2   97.57    5013   98.89  5026.6  103.11  5046.7  103.52  5073.4  104.83
    5197  106.55  5430.9  105.96  5490.9  107.46
#Mann= 4 , 1 , 0
  2967.2     .99       0  4705.5      .1       0    4981     .04       0
  5026.6      .1       0
Bank Sta=4981,5026.6
XS Rating Curve= 0
Exp/Cntr=.3,.1

Type RM Length L Ch R = 1 ,39905.7 ,1103.9,949.5,626.6
BEGIN DESCRIPTION:
Cross Section 39905.7
END DESCRIPTION:
XS GIS Cut Line= 4
      3056019.73     13873651.55      3054364.59     13873625.18
      3054207.68     13873607.15       3052841.4     13873708.15
#Sta/Elev= 30
  3273.2   106.9  3303.2   105.7  3423.2   106.2  3543.2   102.6  3593.2   102.5
  3623.2   103.9  4497.4  104.99  4743.2   105.3  4918.2  103.93  4952.8  104.21
  4977.9  103.77  4993.8   98.46  4994.6   97.26  4995.9   96.52  4997.7   96.04
    5003    95.9  5005.1   96.33  5005.4   97.18  5006.3   98.05  5021.3  102.15
  5029.4  103.82  5035.8  103.22  5049.8  104.69    5200  104.52  5886.5   103.4
  5906.5   102.7  5946.5   103.4  5966.5   102.6  6426.5   104.4  6456.5   105.4
#Mann= 5 , 1 , 0
  3273.2     .99       0  4497.4      .1       0  4977.9     .04       0
  5029.4      .1       0    5200     .99       0
Bank Sta=4977.9,5029.4
XS Rating Curve= 0
Exp/Cntr=.3,.1

Type RM Length L Ch R = 1 ,38956.2 ,85.1,54.7,53.8
BEGIN DESCRIPTION:
Cross Section 38956.2-INTERPOLATED
END DESCRIPTION:
XS GIS Cut Line= 6
      3056923.75     13872865.36      3054608.31     13872573.82
      3054386.34     13872603.14      3054298.04     13872792.95
      3054066.99     13873000.17      3050741.77      13873609.9
#Sta/Elev= 24
  2355.8   104.9  2355.9  102.32  4689.6  103.33  4699.9  103.26  4913.5  101.91
  4979.1  102.61  4987.8   99.16  4992.1   97.38  4994.6   96.24  4995.1    96.2
  5001.3   95.52  5006.7   96.39  5007.9   97.31  5008.7   96.93  5014.6  100.51
  5020.2  102.36  5033.3  103.33  5132.9  103.87  5443.2  104.36    5700  104.29
  6924.7  103.97  7514.7  103.44  7524.7  102.81  8824.7  106.86
#Mann= 5 , 1 , 0
  2355.8     .99       0  4699.9      .1       0  4979.1     .04       0
  5020.2      .1       0    5700     .99       0
Bank Sta=4979.1,5020.2
XS Rating Curve= 0
Exp/Cntr=.5,.3

Type RM Length L Ch R = 1 ,38901.5 ,34,34,34
BEGIN DESCRIPTION:
Upstream Section of Bridge/Culvert/Weir
END DESCRIPTION:
XS GIS Cut Line= 6
      3055484.25     13872341.47      3054426.76     13872314.98
      3054294.12     13872556.36      3054279.69     13872745.19
      3054067.44     13872931.39      3051981.87     13873214.35
#Sta/Elev= 30
  3570.3   104.8  3570.4   103.4  3760.4   103.1  3780.4   102.7  4470.4   102.9
  4499.5  103.26  4510.4   103.4  4753.9  102.35    4868  102.68  4920.2  102.16
  4979.1  102.58  4994.6   96.21  5001.3   95.49  5006.7   96.36  5007.9   97.28
  5008.7    96.9  5014.6  100.48  5020.1  102.33  5020.5  103.18  5022.7  102.99
  5065.6  103.81  5110.3  104.13  5184.4  104.24    5400  103.85    5690   103.8
    5710     103    6100   102.9    6130   103.3    6180   103.5    7480   104.4
#Mann= 5 , 1 , 0
  3570.3     .99       0  4499.5      .1       0  4979.1     .02       0
  5020.1      .1       0    5400     .99       0
#XS Ineff= 2 , 0
       0    4972   102.3    5030       0   102.5
Permanent Ineff=
       F       F
Bank Sta=4979.1,5020.1
XS Rating Curve= 0
Exp/Cntr=.5,.3

Type RM Length L Ch R = 3 ,38884.5 ,,,
BEGIN DESCRIPTION:
TANNER STREET-ACCESS ROAD NORTH
Structure ID: W67-17
END DESCRIPTION:
Bridge Culvert--1,0,-1,-1, 0
Deck Dist Width WeirC Skew NumUp NumDn MinLoCord MaxHiCord MaxSubmerge Is_Ogee
10,14,2.6,0, 55, 55, , , .95, 0, 1,1,,
  3570.3  3570.4  3760.4  3780.4  4470.4  4499.5  4510.4  4648.6  4753.9  4774.4
  4775.1  4818.9  4821.6    4868  4868.7  4920.2  4921.3  4979.1  4981.9 4982.01
  4982.1  4982.2  4987.8  4992.1  4994.6  4995.1  5001.3  5006.7  5007.9  5008.7
  5014.6  5019.9 5019.99  5020.1  5020.2  5020.5  5022.5  5022.7  5065.6  5067.3
  5109.4  5110.3    5146  5146.6  5182.5  5184.4  5191.4    5400    5450    5690
    5710    6100    6130    6180    7480
   104.8   103.4   103.1   102.7   102.9  103.26   103.4   102.7  102.35  102.51
  102.52  102.51  102.52  102.69  102.68   102.5   102.5  103.17   103.2   103.2
   103.2   103.2  103.19  103.18  103.17  103.17  103.16  103.15  103.15  103.15
  103.14  103.13  103.12  103.12  103.12  103.19  103.12  103.12  103.93  103.96
   104.4   104.4   104.3   104.3  104.24  104.24  104.06  103.85   103.8   103.8
     103   102.9   103.3   103.5   104.4
   104.8   103.4   103.1   102.7   102.9  103.26   103.4   102.7  102.35   102.5
  102.51   102.5  102.51  102.68  102.67  102.16  102.17  102.58  101.47  101.43
   102.2   102.2  102.19  102.18  102.17  102.17  102.16  102.15  102.15  102.15
  102.14  102.26  102.29  102.33  102.54  103.18  103.01  102.99  103.81  103.82
  104.12  104.13  104.09  104.09  104.23  104.24  104.06  103.85   103.8   103.8
     103   102.9   103.3   103.5   104.4
  3570.3  3570.4  3760.4  3780.4  4470.4  4499.5  4510.4  4648.6  4753.9  4774.4
  4775.1  4818.9  4821.6    4868  4868.7  4920.2  4921.3  4979.1  4981.9 4982.01
  4982.1  4982.2  4987.8  4992.1  4994.6  4995.1  5001.3  5006.7  5007.9  5008.7
  5014.6  5019.9 5019.99  5020.1  5020.2  5020.5  5022.5  5022.7  5065.6  5067.3
  5109.4  5110.3    5146  5146.6  5182.5  5184.4  5191.4    5400    5450    5690
    5710    6100    6130    6180    7480
   104.8   103.4   103.1   102.7   102.9  103.26   103.4   102.7  102.35  102.51
  102.52  102.51  102.52  102.69  102.68   102.5   102.5  103.17   103.2   103.2
   103.2   103.2  103.19  103.18  103.17  103.17  103.16  103.15  103.15  103.15
  103.14  103.13  103.12  103.12  103.12  103.19  103.12  103.12  103.93  103.96
   104.4   104.4   104.3   104.3  104.24  104.24  104.06  103.85   103.8   103.8
     103   102.9   103.3   103.5   104.4
  104.73  103.33  103.03  102.63  102.83  103.19  103.33  102.63  102.28  102.43
  102.44  102.43  102.44  102.61   102.6  102.09   102.1  102.51   101.4  101.36
  102.13  102.13  102.12  102.11   102.1   102.1  102.09  102.08  102.08  102.08
  102.07  102.19  102.22  102.26  102.47  103.11  102.94  102.92  103.74  103.75
  104.05  104.06  104.02  104.02  104.16  104.17  103.99  103.78  103.73  103.73
  102.93  102.83  103.23  103.43  104.33
Pier Skew, UpSta & Num, DnSta & Num=  ,4995.2, 2 ,4995.2, 2 , 0 , 0 , 0 ,,
       1       1
    95.1  103.17
       1       1
   95.03   103.1
Pier Skew, UpSta & Num, DnSta & Num=  ,5008.7, 2 ,5008.7, 2 , 0 , 0 , 0 ,,
       1       1
   96.14  103.15
       1       1
   96.07  103.08
BR Coef= 1 , 1 , 0 ,1.25, 0 ,,,.8,0,2,0,
WSPro=,,,, 1 ,,,, 0 ,,,, 0 ,,,,-1 ,-1 ,-1 , 0 , 0 , 0 , 0 , 0
BR U #Sta/Elev= 55
  3570.3   104.8  3570.4   103.4  3760.4   103.1  3780.4   102.7  4470.4   102.9
  4499.5  103.26  4510.4   103.4  4648.6   102.7  4753.9  102.35  4774.4   102.5
  4775.1  102.51  4818.9   102.5  4821.6  102.51    4868  102.68  4868.7  102.67
  4920.2  102.16  4921.3  102.17  4979.1  102.58  4981.9  101.47 4982.01  101.43
  4982.1  101.39  4982.2  101.35  4987.8   99.13  4992.1   97.35  4994.6   96.21
  4995.1   96.17  5001.3   95.49  5006.7   96.36  5007.9   97.28  5008.7    96.9
  5014.6  100.48  5019.9  102.26 5019.99  102.29  5020.1  102.33  5020.2  102.54
  5020.5  103.18  5022.5  103.01  5022.7  102.99  5065.6  103.81  5067.3  103.82
  5109.4  104.12  5110.3  104.13    5146  104.09  5146.6  104.09  5182.5  104.23
  5184.4  104.24  5191.4  104.06    5400  103.85    5450   103.8    5690   103.8
    5710     103    6100   102.9    6130   103.3    6180   103.5    7480   104.4
BR U #Mann= 5
  3570.3     .99  4499.5      .1  4979.1     .02  5020.1      .1    5400     .99
BR U Banks=4979.1,5020.1
BR D #Sta/Elev= 55
  3570.3  104.73  3570.4  103.33  3760.4  103.03  3780.4  102.63  4470.4  102.83
  4499.5  103.19  4510.4  103.33  4648.6  102.63  4753.9  102.28  4774.4  102.43
  4775.1  102.44  4818.9  102.43  4821.6  102.44    4868  102.61  4868.7   102.6
  4920.2  102.09  4921.3   102.1  4979.1  102.51  4981.9   101.4 4982.01  101.36
  4982.1  101.32  4982.2  101.28  4987.8   99.06  4992.1   97.28  4994.6   96.14
  4995.1    96.1  5001.3   95.42  5006.7   96.29  5007.9   97.21  5008.7   96.83
  5014.6  100.41  5019.9  102.19 5019.99  102.22  5020.1  102.26  5020.2  102.47
  5020.5  103.11  5022.5  102.94  5022.7  102.92  5065.6  103.74  5067.3  103.75
  5109.4  104.05  5110.3  104.06    5146  104.02  5146.6  104.02  5182.5  104.16
  5184.4  104.17  5191.4  103.99    5400  103.78    5450  103.73    5690  103.73
    5710  102.93    6100  102.83    6130  103.23    6180  103.43    7480  104.33
BR D #Mann= 5
  3570.3     .99  4499.5      .1  4979.1     .02  5020.1      .1    5400     .99
BR D Banks=4979.1,5020.1
BC Design=,, 0 ,, 0 ,,,,,,
BC HTab HWMax=104.8