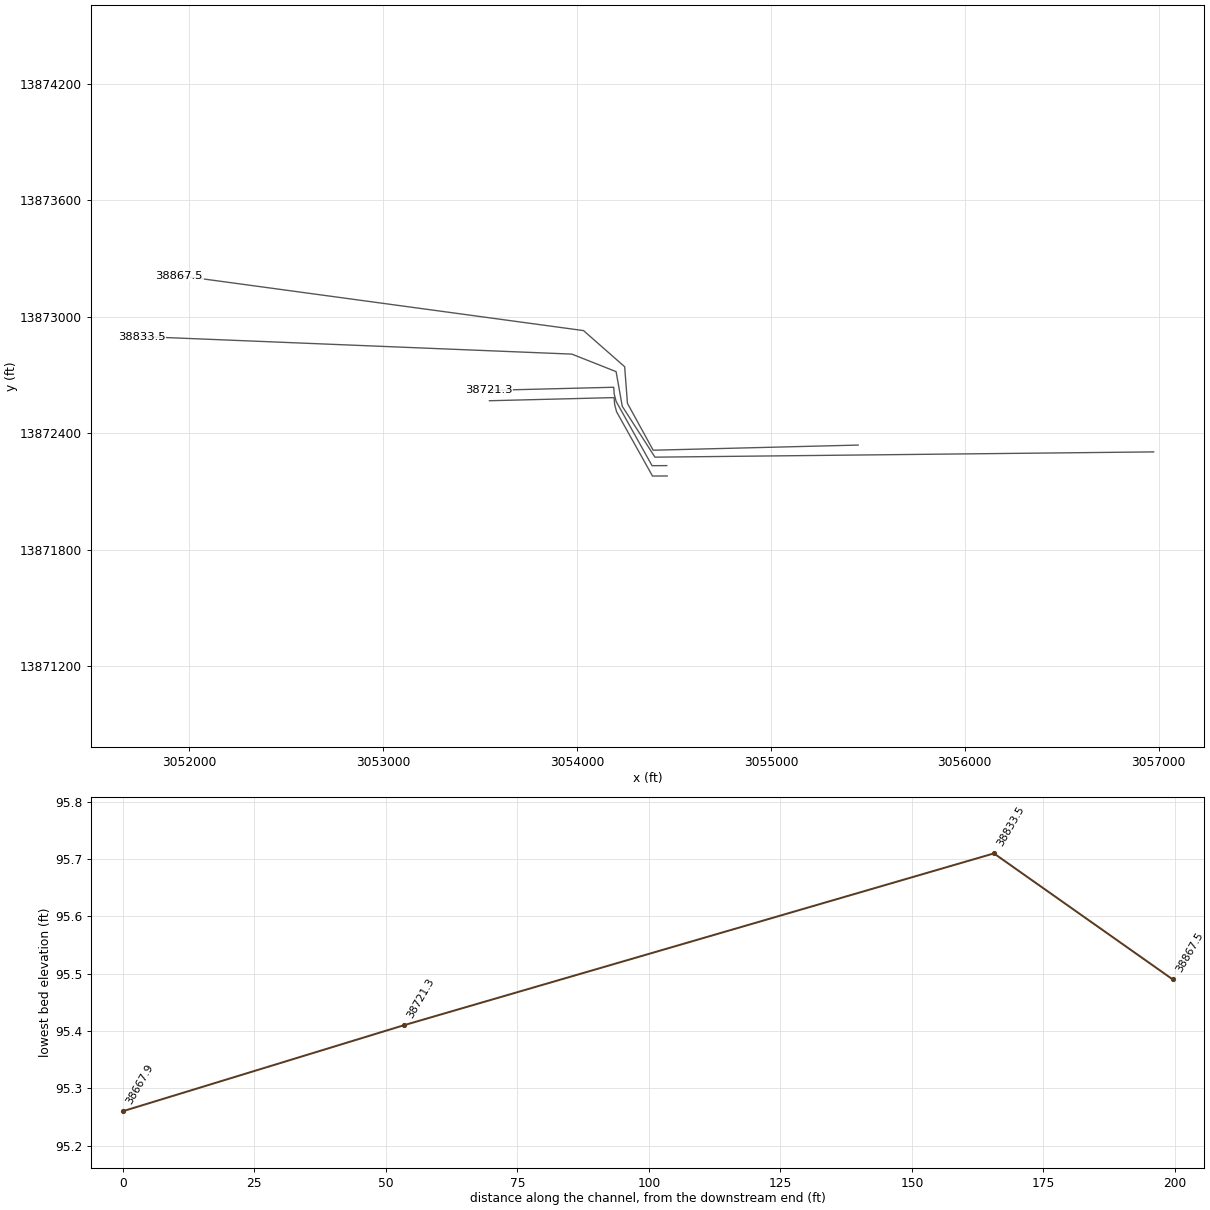
HEC-RAS study W167-00-00pp.prj: W167-00-00

--- W167-00-00pp.g01 (geometry) --- (continued)

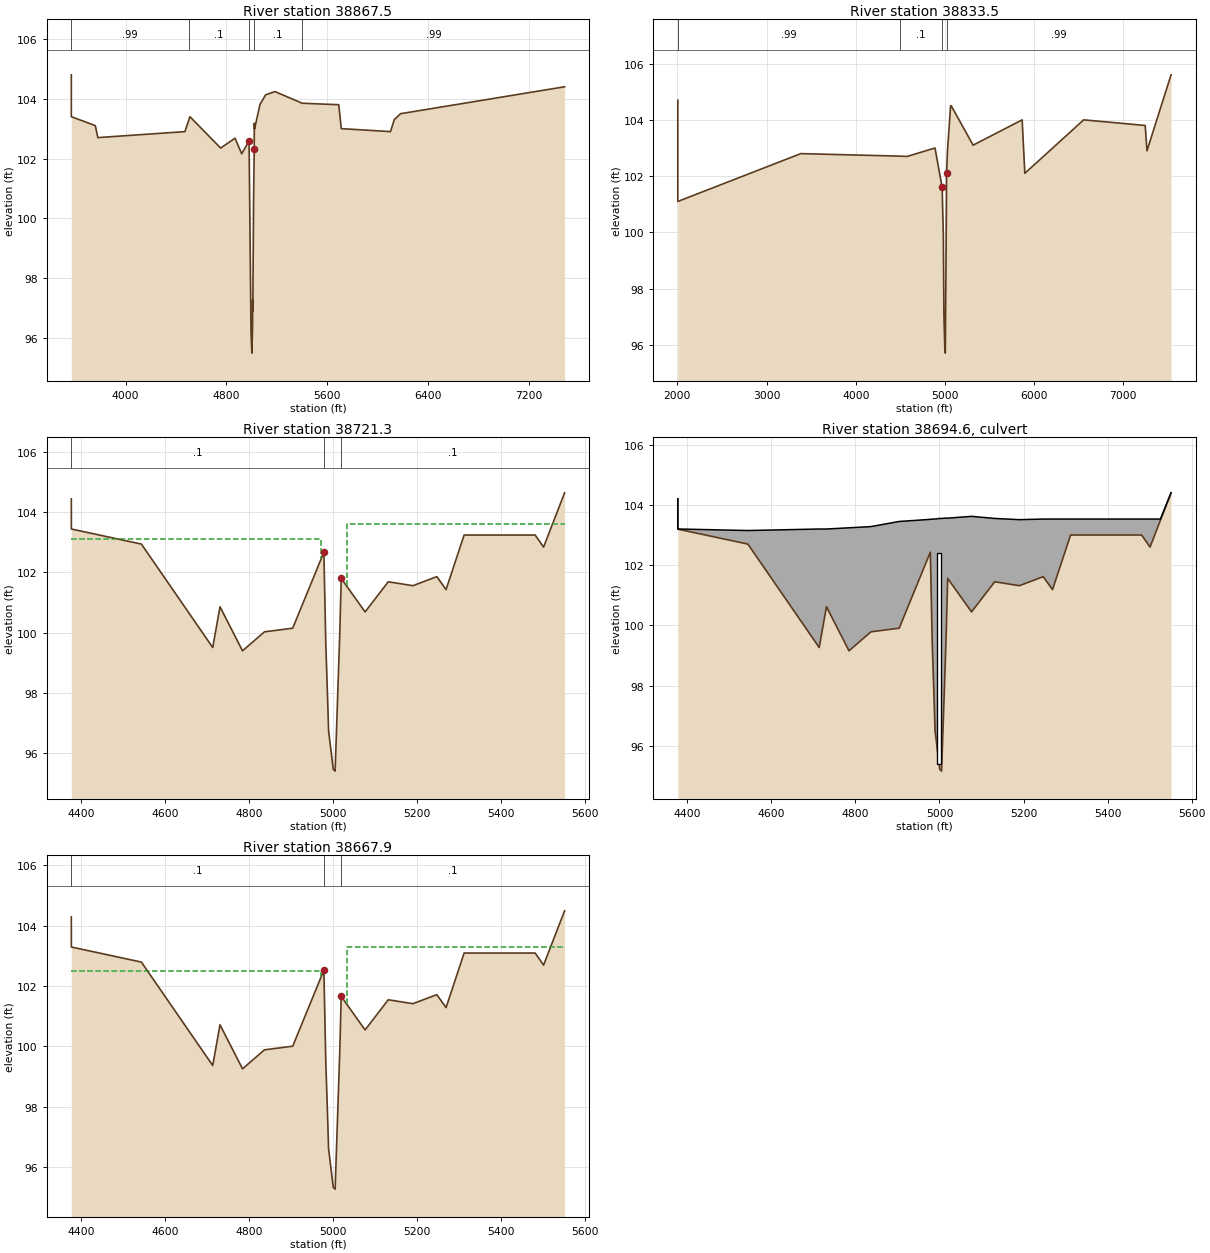
Type RM Length L Ch R = 1 ,38867.5 ,34,34,34
BEGIN DESCRIPTION:
Downstream Section of Bridge/Culvert/Weir
END DESCRIPTION:
XS GIS Cut Line= 6
      3055450.31     13872339.31      3054392.82     13872312.82
      3054260.18      13872554.2      3054245.75     13872743.03
       3054033.5     13872929.23      3051947.93      13873212.2
#Sta/Elev= 30
  3570.3   104.8  3570.4   103.4  3760.4   103.1  3780.4   102.7  4470.4   102.9
  4499.5  103.26  4510.4   103.4  4753.9  102.35    4868  102.68  4920.2  102.16
  4979.1  102.58  4994.6   96.21  5001.3   95.49  5006.7   96.36  5007.9   97.28
  5008.7    96.9  5014.6  100.48  5020.1  102.33  5020.5  103.18  5022.7  102.99
  5065.6  103.81  5110.3  104.13  5184.4  104.24    5400  103.85    5690   103.8
    5710     103    6100   102.9    6130   103.3    6180   103.5    7480   104.4
#Mann= 5 , 1 , 0
  3570.3     .99       0  4499.5      .1       0  4979.1     .02       0
  5020.1      .1       0    5400     .99       0
#XS Ineff= 2 , 0
       0    4972   102.3    5030       0   102.5
Permanent Ineff=
       F       F
Bank Sta=4979.1,5020.1
XS Rating Curve= 0
Exp/Cntr=.5,.3

Type RM Length L Ch R = 1 ,38833.5 ,72.7,112.2,429.9
BEGIN DESCRIPTION:
Cross Section 38833.5-INTERPOLATED
END DESCRIPTION:
XS GIS Cut Line= 6
      3056974.93     13872304.13       3054402.1       13872277.
      3054233.46     13872539.04      3054201.61     13872717.75
      3053973.36     13872807.99      3051755.23     13872898.41
#Sta/Elev= 25
  2004.9   104.7    2005   101.1    3385   102.8    4500  102.71    4578   102.7
  4889.6     103  4969.6   101.6  4982.9   99.93  4987.7    97.9  4989.5   97.05
  5000.7   95.77  5005.1   95.71  5012.2   98.62  5016.1  100.26  5019.6   102.1
  5029.6   102.9  5064.4   104.5  5071.5   104.5    5317   103.1    5867     104
    5897   102.1    6557     104    7247   103.8    7267   102.9    7537   105.6
#Mann= 4 , 1 , 0
  2004.9     .99       0    4500      .1       0  4969.6     .04       0
  5019.6     .99       0
Bank Sta=4969.6,5019.6
XS Rating Curve= 0
Exp/Cntr=.5,.3

Type RM Length L Ch R = 1 ,38721.3 ,53.4,53.4,53.4
BEGIN DESCRIPTION:
Upstream Section of Bridge/Culvert/Weir
END DESCRIPTION:
XS GIS Cut Line= 6
       3054462.9      13872233.5      3054387.17     13872233.08
      3054201.88     13872564.07      3054191.66     13872603.02
      3054189.38     13872637.27      3053545.82     13872621.09
#Sta/Elev= 25
  4377.5  104.44  4377.6  103.44  4544.2  102.94  4713.9   99.51  4731.2  100.86
  4784.8    99.4    4837  100.03  4904.2  100.15  4978.3  102.67  4982.9   99.63
  4987.7    97.6  4989.5   96.75  5000.7   95.47  5005.1   95.41  5016.1   99.96
  5019.6   101.8  5076.4  100.69  5131.5  101.69  5190.1  101.56    5247  101.86
    5269  101.43    5312  103.24    5481  103.24    5501  102.84    5551  104.64
#Mann= 3 , 1 , 0
  4377.5      .1       0  4978.3     .04       0  5019.6      .1       0
#XS Ineff= 2 , 0
       0    4972   103.1    5033       0   103.6
Permanent Ineff=
       F       F
Bank Sta=4978.3,5019.6
XS Rating Curve= 0
Exp/Cntr=.5,.3

Type RM Length L Ch R = 2 ,38694.6 ,,,
BEGIN DESCRIPTION:
TANNER AVENUE
Structure ID: W67-16
END DESCRIPTION:
Bridge Culvert--1,0,-1,-1, 0
Deck Dist Width WeirC Skew NumUp NumDn MinLoCord MaxHiCord MaxSubmerge Is_Ogee
10,33.4,3,0, 35, 35, , , .95, 0, 1,1,,
  4377.5  4377.6  4379.5  4544.2  4713.9  4730.6  4731.2  4784.8  4836.3    4837
  4904.1  4904.2  4978.3  4982.9  4987.7  4989.5  5000.7  5005.1  5012.2  5016.1
  5019.6  5076.4  5076.8  5131.5  5131.6    5190  5190.1    5247  5247.3    5269
    5312    5481    5501  5525.7    5551
   104.2   103.2   103.2  103.15   103.2   103.2   103.2  103.24  103.28  103.28
  103.45  103.45  103.52  103.53  103.53  103.53  103.55  103.55  103.56  103.56
  103.56  103.62  103.62  103.55  103.55  103.51  103.51  103.53  103.53  103.53
  103.53  103.53  103.53  103.53   104.4
   104.2   103.2  103.19   102.7   99.27  100.57  100.62   99.16   99.78   99.79
   99.91   99.91  102.43   99.39   97.36   96.51   95.23   95.17   98.08   99.72
  101.56  100.45  100.46  101.45  101.45  101.32  101.32  101.62  101.61  101.19
     103     103   102.6  103.49   104.4
  4377.5  4377.6  4379.5  4544.2  4713.9  4730.6  4731.2  4784.8  4836.3    4837
  4904.1  4904.2  4978.3  4982.9  4987.7  4989.5  5000.7  5005.1  5012.2  5016.1
  5019.6  5076.4  5076.8  5131.5  5131.6    5190  5190.1    5247  5247.3    5269
    5312    5481    5501  5525.7    5551
   104.2   103.2   103.2  103.15   103.2   103.2   103.2  103.24  103.28  103.28
  103.45  103.45  103.52  103.53  103.53  103.53  103.55  103.55  103.56  103.56
  103.56  103.62  103.62  103.55  103.55  103.51  103.51  103.53  103.53  103.53
  103.53  103.53  103.53  103.53   104.4
  104.11  103.11   103.1  102.61   99.18  100.48  100.53   99.07   99.69    99.7
   99.82   99.82  102.34    99.3   97.27   96.42   95.14   95.08   97.99   99.63
  101.47  100.36  100.37  101.36  101.36  101.23  101.23  101.53  101.52   101.1
  102.91  102.91  102.51   103.4  104.31
BR Coef= 1 , 0 , 0 ,1.25, 0 ,,,.8,-1,2,0,
WSPro=,,,, 1 ,,,, 0 ,,,, 0 ,,,,-1 ,-1 ,-1 , 0 , 0 , 0 , 0 , 0
Culvert=2,7,10,33.4,.015,.5,1,8,1,95.39,4999.5,94.83,4999.5,Culvert #1  , 0 ,10
Culvert Bottom n=.015
BR U #Sta/Elev= 35
  4377.5   104.2  4377.6   103.2  4379.5  103.19  4544.2   102.7  4713.9   99.27
  4730.6  100.57  4731.2  100.62  4784.8   99.16  4836.3   99.78    4837   99.79
  4904.1   99.91  4904.2   99.91  4978.3  102.43  4982.9   99.39  4987.7   97.36
  4989.5   96.51  5000.7   95.23  5005.1   95.17  5012.2   98.08  5016.1   99.72
  5019.6  101.56  5076.4  100.45  5076.8  100.46  5131.5  101.45  5131.6  101.45
    5190  101.32  5190.1  101.32    5247  101.62  5247.3  101.61    5269  101.19
    5312     103    5481     103    5501   102.6  5525.7  103.49    5551   104.4
BR U #Mann= 3
  4377.5      .1  4978.3     .04  5019.6      .1
BR U Banks=4978.3,5019.6
BR D #Sta/Elev= 35
  4377.5  104.11  4377.6  103.11  4379.5   103.1  4544.2  102.61  4713.9   99.18
  4730.6  100.48  4731.2  100.53  4784.8   99.07  4836.3   99.69    4837    99.7
  4904.1   99.82  4904.2   99.82  4978.3  102.34  4982.9    99.3  4987.7   97.27
  4989.5   96.42  5000.7   95.14  5005.1   95.08  5012.2   97.99  5016.1   99.63
  5019.6  101.47  5076.4  100.36  5076.8  100.37  5131.5  101.36  5131.6  101.36
    5190  101.23  5190.1  101.23    5247  101.53  5247.3  101.52    5269   101.1
    5312  102.91    5481  102.91    5501  102.51  5525.7   103.4    5551  104.31
BR D #Mann= 3
  4377.5      .1  4978.3     .04  5019.6      .1
BR D Banks=4978.3,5019.6
BC Design=,, 0 ,, 0 ,,,,,,
BC HTab HWMax=104.64

Type RM Length L Ch R = 1 ,38667.9 ,27.1,27.1,27.1
BEGIN DESCRIPTION:
Downstream Section of Bridge/Culvert/Weir
END DESCRIPTION:
XS GIS Cut Line= 6
      3054465.14     13872180.15      3054389.41     13872179.72
      3054204.12     13872510.71       3054193.9     13872549.66
      3054191.62     13872583.91      3053548.06     13872567.74
#Sta/Elev= 25
  4377.5  104.29  4377.6  103.29  4544.2  102.79  4713.9   99.36  4731.2  100.71
  4784.8   99.25    4837   99.88  4904.2     100  4978.3  102.52  4982.9   99.48
  4987.7   97.45  4989.5    96.6  5000.7   95.32  5005.1   95.26  5016.1   99.81
  5019.6  101.65  5076.4  100.54  5131.5  101.54  5190.1  101.41    5247  101.71
    5269  101.28    5312  103.09    5481  103.09    5501  102.69    5551  104.49
#Mann= 3 , 1 , 0
  4377.5      .1       0  4978.3     .04       0  5019.6      .1       0
#XS Ineff= 2 , 0
       0    4972   102.5    5033       0   103.3
Permanent Ineff=
       F       F
Bank Sta=4978.3,5019.6
XS Rating Curve= 0
Exp/Cntr=.5,.3