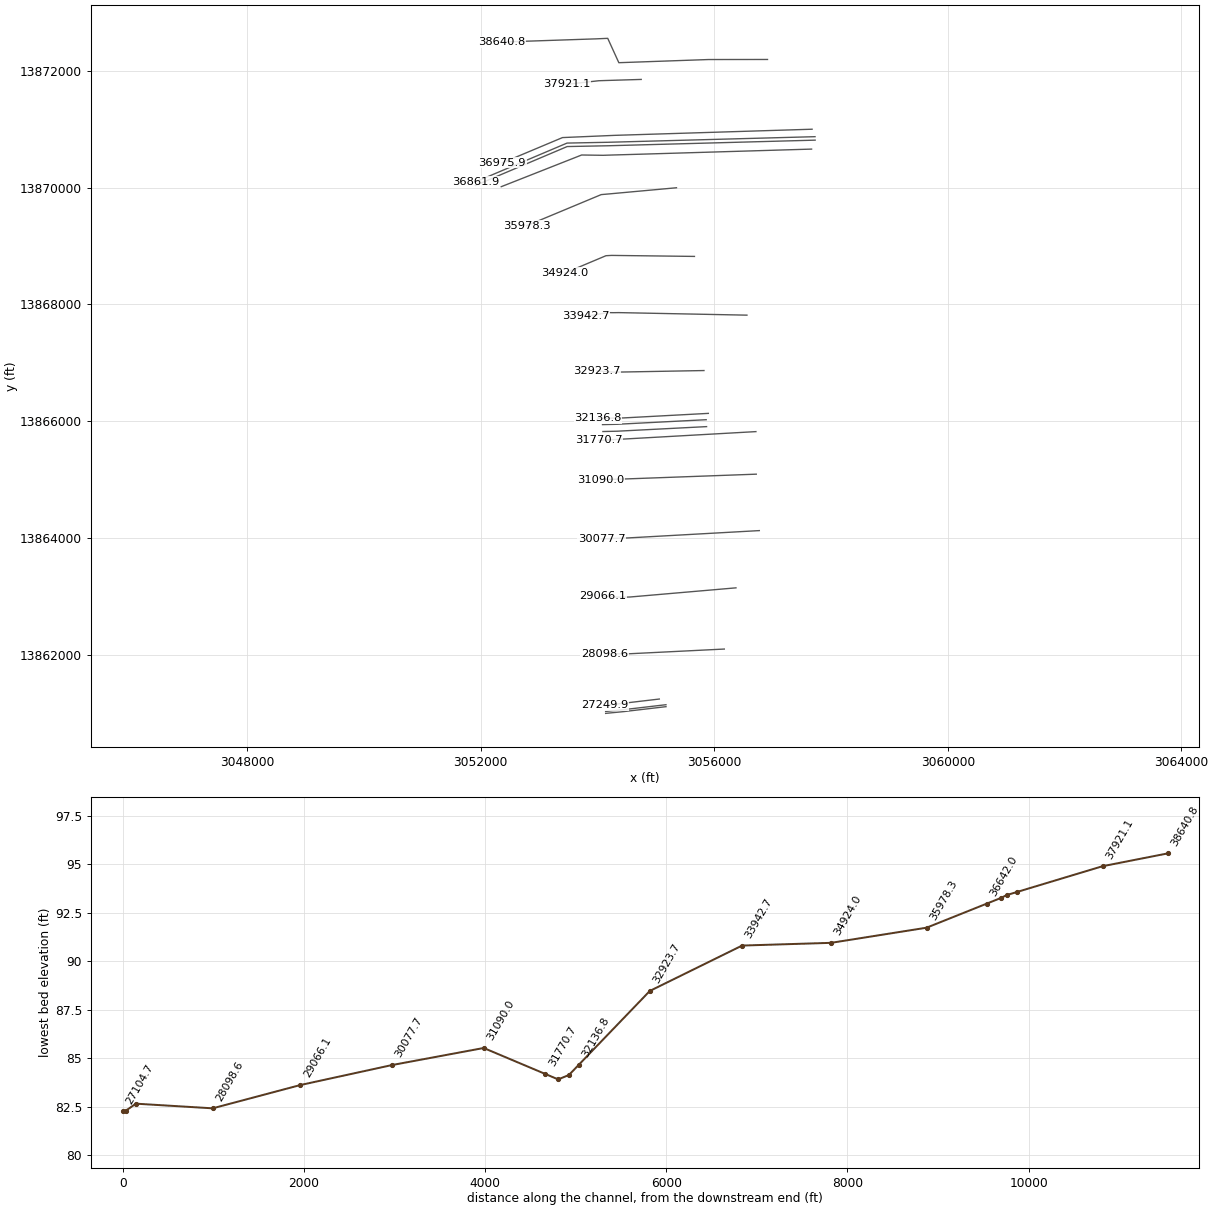
HEC-RAS study W167-00-00pp.prj: W167-00-00

--- W167-00-00pp.g01 (geometry) --- (continued)

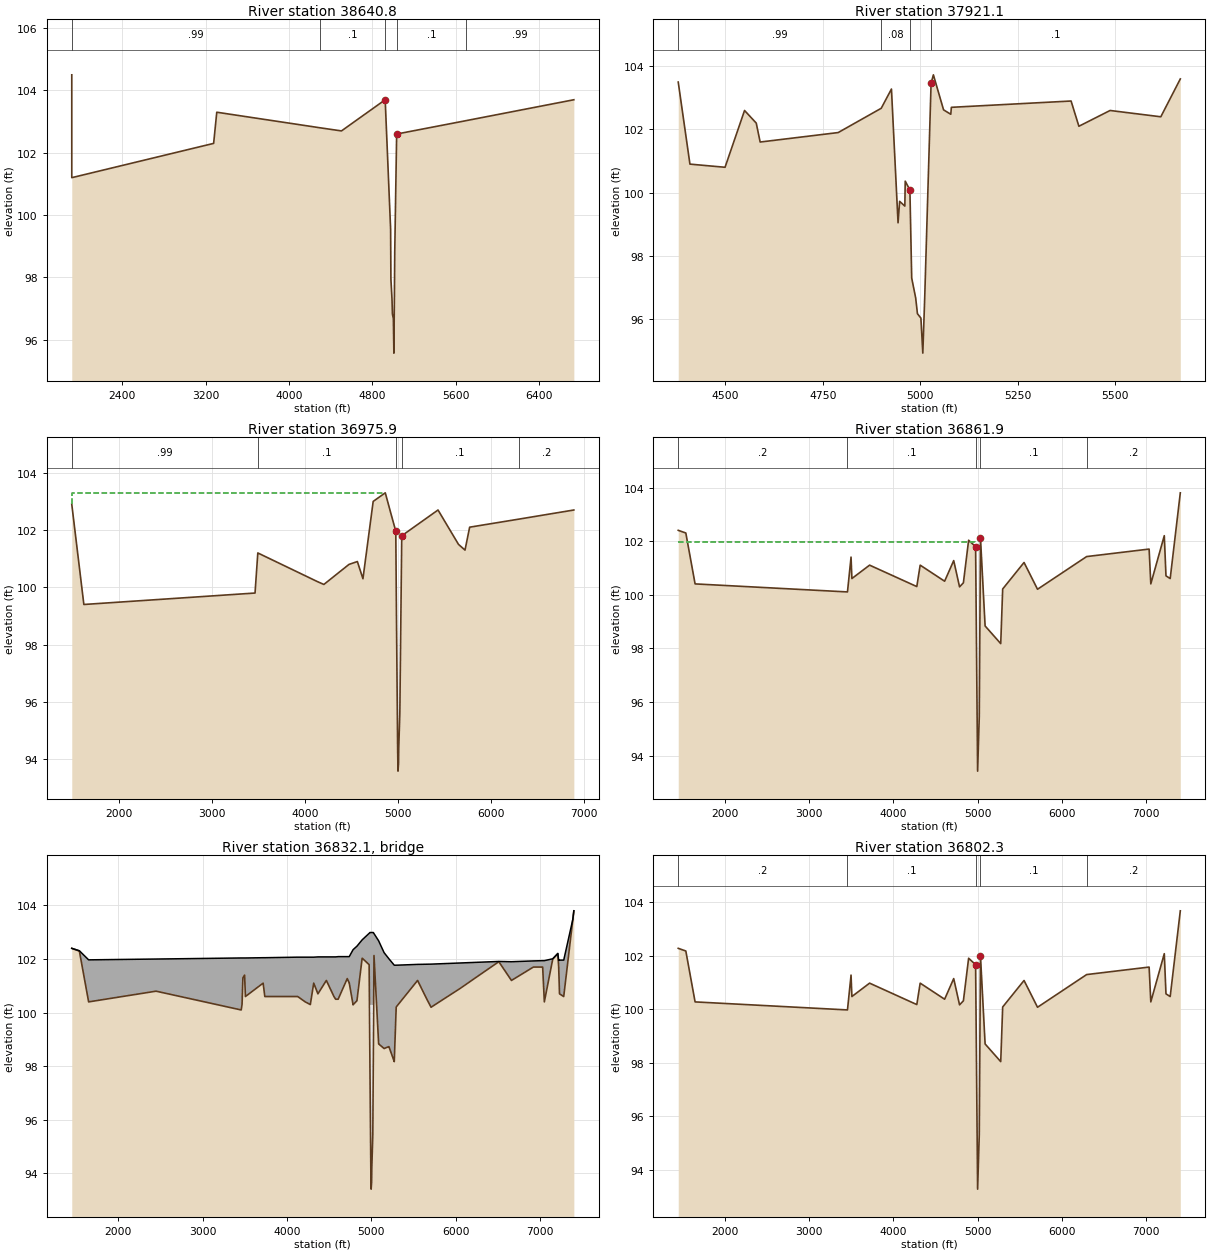
Type RM Length L Ch R = 1 ,38640.8 ,716,719.7,725.2
BEGIN DESCRIPTION:
Cross Section 38640.8-INTERPOLATED
END DESCRIPTION:
XS GIS Cut Line= 6
      3056911.39     13872194.79      3055901.38     13872193.71
      3054365.29     13872139.49      3054175.07     13872556.73
      3053978.67     13872547.89      3052366.84     13872493.41
#Sta/Elev= 18
  1917.5   104.5  1917.6   101.2  3278.1   102.3  3308.1   103.3  4299.6   102.8
    4504   102.7  4923.2   103.7  4975.2   99.56  4978.1   97.95  4988.3   97.32
  4992.8   96.82  5001.7   96.68  5006.6   95.57  5011.6   97.38  5014.9   98.81
  5033.2   102.6  5699.6  103.03  6732.5   103.7
#Mann= 5 , 1 , 0
  1917.5     .99       0  4299.6      .1       0  4923.2     .04       0
  5033.2      .1       0  5699.6     .99       0
Bank Sta=4923.2,5033.2
XS Rating Curve= 0
Exp/Cntr=.3,.1

Type RM Length L Ch R = 1 ,37921.1 ,985.2,945.2,940.4
BEGIN DESCRIPTION:
Cross Section 37921.1
END DESCRIPTION:
XS GIS Cut Line= 4
      3054748.55     13871853.01      3054128.59     13871834.22
      3054021.81     13871830.63      3053465.25     13871768.47
#Sta/Elev= 30
  4379.6   103.5  4409.6   100.9  4499.6   100.8  4549.6   102.6  4579.6   102.2
  4589.6   101.6  4789.6   101.9    4900  102.67  4926.2  103.28  4943.1   99.04
  4947.2   99.72  4960.5   99.57  4961.5  100.36  4973.5  100.08  4978.1   97.29
  4988.3   96.66  4992.8   96.16  5001.7   96.02  5006.6   94.91  5011.6   96.72
  5027.8  103.46  5033.7  103.73  5059.8  102.62  5078.3  102.48  5079.8   102.7
  5386.7   102.9  5406.7   102.1  5486.7   102.6  5616.7   102.4  5666.7   103.6
#Mann= 4 , 1 , 0
  4379.6     .99       0    4900     .08       0  4973.5     .04       0
  5027.8      .1       0
#XS Ineff= 2 , 0
       0                  5386.7       0   102.9
Permanent Ineff=
       F       F
Bank Sta=4973.5,5027.8
XS Rating Curve= 0
Exp/Cntr=.3,.1

Type RM Length L Ch R = 1 ,36975.9 ,114.4,114,113.2
BEGIN DESCRIPTION:
Cross Section 36975.9-INTERPOLATED
END DESCRIPTION:
XS GIS Cut Line= 4
      3057675.15     13871000.33       3054289.8     13870895.08
      3053400.55     13870857.18      3052368.04     13870423.37
#Sta/Elev= 28
  1491.1   102.9  1621.1    99.4  3461.1    99.8    3491   101.2  3491.1   101.2
  4131.1   100.2  4201.1   100.1  4471.1   100.8  4561.1   100.9  4621.1   100.3
  4731.1     103  4861.1   103.3  4928.1   102.5  4974.1  101.96  4980.4   99.39
  4994.1   94.34    4996   93.95  4997.9   93.58  5003.5   93.84  5005.8   94.37
  5017.7   95.62  5038.1   101.8  5428.1   102.7  5648.1   101.5  5718.1   101.3
  5768.1   102.1  6294.9  102.38  6888.1   102.7
#Mann= 5 , 1 , 0
  1491.1     .99       0  3491.1      .1       0  4974.1     .04       0
  5038.1      .1       0  6294.9      .2       0
#XS Ineff= 2 , 0
       0  4861.1   103.3  5428.1       0   102.7
Permanent Ineff=
       F       F
Bank Sta=4974.1,5038.1
XS Rating Curve= 0
Exp/Cntr=.5,.3

Type RM Length L Ch R = 1 ,36861.9 ,59.6,59.6,59.6
BEGIN DESCRIPTION:
Upstream Section of Bridge/Culvert/Weir
END DESCRIPTION:
XS GIS Cut Line= 4
       3057725.1     13870872.63      3054174.11     13870776.51
      3053478.67     13870763.02      3051906.16     13870096.48
#Sta/Elev= 30
  1446.6  102.41  1536.6  102.31  1646.6  100.41  3454.2  100.11  3496.6  101.41
  3506.6  100.61  3716.6  101.11  4276.6  100.31  4316.6  101.11  4606.6  100.51
  4714.4  101.28  4783.7   100.3  4829.3  100.45  4891.3  102.04  4974.1   101.8
  4997.9   93.42  5017.7   95.46  5031.7  102.14  5086.8   98.84  5272.2   98.18
  5295.3  100.22  5548.7  101.21  5708.7  100.21  6291.2  101.43  7032.4  101.71
  7052.4  100.41  7212.4  102.21  7232.4  100.71  7282.4  100.61  7402.4  103.81
#Mann= 5 , 1 , 0
  1446.6      .2       0  3454.2      .1       0  4974.1     .04       0
  5031.7      .1       0  6291.2      .2       0
#XS Ineff= 2 , 0
       0    4972  101.97    5033       0   101.8
Permanent Ineff=
       F       F
Bank Sta=4974.1,5031.7
XS Rating Curve= 0
Exp/Cntr=.5,.3

Type RM Length L Ch R = 3 ,36832.1 ,,,
BEGIN DESCRIPTION:
BRITTMORE PARK
Structure ID: W67-15
END DESCRIPTION:
Bridge Culvert--1,0,-1,-1, 0
Deck Dist Width WeirC Skew NumUp NumDn MinLoCord MaxHiCord MaxSubmerge Is_Ogee
10,39.6,2.6,0, 50, 50, , , .95, 0, 1,1,,
  1446.6  1536.6  1646.6  2446.6  3454.2  3466.6  3476.6  3496.6  3506.6  3716.6
  3736.6  4126.6  4276.6  4316.6  4366.6  4466.6  4556.6  4576.6  4606.6  4714.4
  4737.9  4783.7  4829.3  4892.3  4974.1  4980.4 4982.21  4982.3 5023.59  5023.7
  5031.7  5086.8  5151.2  5208.6  5272.2  5295.3  5548.7  5708.7  6512.4  6662.4
  6922.4  7032.4  7052.4  7152.4  7212.4  7222.4  7232.4  7282.4  7390.2  7402.4
   102.4  102.31  101.97     102  102.04  102.04  102.04  102.04  102.04  102.05
  102.05  102.07  102.07  102.07  102.08  102.08  102.08  102.08  102.09  102.09
  102.09  102.35  102.48  102.72  102.96  102.98  102.99  102.99  102.99  102.99
  102.95  102.68  102.24  102.01  101.77  101.77   101.8  101.81  101.91   101.9
  101.93  101.94  101.94  102.01  102.21  101.95  101.96  101.96  103.48   103.8
   102.4   102.3   100.4   100.8   100.1   100.3   101.3   101.4   100.6   101.1
   100.6   100.6   100.3   101.1   100.7   101.2   100.6   100.5   100.5  101.27
  101.11  100.29  100.44  102.03  101.79   99.22   98.55  100.29  100.29   98.31
  102.13   98.83   98.66   98.73   98.17  100.21   101.2   100.2   101.9   101.2
   101.7   101.7   100.4     102   102.2   101.7   100.7   100.6  103.47   103.8
  1446.6  1536.6  1646.6  2446.6  3454.2  3466.6  3476.6  3496.6  3506.6  3716.6
  3736.6  4126.6  4276.6  4316.6  4366.6  4466.6  4556.6  4576.6  4606.6  4714.4
  4737.9  4783.7  4829.3  4892.3  4974.1  4980.4 4982.21  4982.3 5023.59  5023.7
  5031.7  5086.8  5151.2  5208.6  5272.2  5295.3  5548.7  5708.7  6512.4  6662.4
  6922.4  7032.4  7052.4  7152.4  7212.4  7222.4  7232.4  7282.4  7390.2  7402.4
   102.4  102.31  101.97     102  102.04  102.04  102.04  102.04  102.04  102.05
  102.05  102.07  102.07  102.07  102.08  102.08  102.08  102.08  102.09  102.09
  102.09  102.35  102.48  102.72  102.96  102.98  102.99  102.99  102.99  102.99
  102.95  102.68  102.24  102.01  101.77  101.77   101.8  101.81  101.91   101.9
  101.93  101.94  101.94  102.01  102.21  101.95  101.96  101.96  103.48   103.8
  102.29  102.19  100.29  100.69   99.99  100.19  101.19  101.29  100.49  100.99
  100.49  100.49  100.19  100.99  100.59  101.09  100.49  100.39  100.39  101.16
     101  100.18  100.33  101.92  101.68   99.11   98.44  100.18  100.18    98.2
  102.02   98.72   98.55   98.62   98.06   100.1  101.09  100.09  101.79  101.09
  101.59  101.59  100.29  101.89  102.09  101.59  100.59  100.49  103.36  103.69
BR Coef= 1 , 1 , 0 ,1.25, 0 ,,,.8,0,2,0,
WSPro=,,,, 1 ,,,, 0 ,,,, 0 ,,,,-1 ,-1 ,-1 , 0 , 0 , 0 , 0 , 0
BR U #Sta/Elev= 78
  1446.6   102.4  1534.4   102.3  1536.6   102.3  1646.6   100.4  2446.6   100.8
  3454.2   100.1  3456.6   100.1  3466.6   100.3  3476.6   101.3  3496.6   101.4
  3506.6   100.6  3716.6   101.1  3736.6   100.6  4126.6   100.6  4216.6   100.4
  4276.6   100.3  4316.6   101.1  4366.6   100.7  4466.6   101.2  4556.6   100.6
  4576.6   100.5  4606.6   100.5  4714.4  101.27  4737.6  101.11  4737.9  101.11
  4783.7  100.29  4785.9   100.3  4828.7  100.44  4829.3  100.44  4891.3  102.03
  4892.3  102.03  4974.1  101.79  4980.4   99.22 4982.21   98.55  4982.3   98.52
  4982.4   98.48 4983.09   98.23  4983.2   98.19 4983.31   98.15  4994.1   94.17
    4996   93.78  4997.9   93.41  5003.5   93.67  5005.8    94.2  5017.7   95.45
 5022.59   97.78  5022.7   97.84 5022.81   97.89  5023.5   98.22 5023.59   98.26
  5023.7   98.31  5031.7  102.13  5086.8   98.83    5087   98.83  5151.2   98.66
  5152.4   98.66  5208.3   98.73  5208.6   98.73  5272.2   98.17  5272.8   98.22
  5295.3  100.21  5548.7   101.2  5658.7   100.5  5708.7   100.2  6052.4   100.9
  6291.2  101.42  6512.4   101.9  6662.4   101.2  6922.4   101.7  7032.4   101.7
  7052.4   100.4  7152.4     102  7212.4   102.2  7222.4   101.7  7232.4   100.7
  7282.4   100.6  7390.2  103.47  7402.4   103.8
BR U #Mann= 5
  1446.6      .2  3454.2      .1  4974.1     .04  5031.7      .1  6291.2      .2
BR U Banks=4974.1,5031.7
BR D #Sta/Elev= 78
  1446.6  102.29  1534.4  102.19  1536.6  102.19  1646.6  100.29  2446.6  100.69
  3454.2   99.99  3456.6   99.99  3466.6  100.19  3476.6  101.19  3496.6  101.29
  3506.6  100.49  3716.6  100.99  3736.6  100.49  4126.6  100.49  4216.6  100.29
  4276.6  100.19  4316.6  100.99  4366.6  100.59  4466.6  101.09  4556.6  100.49
  4576.6  100.39  4606.6  100.39  4714.4  101.16  4737.6     101  4737.9     101
  4783.7  100.18  4785.9  100.19  4828.7  100.33  4829.3  100.33  4891.3  101.92
  4892.3  101.92  4974.1  101.68  4980.4   99.11 4982.21   98.44  4982.3   98.41
  4982.4   98.37 4983.09   98.12  4983.2   98.08 4983.31   98.04  4994.1   94.06
    4996   93.67  4997.9    93.3  5003.5   93.56  5005.8   94.09  5017.7   95.34
 5022.59   97.67  5022.7   97.73 5022.81   97.78  5023.5   98.11 5023.59   98.15
  5023.7    98.2  5031.7  102.02  5086.8   98.72    5087   98.72  5151.2   98.55
  5152.4   98.55  5208.3   98.62  5208.6   98.62  5272.2   98.06  5272.8   98.11
  5295.3   100.1  5548.7  101.09  5658.7  100.39  5708.7  100.09  6052.4  100.79
  6291.2  101.31  6512.4  101.79  6662.4  101.09  6922.4  101.59  7032.4  101.59
  7052.4  100.29  7152.4  101.89  7212.4  102.09  7222.4  101.59  7232.4  100.59
  7282.4  100.49  7390.2  103.36  7402.4  103.69
BR D #Mann= 5
  1446.6      .2  3454.2      .1  4974.1     .04  5031.7      .1  6291.2      .2
BR D Banks=4974.1,5031.7
BC Design=,, 0 ,, 0 ,,,,,,
BC HTab HWMax=103.81

Type RM Length L Ch R = 1 ,36802.3 ,160.3,160.3,160.3
BEGIN DESCRIPTION:
Downstream Section of Bridge/Culvert/Weir
END DESCRIPTION:
XS GIS Cut Line= 4
      3057727.12     13870813.06      3054176.13     13870716.95
      3053480.69     13870703.46      3051908.19     13870036.91
#Sta/Elev= 30
  1446.6  102.27  1536.6  102.17  1646.6  100.27  3454.2   99.97  3496.6  101.27
  3506.6  100.47  3716.6  100.97  4276.6  100.17  4316.6  100.97  4606.6  100.37
  4714.4  101.14  4783.7  100.16  4829.3  100.31  4891.3   101.9  4974.1  101.66
  4997.9   93.28  5017.7   95.32  5031.7     102  5086.8    98.7  5272.2   98.04
  5295.3  100.08  5548.7  101.07  5708.7  100.07  6291.2  101.29  7032.4  101.57
  7052.4  100.27  7212.4  102.07  7232.4  100.57  7282.4  100.47  7402.4  103.67
#Mann= 5 , 1 , 0
  1446.6      .2       0  3454.2      .1       0  4974.1     .04       0
  5031.7      .1       0  6291.2      .2       0
#XS Ineff= 2 , 0
       0    4972   101.5    5033       0  101.01
Permanent Ineff=
       F       F
Bank Sta=4974.1,5031.7
XS Rating Curve= 0
Exp/Cntr=.5,.3

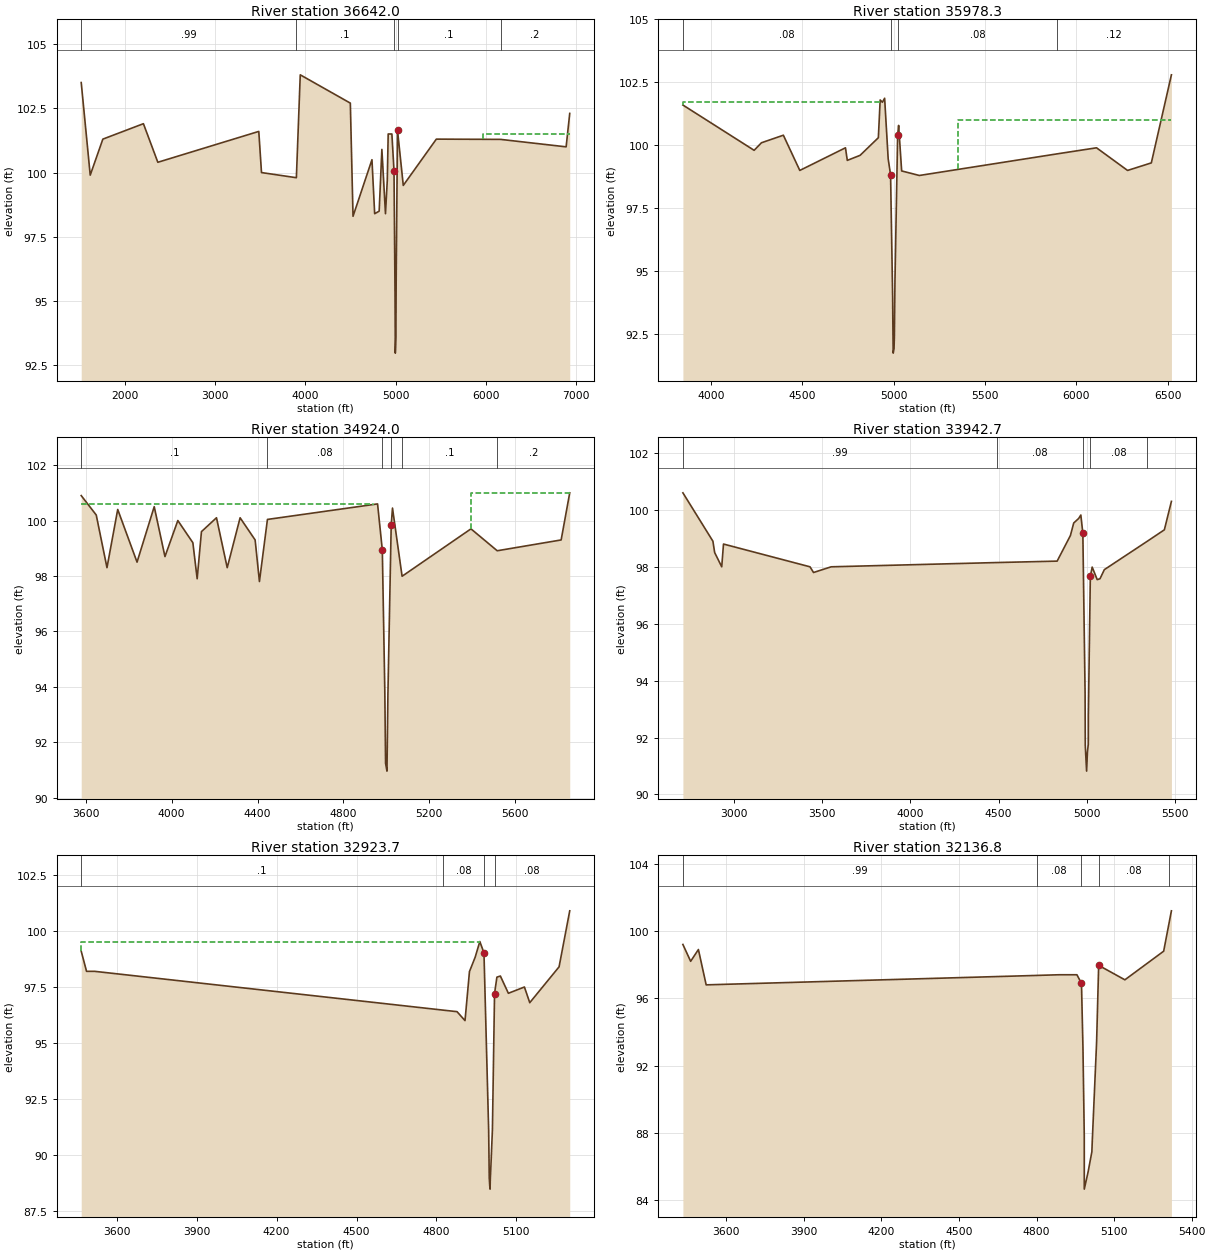
Type RM Length L Ch R = 1 ,36642.0 ,661.9,663.7,805.6
BEGIN DESCRIPTION:
Cross Section 36642.0-INTERPOLATED
END DESCRIPTION:
XS GIS Cut Line= 6
      3057666.19     13870659.94      3054761.95     13870573.16
      3054261.18     13870558.85      3054094.85     13870553.48
      3053728.22     13870558.85      3052351.31     13870016.03
#Sta/Elev= 30
  1512.8   103.5  1612.8    99.9  1752.8   101.3  2202.8   101.9  2362.8   100.4
  3482.8   101.6  3512.8     100  3899.8    99.8  3942.8   103.8  4498.3   102.7
  4528.3    98.3  4738.3   100.5  4768.3    98.4  4818.3    98.5  4848.3   100.9
  4888.3    98.4  4908.3    99.7  4918.3   101.5  4959.3   101.5  4982.9  100.07
  4994.3    95.2  4997.3   92.98  5003.7   93.61  5006.9   95.82  5021.6  101.65
  5085.7    99.5  5452.4   101.3  6164.6  101.29  6892.4     101  6932.4   102.3
#Mann= 5 , 1 , 0
  1512.8     .99       0  3899.8      .1       0  4982.9     .04       0
  5021.6      .1       0  6164.6      .2       0
#XS Ineff= 2 , 0
       0                  5972.4       0   101.5
Permanent Ineff=
       F       F
Bank Sta=4982.9,5021.6
XS Rating Curve= 0
Exp/Cntr=.3,.1

Type RM Length L Ch R = 1 ,35978.3 ,1152.5,1054.3,1051.3
BEGIN DESCRIPTION:
Cross Section 35978.3
END DESCRIPTION:
XS GIS Cut Line= 4
      3055352.28     13869997.84      3054203.23     13869892.83
      3054063.14     13869880.44      3052789.54     13869349.28
#Sta/Elev= 29
    3846   101.6    4236    99.8    4276   100.1    4396   100.4    4486      99
    4736    99.9    4746    99.4    4816    99.6    4916   100.3    4926   101.8
  4938.1  101.71  4950.4  101.87  4969.8   99.46  4982.9   98.83  4994.3   93.96
  4995.3   93.04  4997.3   91.74  5001.8   91.92  5003.7   92.37  5006.9   94.58
  5021.6  100.41    5027  100.79  5043.6   98.98  5140.4    98.8  5895.8   99.66
  6110.4    99.9  6280.4      99  6410.4    99.3  6520.4   102.8
#Mann= 4 , 1 , 0
    3846     .08       0  4982.9     .04       0  5021.6     .08       0
  5895.8     .12       0
#XS Ineff= 2 , 0
       0    4938  101.72    5350       0     101
Permanent Ineff=
       F       F
Bank Sta=4982.9,5021.6
XS Rating Curve= 0
Exp/Cntr=.3,.1

Type RM Length L Ch R = 1 ,34924.0 ,1054,981.3,935.1
BEGIN DESCRIPTION:
Cross Section 34924.0
END DESCRIPTION:
XS GIS Cut Line= 4
      3055660.12     13868821.99      3054241.03     13868839.26
       3054145.2     13868834.15      3053444.81       13868539.
#Sta/Elev= 30
  3578.7   100.9  3648.7   100.2  3698.7    98.3  3748.7   100.4  3838.7    98.5
  3918.7   100.5  3968.7    98.7  4028.7     100  4098.7    99.2  4118.7    97.9
  4138.7    99.6  4208.7   100.1  4258.7    98.3  4318.7   100.1  4388.7    99.3
  4408.7    97.8    4446  100.04  4958.9   100.6    4981   98.94  4992.6   93.88
  4996.2   91.24  5002.7   90.96  5007.1   93.74  5022.4   99.83  5028.4  100.45
  5073.1   97.99  5393.9    99.7  5516.2   98.91  5813.9    99.3  5853.9     101
#Mann= 6 , 1 , 0
  3578.7      .1       0    4446     .08       0    4981     .04       0
  5022.4     .08       0  5073.1      .1       0  5516.2      .2       0
#XS Ineff= 2 , 0
       0  4938.1  100.61    5394       0     101
Permanent Ineff=
       F       F
Bank Sta=4981,5022.4
XS Rating Curve= 0
Exp/Cntr=.3,.1

Type RM Length L Ch R = 1 ,33942.7 ,1028.9,1019,1008.8
BEGIN DESCRIPTION:
Cross Section 33942.7
END DESCRIPTION:
XS GIS Cut Line= 5
      3056559.33     13867816.05      3054364.58     13867859.61
      3054271.07     13867858.39      3054172.54      13867859.7
      3053798.18     13867794.09
#Sta/Elev= 30
  2712.1   100.6  2882.1    98.9  2892.1    98.5  2932.1      98  2942.1    98.8
  3432.1      98  3452.1    97.8  3552.1      98  4492.1   98.15  4832.1    98.2
  4907.3    99.1    4926   99.54  4954.2    99.7  4966.3   99.82  4977.7   99.18
  4990.4   93.57  4991.4   91.74  4993.3   91.49  4998.9   90.82  5003.5   91.48
  5008.6   91.77    5009   92.81  5020.1   97.66  5030.6   97.99    5059   97.55
  5074.8   97.58  5099.4    97.9  5343.2    98.9  5439.4    99.3  5479.4   100.3
#Mann= 5 , 1 , 0
  2712.1     .99       0  4492.1     .08       0  4977.7     .04       0
  5020.1     .08       0  5343.2      .2       0
#XS Ineff= 2 , 0
       0  4966.3   99.82               0
Permanent Ineff=
       F       F
Bank Sta=4977.7,5020.1
XS Rating Curve= 0
Exp/Cntr=.3,.1

Type RM Length L Ch R = 1 ,32923.7 ,878.3,786.9,785.2
BEGIN DESCRIPTION:
Cross Section 32923.7
END DESCRIPTION:
XS GIS Cut Line= 3
      3055823.11     13866867.45      3054290.46     13866839.72
      3053991.34     13866862.69
#Sta/Elev= 26
  3467.1    99.1  3487.1    98.2  3517.1    98.2  4823.8   96.47  4877.1    96.4
  4907.1      96  4923.8   98.19  4945.2   98.83  4962.7   99.53  4978.2   99.02
  4995.8   91.11    4998   88.99  4999.9   88.62  5000.6   88.56  5001.2   88.48
  5001.9   88.91  5004.2    89.5  5009.9   91.13  5017.9   97.21  5026.7   97.94
  5039.8   97.99  5069.8   97.22    5130    97.5    5150    96.8    5260    98.4
    5300   100.9
#Mann= 4 , 1 , 0
  3467.1      .1       0  4823.8     .08       0  4978.2     .04       0
  5017.9     .08       0
#XS Ineff= 2 , 0
       0  4962.7   99.53               0
Permanent Ineff=
       F       F
Bank Sta=4978.2,5017.9
XS Rating Curve= 0
Exp/Cntr=.3,.1

Type RM Length L Ch R = 1 ,32136.8 ,106.1,105.4,102.9
BEGIN DESCRIPTION:
Cross Section 32136.8-INTERPOLATED
END DESCRIPTION:
XS GIS Cut Line= 4
      3055898.03     13866133.91      3054446.04      13866056.2
      3054190.63     13866051.64      3054010.56     13866053.58
#Sta/Elev= 20
  3432.1    99.2  3462.1    98.2  3492.1    98.9  3522.1    96.8    4800   97.36
  4886.2    97.4  4956.2    97.4  4973.8   96.89  4979.5    93.1  4984.6   87.82
  4984.7   84.66  4999.4   85.68    5014   86.88  5015.4   87.45  5032.3   93.39
  5040.3   97.96  5141.7    97.1  5291.7    98.8  5313.2  100.52  5321.7   101.2
#Mann= 5 , 1 , 0
  3432.1     .99       0    4800     .08       0  4973.8     .04       0
  5040.3     .08       0  5313.2      .2       0
Bank Sta=4973.8,5040.3
XS Rating Curve= 0
Exp/Cntr=.5,.3

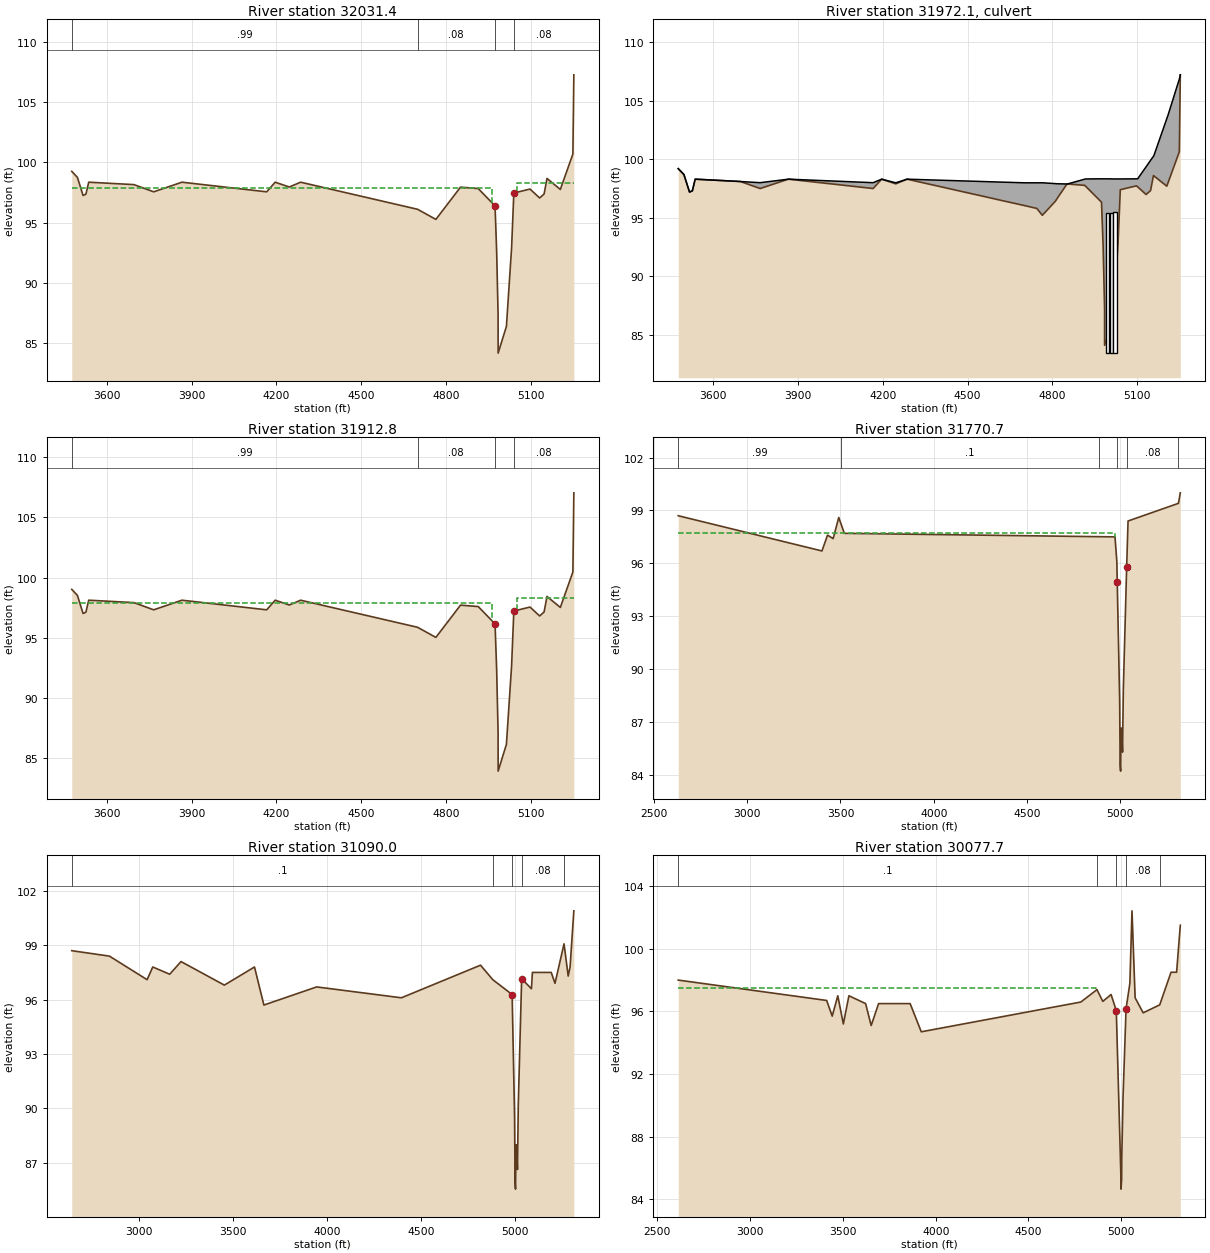
Type RM Length L Ch R = 1 ,32031.4 ,118.6,118.6,118.6
BEGIN DESCRIPTION:
Upstream Section of Bridge/Culvert/Weir
END DESCRIPTION:
XS GIS Cut Line= 4
      3055860.89     13866025.62      3054369.41     13865949.06
      3054340.34     13865947.12      3054085.78     13865941.51
#Sta/Elev= 30
  3475.5   99.25  3495.5   98.75  3515.5   97.25  3525.5   97.35  3535.5   98.35
  3695.5   98.15  3765.5   97.55  3865.5   98.35  4165.5   97.55  4195.5   98.35
  4245.5   97.95  4285.5   98.35  4699.5    96.1  4764.3   95.26  4851.6   97.94
  4914.3   97.82  4973.8   96.38  4979.5   92.59  4984.6   87.31  4984.7   84.15
    5014   86.37  5032.3   92.88  5040.3   97.45  5097.5   97.78  5131.6   97.04
  5147.4   97.37  5157.7   98.66  5204.9   97.75  5249.3  100.69  5252.7  107.27
#Mann= 4 , 1 , 0
  3475.5     .99       0  4699.5     .08       0  4973.8     .04       0
  5040.3     .08       0
#XS Ineff= 2 , 0
       0    4963    97.9    5050       0    98.3
Permanent Ineff=
       F       F
Bank Sta=4973.8,5040.3
XS Rating Curve= 0
Exp/Cntr=.5,.3

Type RM Length L Ch R = 2 ,31972.1 ,,,
BEGIN DESCRIPTION:
CLAY ROAD
Structure ID: W67-13
END DESCRIPTION:
Bridge Culvert--1,0,-1,-1, 0
Deck Dist Width WeirC Skew NumUp NumDn MinLoCord MaxHiCord MaxSubmerge Is_Ogee
10,98.6,3,0, 48, 48, , , .95, 0, 1,1,,
  3475.5  3495.5  3515.5  3525.5  3535.5  3695.4  3695.5  3765.5  3865.5  4165.5
  4195.5  4245.5  4285.5  4699.5  4744.8  4764.3  4766.6    4810  4813.5  4851.6
  4853.6  4914.3  4917.3  4973.8  4979.5 4984.09  4984.2 4984.31  4984.6  4984.7
  4999.4    5014  5015.4  5032.3 5038.09  5038.2 5038.31  5040.3  5097.5  5101.7
  5131.6  5147.4  5157.7  5159.1  5204.9    5209  5249.3  5252.7
    99.2    98.7    97.2    97.3    98.3    98.1    98.1      98    98.3      98
    98.3   97.99    98.3   97.99   97.99   97.99   97.99   97.92   97.91   97.89
   97.89    98.3   98.32   98.33   98.33   98.33   98.33   98.33   98.33   98.33
   98.33   98.32   98.32   98.32   98.32   98.32   98.32   98.32   98.33   98.33
   99.36   99.91  100.26  100.31  103.48  103.76  106.86  107.22
    99.2    98.7    97.2    97.3    98.3    98.1    98.1    97.5    98.3    97.5
    98.3    97.9    98.3   96.05    95.8   95.21   95.27    96.4   96.53   97.89
   97.89   97.77    97.7   96.33   92.54   87.79   87.67   87.56   87.26    84.1
   85.12   86.32   86.89   92.83   96.14    96.2   96.26    97.4   97.73   97.64
   96.99   97.32   98.61   98.58    97.7   97.97  100.64  107.22
  3475.5  3495.5  3515.5  3525.5  3535.5  3695.4  3695.5  3765.5  3865.5  4165.5
  4195.5  4245.5  4285.5  4699.5  4744.8  4764.3  4766.6    4810  4813.5  4851.6
  4853.6  4914.3  4917.3  4973.8  4979.5 4984.09  4984.2 4984.31  4984.6  4984.7
  4999.4    5014  5015.4  5032.3 5038.09  5038.2 5038.31  5040.3  5097.5  5101.7
  5131.6  5147.4  5157.7  5159.1  5204.9    5209  5249.3  5252.7
    99.1    98.6    97.1    97.2    98.2      98      98      98   98.21      98
   98.21   97.99   98.21   97.99   97.99   97.99   97.99   97.92   97.91   97.89
   97.89    98.3   98.32   98.33   98.33   98.33   98.33   98.33   98.33   98.33
   98.33   98.32   98.32   98.32   98.32   98.32   98.32   98.32   98.33   98.33
   99.36   99.91  100.26  100.31  103.48  103.76  106.86  107.12
      99    98.5      97    97.1    98.1    97.9    97.9    97.3    98.1    97.3
    98.1    97.7    98.1   95.85    95.6   95.01   95.07    96.2   96.33   97.69
   97.69   97.57    97.5   96.13   92.34   87.59   87.47   87.36   87.06    83.9
   84.92   86.12   86.69   92.63   95.94      96   96.06    97.2   97.53   97.44
   96.79   97.12   98.41   98.38    97.5   97.77  100.44  107.02
BR Coef= 1 , 0 , 0 ,1.25, 0 ,,,.8,-1,2,0,
WSPro=,,,, 1 ,,,, 0 ,,,, 0 ,,,,-1 ,-1 ,-1 , 0 , 0 , 0 , 0 , 0
Culvert=2,12,12,98.6,.015,.5,1,8,1,83.43,4995.5,82.96,4995.5,Culvert #1  , 0 ,10
Culvert Bottom n=.015
Culvert=2,12,12,98.6,.015,.5,1,8,1,83.45,5008.8,82.93,5008.8,Culvert #2  , 0 ,10
Culvert Bottom n=.015
Culvert=2,12,12,98.6,.015,.5,1,8,1,83.46,5021.3,82.94,5021.3,Culvert #3  , 0 ,10
Culvert Bottom n=.015
BR U #Sta/Elev= 48
  3475.5    99.2  3495.5    98.7  3515.5    97.2  3525.5    97.3  3535.5    98.3
  3695.4    98.1  3695.5    98.1  3765.5    97.5  3865.5    98.3  4165.5    97.5
  4195.5    98.3  4245.5    97.9  4285.5    98.3  4699.5   96.05  4744.8    95.8
  4764.3   95.21  4766.6   95.27    4810    96.4  4813.5   96.53  4851.6   97.89
  4853.6   97.89  4914.3   97.77  4917.3    97.7  4973.8   96.33  4979.5   92.54
 4984.09   87.79  4984.2   87.67 4984.31   87.56  4984.6   87.26  4984.7    84.1
  4999.4   85.12    5014   86.32  5015.4   86.89  5032.3   92.83 5038.09   96.14
  5038.2    96.2 5038.31   96.26  5040.3    97.4  5097.5   97.73  5101.7   97.64
  5131.6   96.99  5147.4   97.32  5157.7   98.61  5159.1   98.58  5204.9    97.7
    5209   97.97  5249.3  100.64  5252.7  107.22
BR U #Mann= 4
  3475.5     .99  4699.5     .08  4973.8     .04  5040.3     .08
BR U Banks=4973.8,5040.3
BR D #Sta/Elev= 48
  3475.5      99  3495.5    98.5  3515.5      97  3525.5    97.1  3535.5    98.1
  3695.4    97.9  3695.5    97.9  3765.5    97.3  3865.5    98.1  4165.5    97.3
  4195.5    98.1  4245.5    97.7  4285.5    98.1  4699.5   95.85  4744.8    95.6
  4764.3   95.01  4766.6   95.07    4810    96.2  4813.5   96.33  4851.6   97.69
  4853.6   97.69  4914.3   97.57  4917.3    97.5  4973.8   96.13  4979.5   92.34
 4984.09   87.59  4984.2   87.47 4984.31   87.36  4984.6   87.06  4984.7    83.9
  4999.4   84.92    5014   86.12  5015.4   86.69  5032.3   92.63 5038.09   95.94
  5038.2      96 5038.31   96.06  5040.3    97.2  5097.5   97.53  5101.7   97.44
  5131.6   96.79  5147.4   97.12  5157.7   98.41  5159.1   98.38  5204.9    97.5
    5209   97.77  5249.3  100.44  5252.7  107.02
BR D #Mann= 4
  3475.5     .99  4699.5     .08  4973.8     .04  5040.3     .08
BR D Banks=4973.8,5040.3
BC Design=,, 0 ,, 0 ,,,,,,
BC HTab HWMax=107.27

Type RM Length L Ch R = 1 ,31912.8 ,142.1,142.1,142.1
BEGIN DESCRIPTION:
Downstream Section of Bridge/Culvert/Weir
END DESCRIPTION:
XS GIS Cut Line= 4
      3055867.74     13865907.22      3054376.27     13865830.66
       3054347.2     13865828.72      3054092.63      13865823.1
#Sta/Elev= 30
  3475.5   99.02  3495.5   98.52  3515.5   97.02  3525.5   97.12  3535.5   98.12
  3695.5   97.92  3765.5   97.32  3865.5   98.12  4165.5   97.32  4195.5   98.12
  4245.5   97.72  4285.5   98.12  4699.5   95.87  4764.3   95.03  4851.6   97.71
  4914.3   97.59  4973.8   96.15  4979.5   92.36  4984.6   87.08  4984.7   83.92
    5014   86.14  5032.3   92.65  5040.3   97.22  5097.5   97.55  5131.6   96.81
  5147.4   97.14  5157.7   98.43  5204.9   97.52  5249.3  100.46  5252.7  107.04
#Mann= 4 , 1 , 0
  3475.5     .99       0  4699.5     .08       0  4973.8     .04       0
  5040.3     .08       0
#XS Ineff= 2 , 0
       0    4963    97.9    5050       0    98.3
Permanent Ineff=
       F       F
Bank Sta=4973.8,5040.3
XS Rating Curve= 0
Exp/Cntr=.5,.3

Type RM Length L Ch R = 1 ,31770.7 ,1044.5,680.7,680.5
BEGIN DESCRIPTION:
Cross Section 31770.7-INTERPOLATED
END DESCRIPTION:
XS GIS Cut Line= 2
      3056712.71     13865821.61      3054026.96     13865670.41
#Sta/Elev= 27
  2630.9    98.7  3400.9    96.7  3430.9    97.6  3460.9    97.4  3490.9    98.6
  3500.9    98.3  3520.9    97.7  4883.9   97.51  4970.9    97.5  4980.9    96.1
    4983   94.94    4996   88.21  4998.5   84.57  4999.6   84.36  5000.6   84.28
    5001    84.2  5001.5   84.58  5002.6   85.67  5005.6   86.65  5007.7   86.27
  5011.3   85.28  5015.6   88.84  5033.5   95.81  5040.9    98.4    5310    99.4
  5310.9    99.4  5320.9     100
#Mann= 6 , 1 , 0
  2630.9     .99       0  3500.9      .1       0  4883.9     .08       0
    4983     .04       0  5033.5     .08       0    5310      .2       0
#XS Ineff= 2 , 0
       0  4970.9    97.7               0
Permanent Ineff=
       F       F
Bank Sta=4983,5033.5
XS Rating Curve= 0
Exp/Cntr=.3,.1

Type RM Length L Ch R = 1 ,31090.0 ,1035.2,1012.3,1011.6
BEGIN DESCRIPTION:
Cross Section 31090.0
END DESCRIPTION:
XS GIS Cut Line= 4
      3056718.92     13865092.86      3054508.11      13865012.1
      3054365.09     13865007.85       3054055.2     13864998.54
#Sta/Elev= 30
  2645.2    98.7  2845.2    98.4  3045.2    97.1  3075.2    97.8  3165.2    97.4
  3225.2    98.1  3455.2    96.8  3615.2    97.8  3665.2    95.7  3945.2    96.7
  4395.2    96.1  4815.2    97.9  4880.4    97.1    4983   96.28    4996   89.55
  4998.5   85.91    5001   85.54  5002.6   87.01  5005.6   87.99  5011.3   86.62
  5015.6   90.18  5033.5   97.15  5085.4    96.6  5090.6    97.5  5190.6    97.5
  5210.6    96.9  5258.6   99.08  5280.6    97.3  5290.6    97.8  5310.6   100.9
#Mann= 5 , 1 , 0
  2645.2      .1       0  4880.4     .08       0    4983     .04       0
  5033.5     .08       0  5258.6      .2       0
#XS Ineff= 2 , 0
       0  4815.2    97.9               0
Permanent Ineff=
       F       F
Bank Sta=4983,5033.5
XS Rating Curve= 0
Exp/Cntr=.3,.1

Type RM Length L Ch R = 1 ,30077.7 ,999.4,1011.6,1002.5
BEGIN DESCRIPTION:
Cross Section 30077.7
END DESCRIPTION:
XS GIS Cut Line= 4
      3056770.99     13864126.44      3054522.15     13864001.01
      3054388.35     13863995.96      3054068.57     13863984.81
#Sta/Elev= 30
  2612.2      98  3412.2    96.7  3442.2    95.7  3472.2      97  3502.2    95.2
  3532.2      97  3622.2    96.5  3652.2    95.1  3692.2    96.5  3862.2    96.5
  3922.2    94.7  4782.2    96.6  4869.1   97.39  4900.7   96.64  4945.2   97.08
  4973.4   96.05  4997.5   85.78  4998.7   84.66  5002.1   85.27  5002.8   86.67
  5009.7   90.51  5025.9   96.16  5046.5   97.79    5058  102.42  5074.9   96.87
  5118.2   95.91  5207.4   96.42  5268.4    98.5  5298.4    98.5  5318.4   101.5
#Mann= 5 , 1 , 0
  2612.2      .1       0  4869.1     .08       0  4973.4     .04       0
  5025.9     .08       0  5207.4      .2       0
#XS Ineff= 2 , 0
       0  4864.6    97.5               0
Permanent Ineff=
       F       F
Bank Sta=4973.4,5025.9
XS Rating Curve= 0
Exp/Cntr=.3,.1

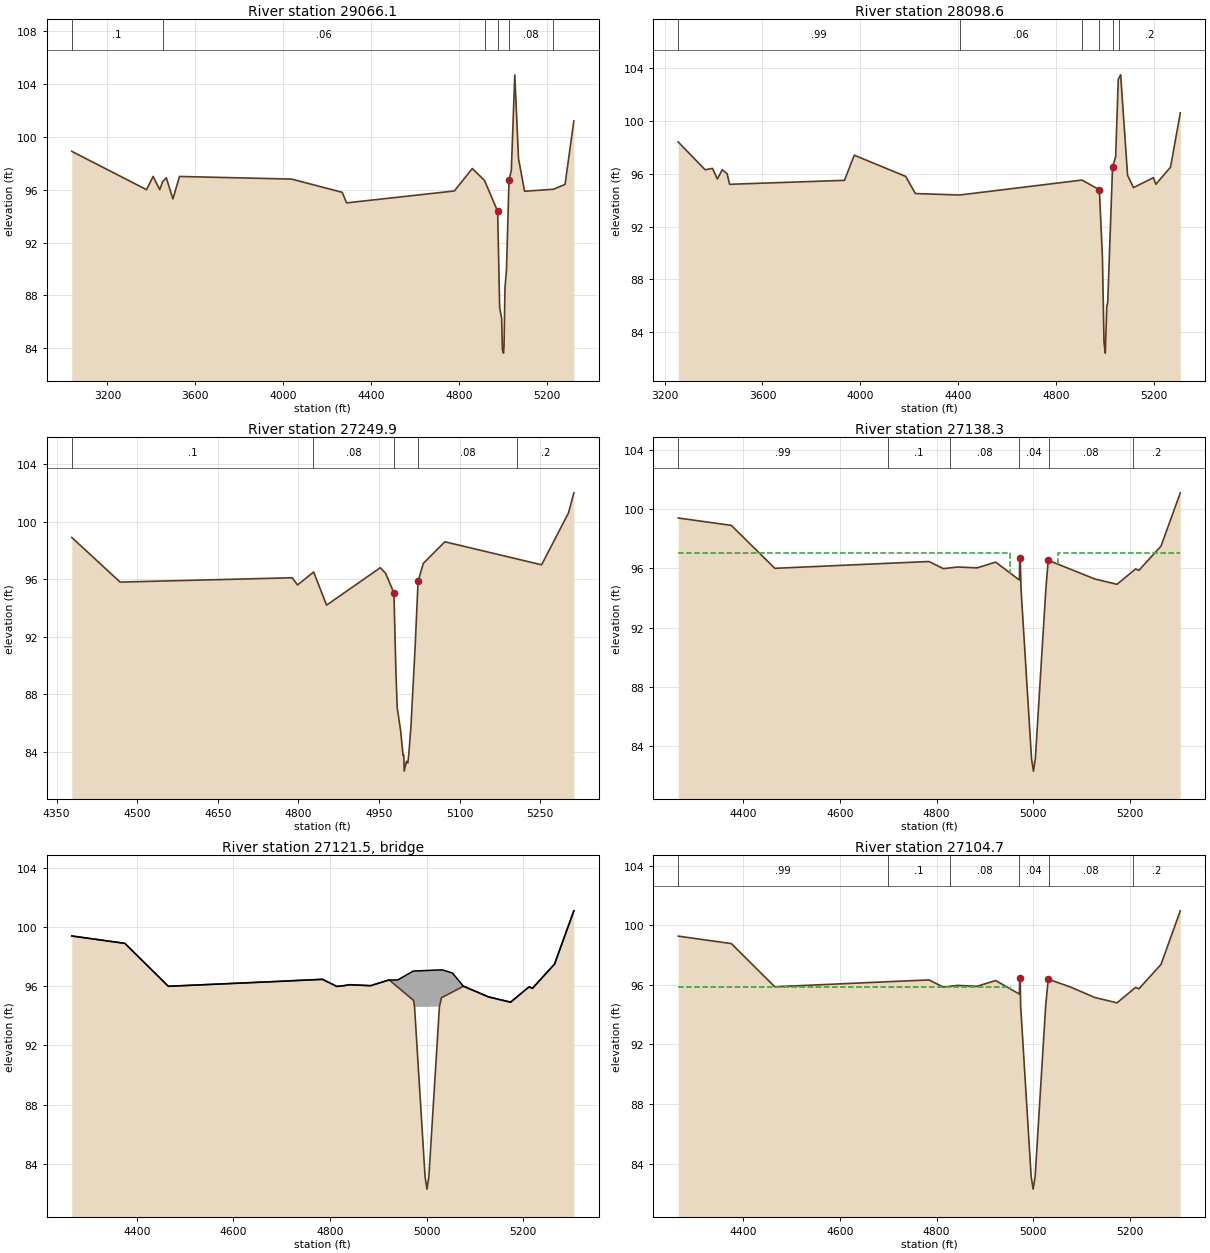
Type RM Length L Ch R = 1 ,29066.1 ,982.3,967.5,966.9
BEGIN DESCRIPTION:
Cross Section 29066.1
END DESCRIPTION:
XS GIS Cut Line= 4
      3056371.25     13863146.13      3054556.32     13862989.24
      3054414.52     13862985.04       3054094.8     13862999.37
#Sta/Elev= 30
  3037.9    98.9  3377.9      96  3407.9      97  3437.9      96  3451.4   96.61
  3467.9    96.9  3497.9    95.3  3527.9      97  4037.9    96.8  4267.9    95.8
  4287.9      95  4777.9    95.9  4859.6    97.6  4915.2    96.7    4975   94.36
    4984    87.1  4993.1   86.25  4996.5   83.89  5001.6   83.63  5003.9   84.12
  5008.3   88.57  5015.2   89.98  5026.6   96.71  5037.2   97.47  5052.9  104.69
  5069.8   98.36  5097.3   95.88  5228.6   96.03  5281.5    96.4  5321.5   101.2
#Mann= 6 , 1 , 0
  3037.9      .1       0  3451.4     .06       0  4915.2     .08       0
    4975     .04       0  5026.6     .08       0  5228.6      .2       0
#XS Ineff= 2 , 0
       0  4859.6    97.6               0
Permanent Ineff=
       F       F
Bank Sta=4975,5026.6
XS Rating Curve= 0
Exp/Cntr=.3,.1

Type RM Length L Ch R = 1 ,28098.6 ,1025.5,848.7,845.6
BEGIN DESCRIPTION:
Cross Section 28098.6
END DESCRIPTION:
XS GIS Cut Line= 4
      3056171.45     13862098.01      3054542.66     13862017.12
      3054430.03     13862017.74      3054120.06     13862016.64
#Sta/Elev= 30
  3255.5    98.4  3365.5    96.3  3395.5    96.4  3415.5    95.6  3435.5    96.3
  3455.5      96  3465.5    95.2  3935.5    95.5  3975.5    97.4  4185.5    95.8
  4225.5    94.5  4406.5   94.39  4906.5   95.52  4977.9   94.79  4990.4   89.68
  4996.8   83.26    5002   82.43  5008.2   85.94    5012   86.26  5031.8   96.52
  5044.5   97.29  5055.1  103.14  5059.5  103.29  5064.9  103.48  5093.2   95.89
  5117.2   94.95  5198.9    95.7  5208.9    95.2  5268.9    96.5  5308.9   100.6
#Mann= 6 , 1 , 0
  3255.5     .99       0  4406.5     .06       0  4906.5     .08       0
  4977.9     .04       0  5031.8     .08       0  5059.5      .2       0
#XS Ineff= 2 , 0
       0  3975.5    97.4               0
Permanent Ineff=
       F       F
Bank Sta=4977.9,5031.8
XS Rating Curve= 0
Exp/Cntr=.3,.1

Type RM Length L Ch R = 1 ,27249.9 ,201.2,111.6,111.5
BEGIN DESCRIPTION:
Cross Section 27249.9-INTERPOLATED
END DESCRIPTION:
XS GIS Cut Line= 3
      3055058.29     13861241.89      3054597.43     13861187.82
      3054130.76     13861132.12
#Sta/Elev= 29
  4378.4    98.9  4468.4    95.8  4788.4    96.1  4798.4    95.6  4827.9   96.49
  4828.4    96.5  4852.4    94.2  4952.4    96.8  4962.4    96.4  4977.7   95.04
  4981.4   89.61  4983.8   87.09  4990.3   85.44  4994.7   83.76    4996    83.8
  4996.8   82.67    5001   83.36  5003.6   83.23  5005.3   83.82  5009.7   85.93
  5010.3   86.47    5017   91.18  5022.6   95.85  5032.4    97.1  5072.4    98.6
  5206.4   97.41  5252.4      97  5302.4   100.6  5312.4     102
#Mann= 5 , 1 , 0
  4378.4      .1       0  4827.9     .08       0  4977.7     .04       0
  5022.6     .08       0  5206.4      .2       0
#XS Ineff= 2 , 0
       0  4952.4    96.8               0
Permanent Ineff=
       F       F
Bank Sta=4977.7,5022.6
XS Rating Curve= 0
Exp/Cntr=.5,.3

Type RM Length L Ch R = 1 ,27138.3 ,33.6,33.6,33.6
BEGIN DESCRIPTION:
Upstream Section of Bridge - Updated April 2011
END DESCRIPTION:
XS GIS Cut Line= 3
      3055172.57     13861144.79      3054442.39     13861059.48
      3054138.98     13861029.92
#Sta/Elev= 27
    4265    99.4    4375    98.9    4465      96    4700   96.34  4784.3   96.46
  4814.1   95.98  4828.3   96.03  4843.7   96.09    4884   96.03  4922.5   96.42
 4971.67   95.21 4972.37   96.68 4973.37   96.68 4975.04   94.61 4996.88   83.12
 5000.78    82.3 5004.68   83.12 5026.52   94.61 5031.37   96.53 5032.37   96.53
  5127.9   95.28  5173.9   94.92  5207.6   95.83  5212.6   95.96  5219.2   95.86
    5265    97.5    5305   101.1
#Mann= 6 ,-1 , 0
    4265     .99       0    4700      .1       0  4828.3     .08       0
 4971.67     .04       0 5032.37     .08       0  5207.6      .2       0
#XS Ineff= 2 , 0
       0 4952.45   97.03 5052.45       0   97.03
Permanent Ineff=
       F       F
Bank Sta=4973.37,5031.37
XS Rating Curve= 0
Exp/Cntr=.5,.3

Type RM Length L Ch R = 3 ,27121.5 ,,,
BEGIN DESCRIPTION:
CenterPoint Energy - Bridge Replacement (as-built)
Structure ID: W167-12
END DESCRIPTION:
Bridge Culvert--1,0,-1,-1, 0
Deck Dist Width WeirC Skew NumUp NumDn MinLoCord MaxHiCord MaxSubmerge Is_Ogee
4.8,24,2.6,0, 34, 34, , , .95, 0, 1,1,,
    4265    4375    4465    4700  4711.2  4784.3  4808.5  4814.1  4828.3    4842
  4843.7    4884    4885  4922.5  4922.8 4940.23 4972.45 4973.03 5002.45 5029.29
 5032.45 5053.45  5076.1  5077.7  5127.2  5127.9  5173.9    5174  5207.6    5212
  5212.6  5219.2    5265    5305
    99.4    98.9      96   96.34   96.36   96.47   96.08   95.99   96.04   96.11
    96.1   96.04   96.05   96.43   96.42   96.43   97.03   97.03   97.07   97.11
   97.11    96.9   96.01   95.99    95.3   95.29   94.93   94.93   95.84   95.95
   95.96   95.86    97.5   101.1
                                                                                
                                                           94.58   94.61   94.63
                                                                                
                                
    4265    4375    4465    4700  4711.2  4784.3  4808.5  4814.1  4828.3    4842
  4843.7    4884    4885  4922.5  4922.8 4940.23 4972.45 4973.03 5002.45 5029.29
 5032.45 5053.45  5076.1  5077.7  5127.2  5127.9  5173.9    5174  5207.6    5212
  5212.6  5219.2    5265    5305
   99.29   98.79   95.89   96.23   96.24   96.35   95.96   95.87   95.92   95.97
   95.98   95.92   95.93   96.31    96.3   96.43   97.03   97.03   97.07   97.11
   97.11    96.9   95.89   95.87   95.18   95.17   94.81   94.81   95.72   95.83
   95.85   95.75   97.39  100.99
                                                                                
                                                           94.58   94.66   94.63
                                                                                
                                
BR Coef= 1 , 1 , 0 ,1.25, 0 ,,,.8,0,2,0,
WSPro=,,,, 1 ,,,, 0 ,,,, 0 ,,,,-1 ,-1 ,-1 , 0 , 0 , 0 , 0 , 0
BR U #Sta/Elev= 34
    4265    99.4    4375    98.9    4465      96    4700   96.34  4711.2   96.36
  4784.3   96.47  4808.5   96.08  4814.1   95.99  4828.3   96.04    4842   96.11
  4843.7    96.1    4884   96.04    4885   96.05  4922.5   96.43  4922.8   96.42
 4972.84   95.05 4975.04   94.61 4996.88   83.12 5000.78   82.29 5004.68   83.12
 5026.52   94.61  5030.7   95.22  5076.1      96  5077.7   95.98  5127.2   95.29
  5127.9   95.28  5173.9   94.92    5174   94.92  5207.6   95.83    5212   95.94
  5212.6   95.96  5219.2   95.86    5265    97.5    5305   101.1
BR U #Mann= 6
    4265     .99    4700      .1  4828.3     .08 4972.84     .04  5030.7     .08
  5207.6      .2
BR U Banks=4972.84,5030.7
BR D #Sta/Elev= 34
    4265   99.29    4375   98.79    4465   95.89    4700   96.23  4711.2   96.24
  4784.3   96.35  4808.5   95.96  4814.1   95.87  4828.3   95.92    4842   95.97
  4843.7   95.98    4884   95.92    4885   95.93  4922.5   96.31  4922.8    96.3
 4972.84   95.05 4974.22   94.61 4996.06   83.12 5000.18   82.29  5004.3   83.12
 5026.14   94.61  5030.7   95.23  5076.1   95.89  5077.7   95.87  5127.2   95.18
  5127.9   95.17  5173.9   94.81    5174   94.81  5207.6   95.72    5212   95.83
  5212.6   95.85  5219.2   95.75    5265   97.39    5305  100.99
BR D #Mann= 6
    4265     .99    4700      .1  4828.3     .08 4972.84     .04  5030.7     .08
  5207.6      .2
BR D Banks=4972.84,5030.7
BC Design=,, 0 ,, 0 ,,,,,,
BC HTab HWMax=101.1

Type RM Length L Ch R = 1 ,27104.7 ,156.4,156.4,156.4
BEGIN DESCRIPTION:
Downstream Section of Bridge - Updated April 2011
END DESCRIPTION:
XS GIS Cut Line= 3
      3055173.06     13861111.19      3054442.87     13861025.88
      3054139.46     13860996.32
#Sta/Elev= 28
    4265   99.27    4375   98.77    4465   95.87    4700   96.21  4784.3   96.33
  4814.1   95.85  4828.3    95.9  4843.7   95.96    4884    95.9  4922.5   96.29
 4971.65   95.38 4972.38   96.44 4973.38   96.44 4974.22   94.61 4996.06   83.12
 5000.18   82.28  5004.3   83.12 5026.14   94.61 5031.37   96.37 5032.37   96.37
  5077.7   95.85  5127.9   95.15  5173.9   94.79  5207.6    95.7  5212.6   95.83
  5219.2   95.73    5265   97.37    5305  100.97
#Mann= 6 ,-1 , 0
    4265     .99       0    4700      .1       0  4828.3     .08       0
 4971.65     .04       0 5032.37     .08       0  5207.6      .2       0
#XS Ineff= 2 , 0
       0 4952.45   95.83 5052.45       0   95.83
Permanent Ineff=
       F       F
Bank Sta=4973.38,5031.37
XS Rating Curve= 0
Exp/Cntr=.5,.3