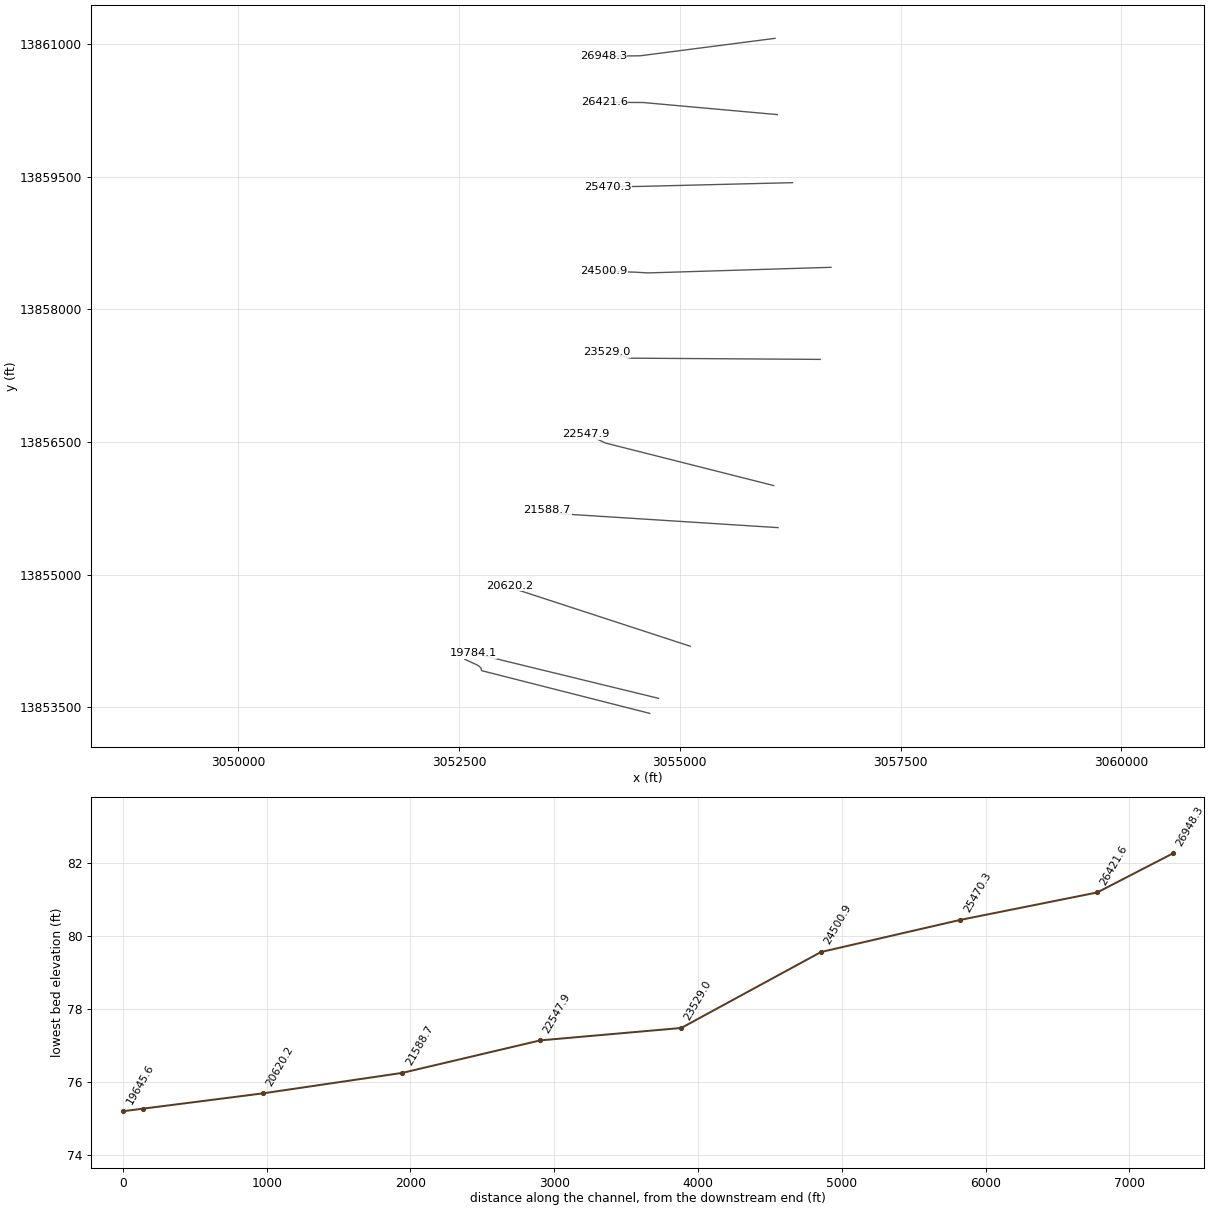
HEC-RAS study W167-00-00pp.prj: W167-00-00

--- W167-00-00pp.g01 (geometry) --- (continued)

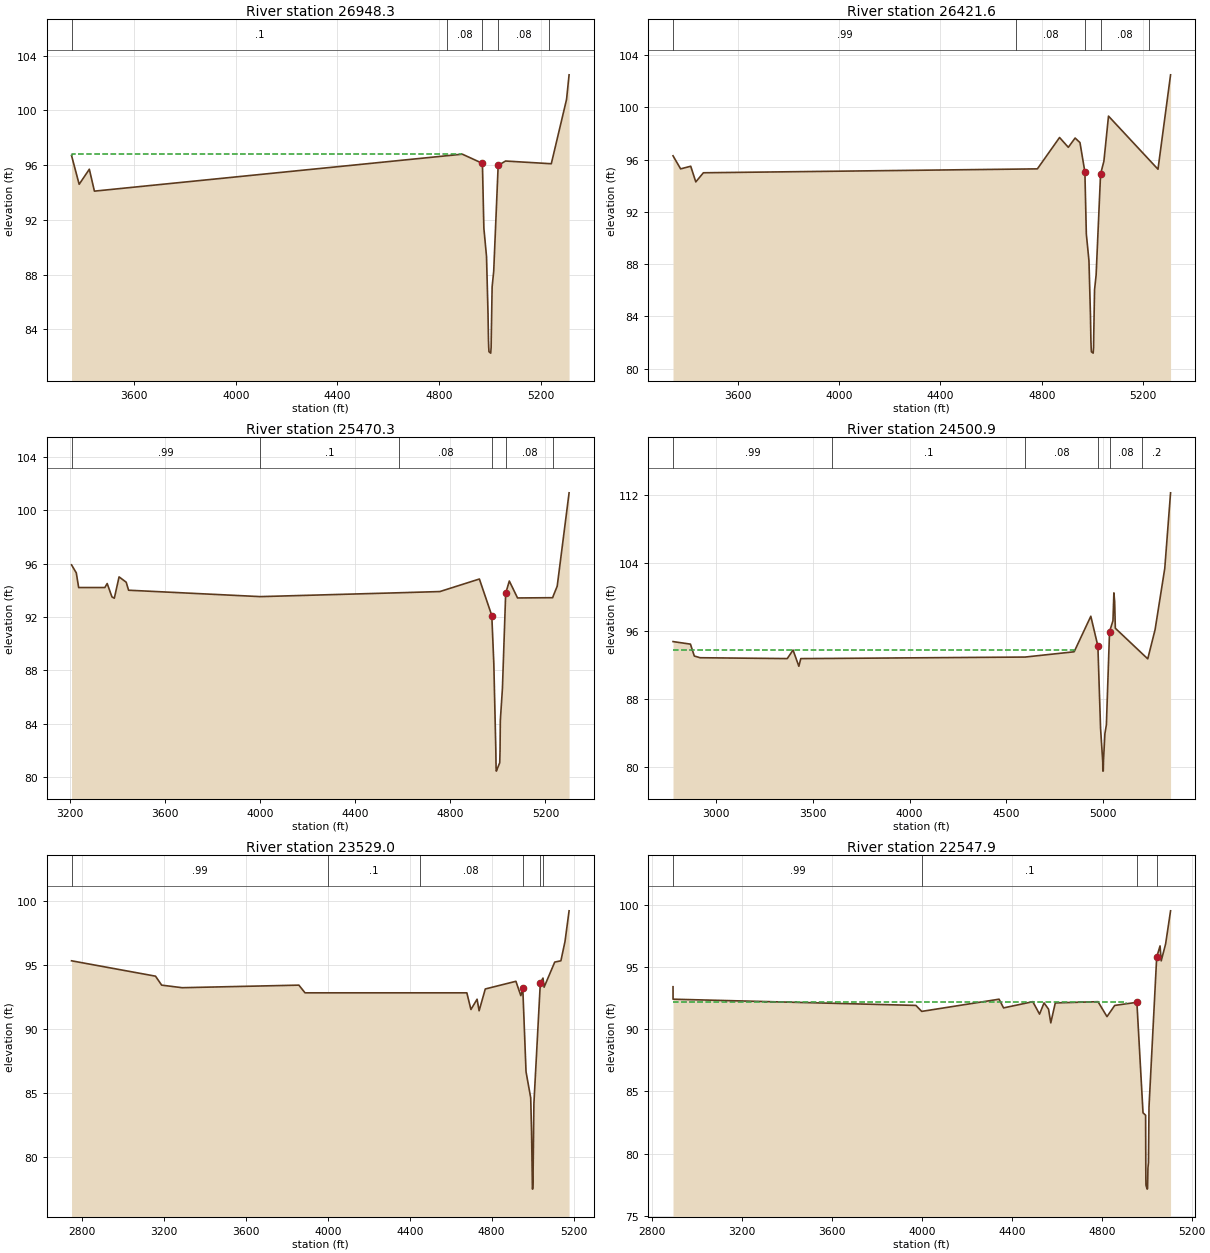
Type RM Length L Ch R = 1 ,26948.3 ,855.8,526.7,526.5
BEGIN DESCRIPTION:
Cross Section 26948.3-INTERPOLATED
END DESCRIPTION:
XS GIS Cut Line= 3
      3056077.94     13861066.44      3054552.96     13860869.17
      3054132.99     13860862.91
#Sta/Elev= 24
    3354    96.7    3384    94.6    3424    95.7    3444    94.1  4832.3   96.69
  4891.7    96.8  4970.7   96.13  4976.4   91.39  4986.8   89.33  4992.7   85.18
  4994.5   83.21  4995.4   82.73  4996.5   82.36  5003.4   82.26    5005   82.69
  5005.5   83.42  5008.9   87.11  5015.1   88.24  5032.7   95.98  5061.7    96.3
  5233.8   96.11  5241.7    96.1  5301.7   100.8  5311.7   102.6
#Mann= 5 , 1 , 0
    3354      .1       0  4832.3     .08       0  4970.7     .04       0
  5032.7     .08       0  5233.8      .2       0
#XS Ineff= 2 , 0
       0  4891.7    96.8               0
Permanent Ineff=
       F       F
Bank Sta=4970.7,5032.7
XS Rating Curve= 0
Exp/Cntr=.3,.1

Type RM Length L Ch R = 1 ,26421.6 ,1098,951.3,950.6
BEGIN DESCRIPTION:
Cross Section 26421.6
END DESCRIPTION:
XS GIS Cut Line= 4
       3056104.4     13860203.56      3054582.89     13860340.32
      3054454.26     13860340.95      3054144.25     13860343.55
#Sta/Elev= 29
    3343    96.3    3373    95.3    3413    95.5    3433    94.3    3463      95
    4700   95.28    4783    95.3  4870.6    97.7  4905.2   96.95  4932.1   97.66
  4951.3   97.31  4970.7   95.06  4976.4   90.32  4986.8   88.26  4992.7   84.11
  4994.5   82.14  4995.4   81.66  4996.5   81.29  5003.4   81.19    5005   81.62
  5005.5   82.35  5008.9   86.04  5015.1   87.17  5032.7   94.91  5045.9   95.89
    5064   99.34    5224   96.01  5259.6   95.27  5309.3   102.5
#Mann= 5 , 1 , 0
    3343     .99       0    4700     .08       0  4970.7     .04       0
  5032.7     .08       0    5224      .2       0
Bank Sta=4970.7,5032.7
XS Rating Curve= 0
Exp/Cntr=.3,.1

Type RM Length L Ch R = 1 ,25470.3 ,1007.5,969.4,966.2
BEGIN DESCRIPTION:
Cross Section 25470.3
END DESCRIPTION:
XS GIS Cut Line= 4
       3056276.3     13859433.59      3054559.36     13859391.29
      3054483.34     13859390.13      3054183.33     13859389.63
#Sta/Elev= 30
  3205.9    95.9  3225.9    95.3  3235.9    94.2  3345.9    94.2  3355.9    94.5
  3375.9    93.5  3385.9    93.4  3405.9      95  3435.9    94.6  3445.9      94
    4000   93.52  4585.4   93.81  4755.9    93.9    4922   94.84  4974.2    92.1
  4982.7   88.51  4991.1   82.07  4992.2   80.68  4993.3   80.44  5007.6   81.07
  5008.9   81.98  5010.1   84.24  5018.9   86.62  5032.6   93.76  5047.9   94.69
  5082.5   93.42  5230.3   93.44    5233   93.58  5249.4    94.3  5299.4   101.3
#Mann= 6 , 1 , 0
  3205.9     .99       0    4000      .1       0  4585.4     .08       0
  4974.2     .04       0  5032.6     .08       0    5233      .2       0
#XS Ineff= 2 , 0
       0    4922   94.84               0
Permanent Ineff=
       F       F
Bank Sta=4974.2,5032.6
XS Rating Curve= 0
Exp/Cntr=.3,.1

Type RM Length L Ch R = 1 ,24500.9 ,1253.3,971.9,951.3
BEGIN DESCRIPTION:
Cross Section 24500.9
END DESCRIPTION:
XS GIS Cut Line= 4
      3056711.87     13858475.76      3054640.78     13858412.42
      3054493.03     13858420.89      3054143.22     13858430.52
#Sta/Elev= 30
  2778.5    94.8  2868.5    94.5  2888.5    93.1  2918.5    92.9  3368.5    92.8
  3398.5    93.8  3428.5    91.9  3438.5    92.8  3599.5   92.82  4597.3   92.98
  4850.5    93.6  4936.5   97.78  4973.1   94.27    4987   84.56  4998.2   80.67
  4998.7   79.56  5000.9   79.58  5001.9   80.76  5009.3   83.96    5017   85.01
  5033.3   95.98    5051   97.25  5055.7  100.53  5059.5   99.58  5063.2   96.37
  5200.7   93.41  5230.7   92.77  5268.5    96.2  5318.5   103.4  5348.5   112.3
#Mann= 6 , 1 , 0
  2778.5     .99       0  3599.5      .1       0  4597.3     .08       0
  4973.1     .04       0  5033.3     .08       0  5200.7      .2       0
#XS Ineff= 2 , 0
       0  4850.3    93.8               0
Permanent Ineff=
       F       F
Bank Sta=4973.1,5033.3
XS Rating Curve= 0
Exp/Cntr=.3,.1

Type RM Length L Ch R = 1 ,23529.0 ,1036.2,981.1,974.1
BEGIN DESCRIPTION:
Cross Section 23529.0
END DESCRIPTION:
XS GIS Cut Line= 4
      3056589.44     13857434.06      3054440.39     13857447.91
       3054342.8     13857470.06      3054167.79     13857512.28
#Sta/Elev= 30
  2748.8    95.3  3158.8    94.1  3188.8    93.4  3288.8    93.2  3858.8    93.4
  3888.8    92.8  3999.8    92.8  4447.9    92.8  4678.8    92.8  4698.8    91.5
  4728.8    92.3  4738.8    91.4  4768.8    93.1  4918.4    93.7  4942.4   92.58
    4952   93.14  4967.8   86.64  4990.6   84.61  4994.8   81.99    4999   77.49
  5000.5   77.48  5001.8   78.06  5006.2   84.15  5037.6   93.58  5050.6   93.95
    5056   93.24    5108    95.2    5138    95.3    5158    96.8    5178    99.2
#Mann= 6 , 1 , 0
  2748.8     .99       0  3999.8      .1       0  4447.9     .08       0
    4952     .04       0  5037.6     .08       0  5050.6      .2       0
#XS Ineff= 2 , 0
       0  4768.8    93.1               0
Permanent Ineff=
       F       F
Bank Sta=4952,5037.6
XS Rating Curve= 0
Exp/Cntr=.3,.1

Type RM Length L Ch R = 1 ,22547.9 ,865.6,959.2,959.2
BEGIN DESCRIPTION:
Cross Section 22547.9
END DESCRIPTION:
XS GIS Cut Line= 4
      3056062.16     13856006.73      3054157.47     13856487.73
      3054032.64     13856547.34      3053930.98     13856589.32
#Sta/Elev= 30
  2893.1    93.4  2893.2    92.4  3973.2    91.9  3999.2   91.42  4343.2    92.4
  4363.2    91.7  4493.2    92.2  4523.2    91.2  4543.2    92.1  4563.2    91.6
  4573.2    90.5  4593.2    92.1  4783.2    92.2  4823.2      91  4857.6    91.9
  4956.1   92.15  4983.4   83.27  4994.9   83.08    4996   77.97  4996.6   77.44
  5001.8   77.14  5003.5   77.16  5005.3   78.84  5007.6   79.27    5010   83.73
  5044.2   95.78  5059.2   96.68  5064.3   95.48  5083.8   96.83  5105.9    99.5
#Mann= 4 , 1 , 0
  2893.1     .99       0  3999.2      .1       0  4956.1    .035       0
  5044.2      .2       0
#XS Ineff= 2 , 0
       0  4906.1    92.2               0
Permanent Ineff=
       F       F
Bank Sta=4956.1,5044.2
XS Rating Curve= 0
Exp/Cntr=.3,.1

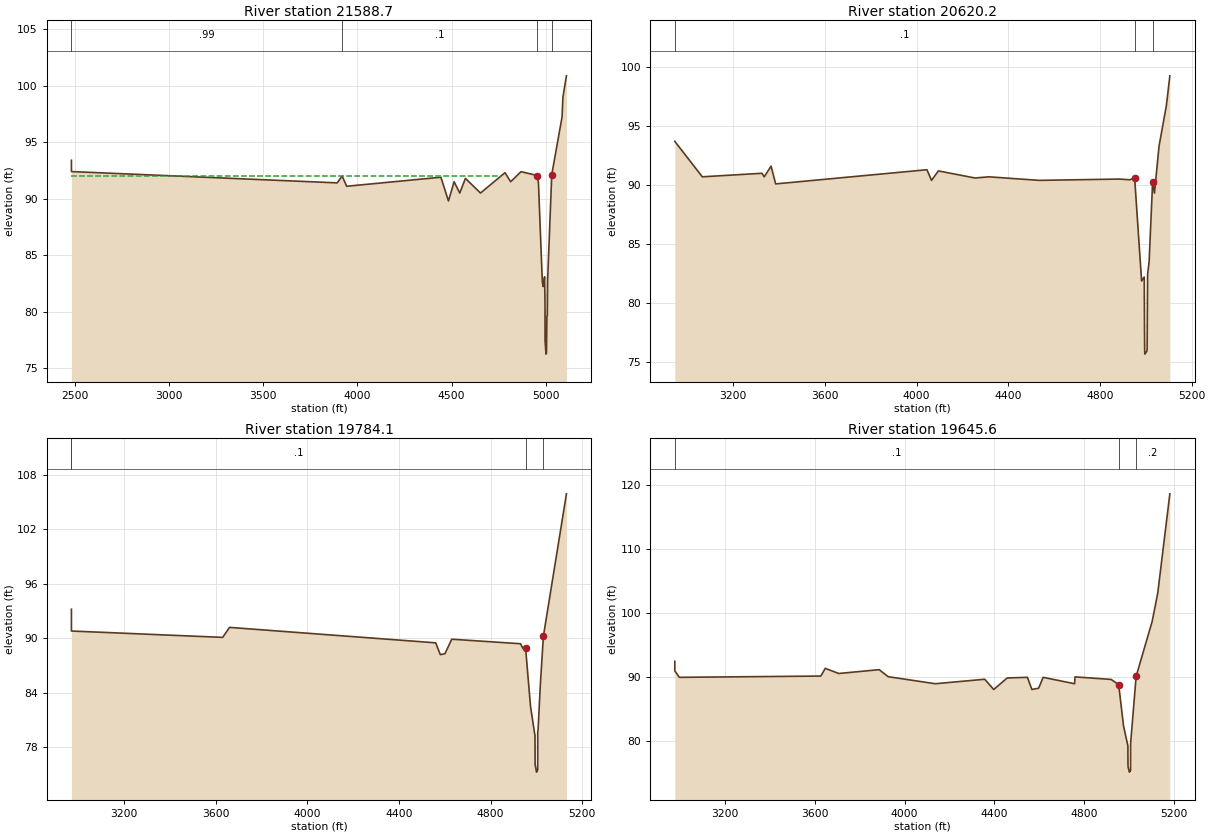
Type RM Length L Ch R = 1 ,21588.7 ,1067.4,968.5,964.6
BEGIN DESCRIPTION:
Cross Section 21588.7
END DESCRIPTION:
XS GIS Cut Line= 3
      3056112.72     13855530.43      3053600.36     13855690.53
      3053498.88     13855729.33
#Sta/Elev= 30
  2483.1    93.4  2483.2    92.4  3893.2    91.4  3919.2   92.01  3943.2    91.1
  4443.2    91.9  4483.2    89.8  4513.2    91.5  4543.2    90.5  4573.2    91.8
  4653.2    90.5  4783.2    92.3  4813.2    91.5  4868.3   92.39  4954.8   92.05
  4960.7   91.38  4981.2   82.65  4985.6   82.23  4993.2   83.09  4995.4   80.93
  4995.8   77.45  5000.7   76.25  5003.1   76.36  5005.6   79.62  5007.6   79.67
  5009.1   82.69  5031.2   92.12  5085.8   97.22  5090.6      99  5109.2  100.87
#Mann= 4 , 1 , 0
  2483.1     .99       0  3919.2      .1       0  4954.8    .035       0
  5031.2      .2       0
#XS Ineff= 2 , 0
       0 4761.52      92               0
Permanent Ineff=
       F       F
Bank Sta=4954.8,5031.2
XS Rating Curve= 0
Exp/Cntr=.3,.1

Type RM Length L Ch R = 1 ,20620.2 ,779.2,836.1,844.1
BEGIN DESCRIPTION:
Cross Section 20620.2
END DESCRIPTION:
XS GIS Cut Line= 3
      3055118.21     13854188.74       3053164.2     13854825.97
      3053072.34     13854875.82
#Sta/Elev= 30
  2944.8    93.7  3064.8    90.7  3324.8      91  3334.8    90.7  3364.8    91.6
  3384.8    90.1  4044.8    91.3  4064.8    90.4  4094.8    91.2  4254.8    90.6
  4314.8    90.7  4534.8    90.4  4884.4   90.51  4929.8   90.45    4951   90.61
  4981.3   81.88  4992.9   82.22  4994.2   77.29  4994.7   75.95  4995.5   75.69
  5004.6   75.95  5005.3   76.16  5005.8   77.18  5007.6   82.44  5014.2   83.53
  5029.3   90.23  5037.5   89.32  5057.4   93.29  5089.7   96.77  5104.6   99.25
#Mann= 3 , 1 , 0
  2944.8      .1       0    4951    .035       0  5029.3      .2       0
#XS Ineff= 2 , 0
       0  3364.8    91.6               0
Permanent Ineff=
       F       F
Bank Sta=4951,5029.3
XS Rating Curve= 0
Exp/Cntr=.3,.1

Type RM Length L Ch R = 1 ,19784.1 ,167.6,138.5,127.2
BEGIN DESCRIPTION:
Cross Section 19784.1-INTERPOLATED
END DESCRIPTION:
XS GIS Cut Line= 3
      3054758.73     13853599.21      3052853.79      13854062.8
      3052660.03     13854112.35
#Sta/Elev= 22
  2970.8    93.2  2970.9    90.8  3630.9    90.1  3660.9    91.2  4560.9    89.5
  4580.9    88.2  4600.9    88.3  4630.9    89.9  4930.9    89.4  4941.4    88.9
    4953   88.94  4974.7   82.47    4993   79.44    4994   79.39  4994.6   76.13
  5000.7   75.27  5005.9   75.51    5006   79.67  5007.7      80  5017.3   84.82
  5030.7   90.22  5131.4   105.9
#Mann= 4 , 1 , 0
  2970.8      .2       0  2970.9      .1       0    4953     .04       0
  5030.7      .2       0
#XS Ineff= 2 , 0
       0  3660.9    91.2               0
Permanent Ineff=
       F       F
Bank Sta=4953,5030.7
XS Rating Curve= 0
Exp/Cntr=.5,.3

Type RM Length L Ch R = 1 ,19645.6 ,27.2,27.2,27.2
BEGIN DESCRIPTION:
Upstream Section of Bridge/Culvert/Weir
END DESCRIPTION:
XS GIS Cut Line= 6
      3054659.29     13853429.05      3052754.93     13853912.37
      3052747.35       13853942.      3052728.28     13853961.07
      3052698.31     13853980.14      3052565.06      13854040.3
#Sta/Elev= 30
  2976.5   92.51  2976.6   91.01  2996.6   90.01  3626.6   90.21  3646.6   91.41
  3706.6   90.61  3886.6   91.21  3926.6   90.11  4136.6   89.01  4356.6   89.71
  4396.6   88.11  4456.6   89.91  4546.6   90.01  4566.6   88.11  4596.6   88.31
  4616.6   90.01  4756.6   89.01  4758.7   90.08  4919.3   89.68    4953   88.87
  4974.7    82.4    4994   79.32  4994.6   76.06  5000.7    75.2  5005.9   75.44
    5006    79.6  5030.7   90.15  5102.2   98.76  5126.8  103.12  5180.9  118.68
#Mann= 3 , 1 , 0
  2976.5      .1       0    4953     .04       0  5030.7      .2       0
#XS Ineff= 2 , 0
       0  3646.6    91.4    5031       0   90.18
Permanent Ineff=
       F       F
Bank Sta=4953,5030.7
XS Rating Curve= 0
Exp/Cntr=.5,.3