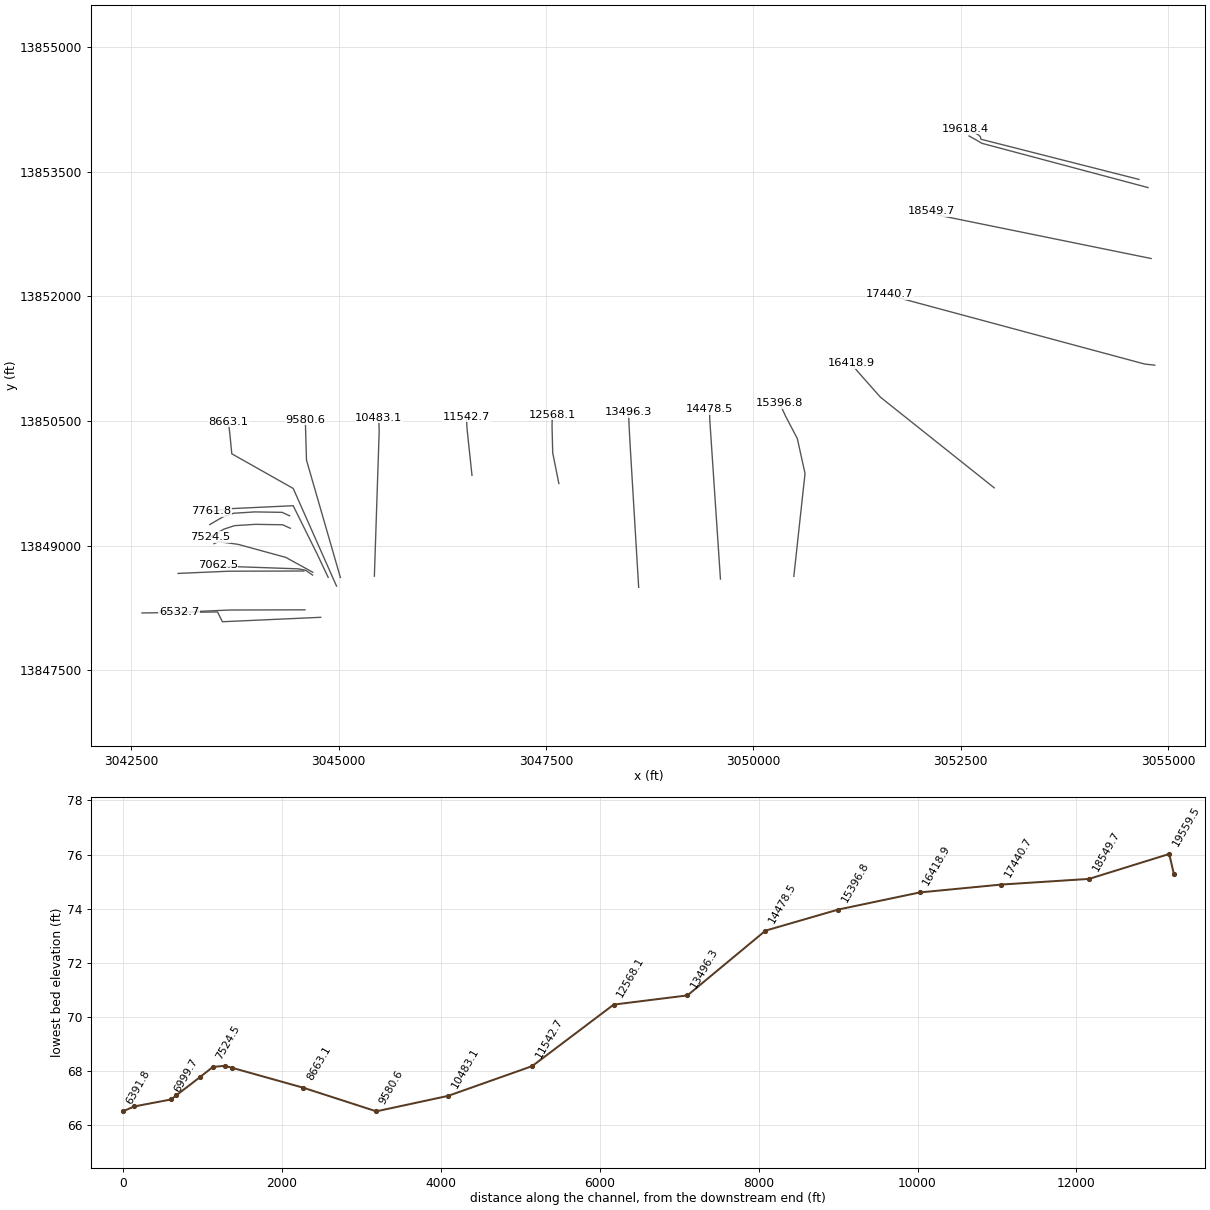
HEC-RAS study W167-00-00pp.prj: W167-00-00

--- W167-00-00pp.g01 (geometry) --- (continued)

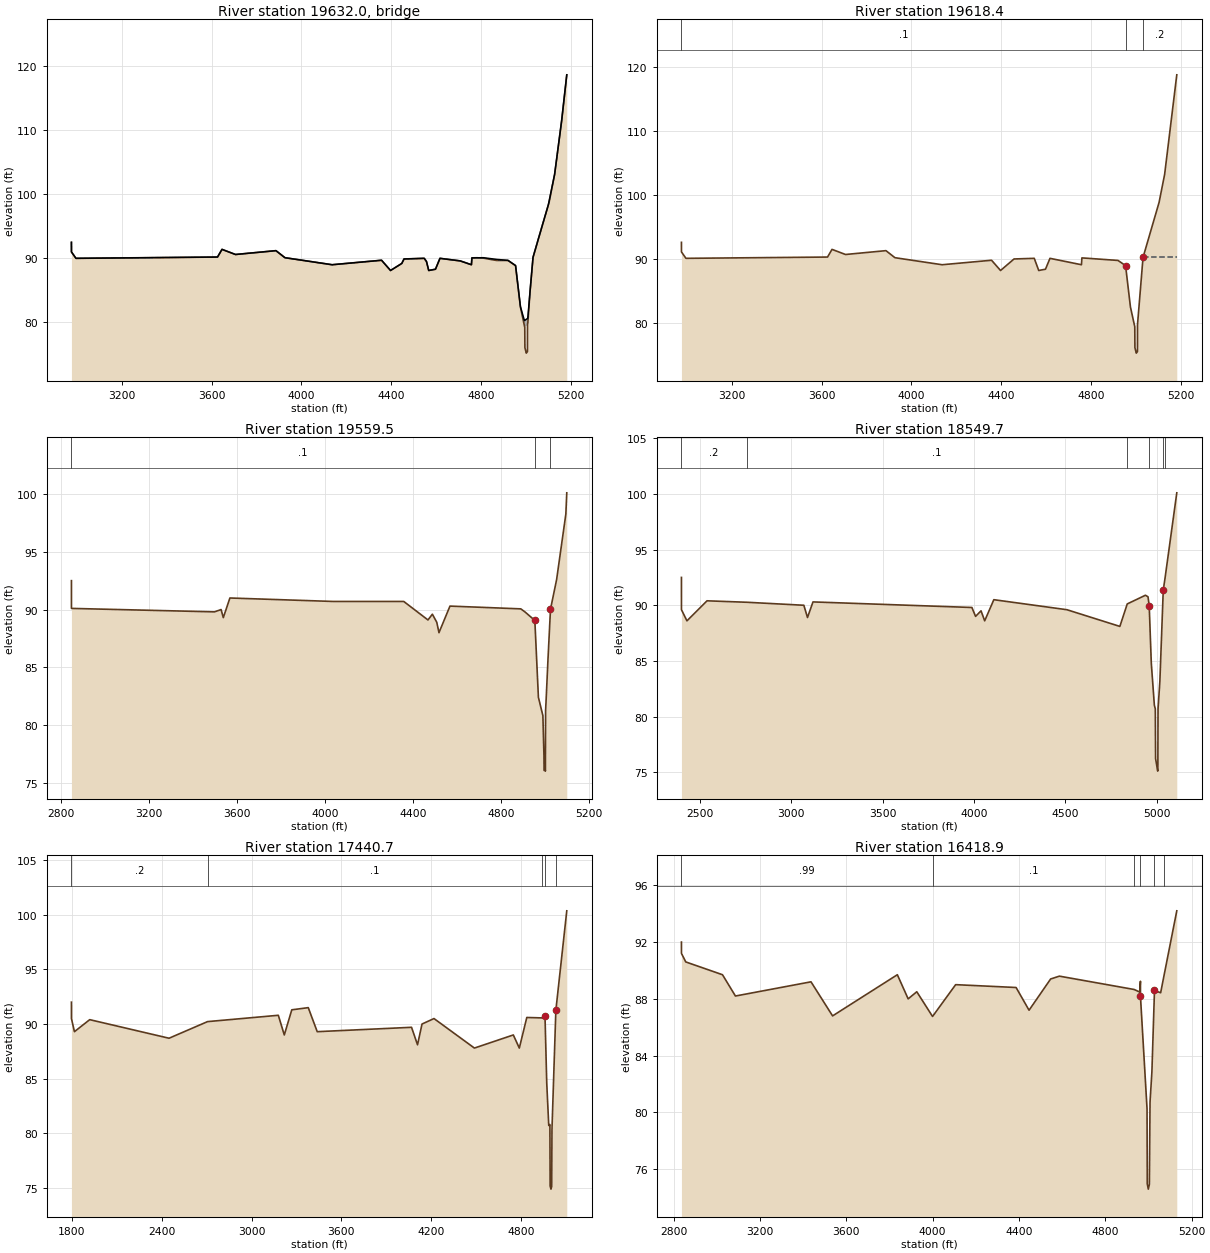
Type RM Length L Ch R = 3 ,19632.0 ,,,
BEGIN DESCRIPTION:
CHATTERTON & SHERWOOD FOREST-FOOTBRIDGE
Structure ID: W67-10
END DESCRIPTION:
Bridge Culvert--1,0,-1,-1, 0
Deck Dist Width WeirC Skew NumUp NumDn MinLoCord MaxHiCord MaxSubmerge Is_Ogee
10,7.2,2.6,0, 38, 38, , , .95, 0, 1,1,,
  2976.5  2976.6  2996.6  3626.6  3646.6  3706.6  3886.6  3926.6  4136.6  4356.6
  4396.6  4446.6  4456.6  4546.6  4556.6  4566.6  4596.6  4616.6  4706.6  4756.6
  4758.7  4808.9  4867.7  4919.3    4953  4974.7 4992.29    4994    5006  5007.1
  5007.6  5017.3  5030.7  5098.7  5102.2  5126.8    5158  5180.9
    92.5      91      90    90.2    91.4    90.6    91.2    90.1      89    89.7
    88.1    89.2    89.9      90    89.5    88.1    88.3      90    89.6      89
   90.07    90.1   89.84   89.68   88.87   82.45   80.28   80.31    80.6   80.62
   80.74   84.75   90.15   98.34   98.92  103.12  111.47  118.67
    92.5      91      90    90.2    91.4    90.6    91.2    90.1      89    89.7
    88.1    89.2    89.9      90    89.5    88.1    88.3      90    89.6      89
   90.07   90.04   89.67   89.67   88.86   82.39   79.48   79.31    79.6   79.82
   79.92   84.74   90.14   98.33   98.75  103.11  111.47  118.67
  2976.5  2976.6  2996.6  3626.6  3646.6  3706.6  3886.6  3926.6  4136.6  4356.6
  4396.6  4446.6  4456.6  4546.6  4556.6  4566.6  4596.6  4616.6  4706.6  4756.6
  4758.7  4808.9  4867.7  4919.3    4953  4974.7 4992.29    4994    5006  5007.1
  5007.6  5017.3  5030.7  5098.7  5102.2  5126.8    5158  5180.9
    92.5      91      90    90.2    91.4    90.6    91.2    90.1      89    89.7
    88.1    89.2    89.9      90    89.5    88.1    88.3      90    89.6      89
   90.07    90.1   89.84   89.68   88.87   82.45   80.28   80.31    80.6   80.62
   80.74   84.75   90.15   98.34   98.92  103.12  111.47  118.67
   92.46   90.96   89.96   90.16   91.36   90.56   91.16   90.06   88.96   89.66
   88.06   89.16   89.86   89.96   89.46   88.06   88.26   89.96   89.56   88.96
   90.03      90   89.63   89.63   88.82   82.35   79.44   79.27   79.56   79.78
   79.88    84.7    90.1   98.29   98.71  103.07  111.43  118.63
BR Coef= 1 , 1 , 0 ,1.25, 0 ,,,.8,0,2,0,
WSPro=,,,, 1 ,,,, 0 ,,,, 0 ,,,,-1 ,-1 ,-1 , 0 , 0 , 0 , 0 , 0
BR U #Sta/Elev= 63
  2976.5    92.5  2976.6      91  2996.6      90  3626.6    90.2  3646.6    91.4
  3706.6    90.6  3886.6    91.2  3926.6    90.1  4136.6      89  4356.6    89.7
  4396.6    88.1  4446.6    89.2  4456.6    89.9  4546.6      90  4556.6    89.5
  4566.6    88.1  4596.6    88.3  4616.6      90  4706.6    89.6  4756.6      89
  4758.7   90.07    4781   90.09  4781.2   90.09  4807.9   90.04  4808.9   90.04
  4841.7   89.83  4867.7   89.67  4917.2   89.67  4919.3   89.67    4953   88.86
  4974.7   82.39 4992.29   79.48  4992.4   79.46 4992.51   79.44  4992.6   79.43
 4992.71   79.41  4992.8   79.39  4992.9   79.38    4993   79.36    4994   79.31
  4994.6   76.05  5000.7   75.19  5005.9   75.43    5006   79.59 5006.49   79.69
  5006.6   79.71 5006.71   79.74    5007    79.8  5007.1   79.82 5007.49    79.9
  5007.6   79.92  5007.7   79.97  5017.3   84.74  5030.7   90.14    5056   93.23
    5059   93.59  5098.7   98.33  5102.2   98.75  5126.8  103.11  5127.9   103.4
  5157.2  111.26    5158  111.47  5180.9  118.67
BR U #Mann= 3
  2976.5      .1    4953     .04  5030.7      .2
BR U Banks=4953,5030.7
BR D #Sta/Elev= 63
  2976.5   92.46  2976.6   90.96  2996.6   89.96  3626.6   90.16  3646.6   91.36
  3706.6   90.56  3886.6   91.16  3926.6   90.06  4136.6   88.96  4356.6   89.66
  4396.6   88.06  4446.6   89.16  4456.6   89.86  4546.6   89.96  4556.6   89.46
  4566.6   88.06  4596.6   88.26  4616.6   89.96  4706.6   89.56  4756.6   88.96
  4758.7   90.03    4781   90.05  4781.2   90.05  4807.9      90  4808.9      90
  4841.7   89.79  4867.7   89.63  4917.2   89.63  4919.3   89.63    4953   88.82
  4974.7   82.35 4992.29   79.44  4992.4   79.42 4992.51    79.4  4992.6   79.39
 4992.71   79.37  4992.8   79.35  4992.9   79.34    4993   79.32    4994   79.27
  4994.6   76.01  5000.7   75.15  5005.9   75.39    5006   79.55 5006.49   79.65
  5006.6   79.67 5006.71    79.7    5007   79.76  5007.1   79.78 5007.49   79.86
  5007.6   79.88  5007.7   79.93  5017.3    84.7  5030.7    90.1    5056   93.19
    5059   93.55  5098.7   98.29  5102.2   98.71  5126.8  103.07  5127.9  103.36
  5157.2  111.22    5158  111.43  5180.9  118.63
BR D #Mann= 3
  2976.5      .1    4953     .04  5030.7      .2
BR D Banks=4953,5030.7
BC Design=,, 0 ,, 0 ,,,,,,
BC HTab HWMax=118.68

Type RM Length L Ch R = 1 ,19618.4 ,58.9,58.9,58.9
BEGIN DESCRIPTION:
Downstream Section of Bridge/Culvert/Weir
END DESCRIPTION:
XS GIS Cut Line= 6
      3054647.02     13853404.77      3052742.67     13853888.09
      3052735.09     13853917.72      3052716.02     13853936.79
      3052686.05     13853955.86       3052552.8     13854016.03
#Sta/Elev= 30
  2976.5   92.59  2976.6   91.09  2996.6   90.09  3626.6   90.29  3646.6   91.49
  3706.6   90.69  3886.6   91.29  3926.6   90.19  4136.6   89.09  4356.6   89.79
  4396.6   88.19  4456.6   89.99  4546.6   90.09  4566.6   88.19  4596.6   88.39
  4616.6   90.09  4756.6   89.09  4758.7   90.16  4919.3   89.76    4953   88.95
  4974.7   82.48    4994    79.4  4994.6   76.14  5000.7   75.28  5005.9   75.52
    5006   79.68  5030.7   90.23  5102.2   98.84  5126.8   103.2  5180.9  118.76
#Mann= 3 , 1 , 0
  2976.5      .1       0    4953     .04       0  5030.7      .2       0
#XS Ineff= 2 , 0
       0  3646.6    91.4    5031       0   90.27
Permanent Ineff=
       F       F
Bank Sta=4953,5030.7
XS Rating Curve= 0
Exp/Cntr=.5,.3

Type RM Length L Ch R = 1 ,19559.5 ,922.9,1009.8,1009
BEGIN DESCRIPTION:
Cross Section 19559.5
END DESCRIPTION:
XS GIS Cut Line= 4
      3054756.34     13853306.62      3052752.34     13853839.69
      3052686.18     13853879.19       3052598.5      13853927.4
#Sta/Elev= 29
  2849.1    92.5  2849.2    90.1  3499.2    89.8  3529.2      90  3539.2    89.3
  3569.2      91  4039.2    90.7  4359.2    90.7  4469.2    89.1  4489.2    89.6
  4509.2    88.9  4519.2      88  4569.2    90.3  4890.9   90.06  4910.3   89.79
  4954.8   89.06    4971   82.41  4991.4   80.82  4996.3   77.32  4996.8   76.08
    5002   76.12  5002.7   76.02  5003.7   81.27  5006.2   82.23  5014.8    85.8
  5025.9   90.02  5053.8    92.6  5095.7   98.26  5099.9   100.1
#Mann= 3 , 1 , 0
  2849.1      .1       0  4954.8     .04       0  5025.9      .2       0
#XS Ineff= 2 , 0
       0  3569.2      91               0
Permanent Ineff=
       F       F
Bank Sta=4954.8,5025.9
XS Rating Curve= 0
Exp/Cntr=.3,.1

Type RM Length L Ch R = 1 ,18549.7 ,1170.1,1109,1105
BEGIN DESCRIPTION:
Cross Section 18549.7
END DESCRIPTION:
XS GIS Cut Line= 3
       3054793.3     13852453.24       3052243.8     13852971.67
       3052147.6     13853025.05
#Sta/Elev= 30
  2398.4    92.5  2398.5    89.6  2428.5    88.6  2538.5    90.4  2755.1   90.27
  3068.5      90  3088.5    88.9  3118.5    90.3  3988.5    89.8  4008.5      89
  4038.5    89.5  4058.5    88.6  4108.5    90.5  4508.5    89.6  4798.5    88.1
  4838.9   90.12  4938.5    90.9  4952.6   90.76  4959.2   89.93  4970.6    84.8
  4987.3   81.03  4992.5    80.7  4994.1   76.21  5005.7    75.1  5006.5   75.49
  5007.5    80.7  5017.5   83.16  5036.1   91.37  5045.6   92.41  5110.1   100.1
#Mann= 6 , 1 , 0
  2398.4      .2       0  2755.1      .1       0  4838.9     .04       0
  4959.2    .035       0  5036.1     .04       0  5045.6      .2       0
#XS Ineff= 2 , 0
       0  4108.5    90.5               0
Permanent Ineff=
       F       F
Bank Sta=4959.2,5036.1
XS Rating Curve= 0
Exp/Cntr=.3,.1

Type RM Length L Ch R = 1 ,17440.7 ,1508.6,1021.8,993.6
BEGIN DESCRIPTION:
Cross Section 17440.7
END DESCRIPTION:
XS GIS Cut Line= 4
       3054837.4     13851170.36      3054716.02     13851183.51
      3051743.18     13851982.35      3051643.43     13852025.58
#Sta/Elev= 30
  1796.7      92  1796.8    90.5  1816.8    89.3  1918.8    90.4  2448.8    88.7
  2705.8   90.22  3178.8    90.8  3218.8      89  3268.8    91.3  3378.8    91.5
  3438.8    89.3  4068.8    89.7  4108.8    88.1  4138.8      90  4218.8    90.5
  4488.8    87.8  4748.8      89  4788.8    87.8  4838.8    90.6  4939.2   90.56
  4960.3   90.76  4972.1   84.57  4985.4   80.72  4993.1    80.8  4994.7   75.17
  5000.2   74.89    5005   75.14  5006.9   80.36  5032.9   91.26  5105.8  100.36
#Mann= 5 , 1 , 0
  1796.7      .2       0  2705.8      .1       0  4939.2     .04       0
  4960.3    .035       0  5032.9      .2       0
#XS Ineff= 2 , 0
       0  3378.8    91.5               0
Permanent Ineff=
       F       F
Bank Sta=4960.3,5032.9
XS Rating Curve= 0
Exp/Cntr=.3,.1

Type RM Length L Ch R = 1 ,16418.9 ,1328.4,1022.1,1015.9
BEGIN DESCRIPTION:
Cross Section 16418.9
END DESCRIPTION:
XS GIS Cut Line= 4
      3052902.05     13849694.65      3051531.74     13850784.13
      3051257.04      13851093.5      3051174.48     13851193.97
#Sta/Elev= 30
  2836.5      92  2836.6    91.2  2856.6    90.6  3026.6    89.7  3086.6    88.2
  3436.6    89.2  3536.6    86.8  3836.6    89.7  3886.6      88  3926.6    88.5
  3999.6   86.76  4106.6      89  4386.6    88.8  4446.6    87.2  4546.6    89.4
  4587.2    89.6  4933.5   88.66    4959   88.48  4962.6   89.24  4962.7   88.17
  4993.1   80.27  4994.2   74.97    4999    74.6  5003.9   74.93    5007   80.74
  5015.6   82.85  5027.6   88.59  5056.2   88.43  5069.8   89.49  5130.9    94.2
#Mann= 6 , 1 , 0
  2836.5     .99       0  3999.6      .1       0  4933.5     .04       0
  4962.7    .035       0  5027.6     .04       0  5069.8     .08       0
#XS Ineff= 2 , 0
       0  4587.2    89.6               0
Permanent Ineff=
       F       F
Bank Sta=4962.7,5027.6
XS Rating Curve= 0
Exp/Cntr=.3,.1

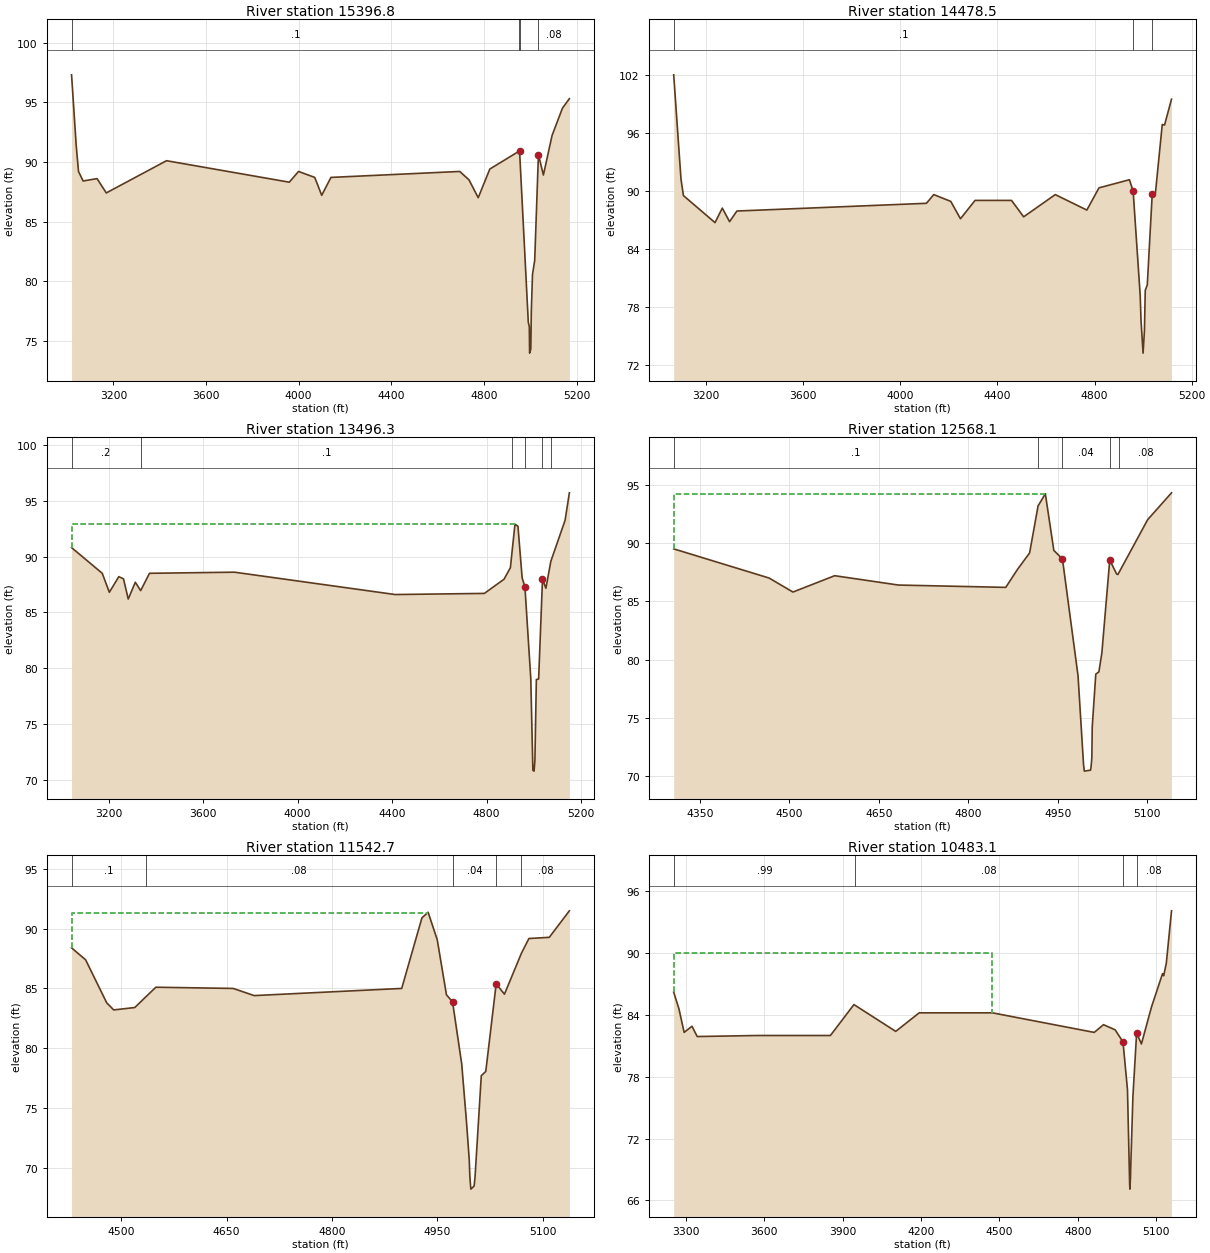
Type RM Length L Ch R = 1 ,15396.8 ,1118.4,918.3,898.6
BEGIN DESCRIPTION:
Cross Section 15396.8
END DESCRIPTION:
XS GIS Cut Line= 5
      3050487.09     13848629.31      3050622.05     13849867.71
      3050528.98     13850287.54      3050387.76     13850556.27
      3050316.42     13850710.55
#Sta/Elev= 30
  3019.4    97.3  3039.4    91.4  3049.4    89.2  3069.4    88.4  3129.4    88.6
  3169.4    87.4  3429.4    90.1  3959.4    88.3  3999.4    89.2  4069.4    88.7
  4099.4    87.2  4139.4    88.7  4695.2    89.2  4735.2    88.5  4775.2      87
  4825.2    89.4  4951.6    90.9  4953.7   90.91  4991.4   76.55  4995.7   76.21
    4997   73.97  5002.3   74.32  5004.4   77.51  5009.5   80.57    5019   81.74
  5035.1   90.62  5056.6    88.9  5093.9   92.21  5138.7    94.5  5168.7    95.3
#Mann= 4 , 1 , 0
  3019.4      .1       0  4951.6     .04       0  4953.7     .04       0
  5035.1     .08       0
#XS Ineff= 2 , 0
       0  4951.6    90.9               0
Permanent Ineff=
       F       F
Bank Sta=4953.7,5035.1
XS Rating Curve= 0
Exp/Cntr=.3,.1

Type RM Length L Ch R = 1 ,14478.5 ,1021.1,982.2,980.6
BEGIN DESCRIPTION:
Cross Section 14478.5
END DESCRIPTION:
XS GIS Cut Line= 3
       3049602.6     13848596.82      3049473.37     13850522.21
      3049472.79     13850640.89
#Sta/Elev= 30
  3068.5     102  3098.5    91.2  3108.5    89.5  3238.5    86.7  3268.5    88.2
  3298.5    86.8  3328.5    87.9  4108.5    88.7  4138.5    89.6  4208.5    88.9
  4248.5    87.1  4308.5      89  4458.5      89  4508.5    87.3  4638.5    89.6
  4768.5      88  4818.5    90.3  4943.7   91.14    4959   89.96  4988.1   79.13
  4991.5   76.53  4999.9   73.19  5005.5   75.51  5008.8   79.69  5017.2   80.25
  5037.5   89.64  5050.8   89.78  5078.8   96.86  5088.2    96.8  5116.9   99.48
#Mann= 3 , 1 , 0
  3068.5      .1       0    4959     .04       0  5037.5     .08       0
#XS Ineff= 2 , 0
       0  4943.7   91.14               0
Permanent Ineff=
       F       F
Bank Sta=4959,5037.5
XS Rating Curve= 0
Exp/Cntr=.3,.1

Type RM Length L Ch R = 1 ,13496.3 ,1111.2,928.2,926
BEGIN DESCRIPTION:
Cross Section 13496.3
END DESCRIPTION:
XS GIS Cut Line= 4
        3048617.     13848497.04      3048516.26     13850171.87
      3048501.08     13850451.55      3048494.88     13850601.41
#Sta/Elev= 30
  3042.8    90.8  3172.8    88.5  3202.8    86.8  3242.8    88.2  3262.8      88
  3282.8    86.2  3312.8    87.7  3335.4   86.95  3372.8    88.5  3732.8    88.6
  4412.8    86.6  4790.7    86.7  4874.1   87.97  4900.9      89  4908.9    90.6
  4920.4   92.89    4933   92.71  4950.7   88.09  4962.5   87.29  4987.3   79.08
  4996.2   70.87  5001.2    70.8  5004.7   71.71  5010.9   78.99  5020.6   79.05
  5036.9   87.98  5051.3   87.16  5072.3   89.58  5132.5   93.24  5150.7    95.7
#Mann= 6 , 1 , 0
  3042.8      .2       0  3335.4      .1       0  4908.9     .04       0
  4962.5     .04       0  5036.9     .04       0  5072.3     .08       0
#XS Ineff= 2 , 0
       0  4920.4   92.89               0
Permanent Ineff=
       F       F
Bank Sta=4962.5,5036.9
XS Rating Curve= 0
Exp/Cntr=.3,.1

Type RM Length L Ch R = 1 ,12568.1 ,1044.4,1025.4,1024.7
BEGIN DESCRIPTION:
Cross Section 12568.1
END DESCRIPTION:
XS GIS Cut Line= 4
      3047654.99     13849746.24       3047580.9     13850115.72
      3047573.06     13850433.67      3047575.76     13850573.66
#Sta/Elev= 29
  4306.1    89.5  4466.1      87  4506.1    85.8  4576.1    87.2    4683    86.4
    4863    86.2  4882.4   87.72    4903   89.15  4916.3   92.92  4917.2   93.18
  4929.4   94.22  4943.6   89.37  4958.1   88.63  4984.2   78.64  4993.5   70.99
  4994.8   70.46  5005.2   70.54  5006.1   70.83  5007.4   71.61    5008   74.22
    5014   78.77  5019.2   78.96  5024.2   80.59  5037.4   88.54  5048.9   87.35
    5051    87.3  5053.5   87.53    5101      92    5141    94.3
#Mann= 5 , 1 , 0
  4306.1      .1       0  4916.3     .04       0  4958.1     .04       0
  5037.4     .04       0  5053.5     .08       0
#XS Ineff= 2 , 0
       0  4929.4   94.22               0
Permanent Ineff=
       F       F
Bank Sta=4958.1,5037.4
XS Rating Curve= 0
Exp/Cntr=.3,.1

Type RM Length L Ch R = 1 ,11542.7 ,1186.8,1059.6,1058.3
BEGIN DESCRIPTION:
Cross Section 11542.7
END DESCRIPTION:
XS GIS Cut Line= 3
      3046607.94      13849845.1      3046547.98     13850410.68
      3046540.67     13850550.44
#Sta/Elev= 30
  4429.3    88.4  4449.3    87.4  4479.3    83.8  4489.3    83.2  4519.3    83.4
  4535.3   84.31  4549.3    85.1  4659.3      85  4689.3    84.4  4899.3      85
  4928.1   90.91  4936.9   91.38  4949.9   89.08    4963   84.47  4971.7   83.87
  4984.7   78.69  4991.6   73.78  4995.5   70.62  4996.3   69.28  4997.7   68.19
  5002.4   68.45  5003.7    69.2  5012.6   77.69    5019   78.05  5033.8   85.38
  5045.6   84.52  5069.7   87.94  5080.4   89.18  5109.4   89.28    5138    91.5
#Mann= 5 , 1 , 0
  4429.3      .1       0  4535.3     .08       0  4971.7     .04       0
  5033.8     .04       0  5069.7     .08       0
#XS Ineff= 2 , 0
       0    4937    91.3               0
Permanent Ineff=
       F       F
Bank Sta=4971.7,5033.8
XS Rating Curve= 0
Exp/Cntr=.3,.1

Type RM Length L Ch R = 1 ,10483.1 ,798.4,902.5,886.9
BEGIN DESCRIPTION:
Cross Section 10483.1
END DESCRIPTION:
XS GIS Cut Line= 3
       3045431.6     13848631.67       3045489.7     13850376.62
      3045484.09      13850536.5
#Sta/Elev= 29
    3253    86.2    3273    84.6    3293    82.3    3323    82.9    3343    81.9
    3573      82    3853      82    3943      85  3948.7   84.91    4103    82.4
    4193    84.2    4473    84.2    4863    82.3  4898.5   83.05  4943.1   82.55
  4973.2   81.37  4990.3   76.75  4998.5   67.71  4999.5   67.09    5002   68.33
  5002.5   68.99  5011.1   76.07  5025.3   82.23  5043.7   81.18  5081.8   84.73
  5124.5      88  5128.9    87.8  5138.9      89  5158.9    94.1
#Mann= 4 , 1 , 0
    3253     .99       0  3948.7     .08       0  4973.2     .04       0
  5025.3     .08       0
#XS Ineff= 2 , 0
       0    4470      90               0
Permanent Ineff=
       F       F
Bank Sta=4973.2,5025.3
XS Rating Curve= 0
Exp/Cntr=.3,.1

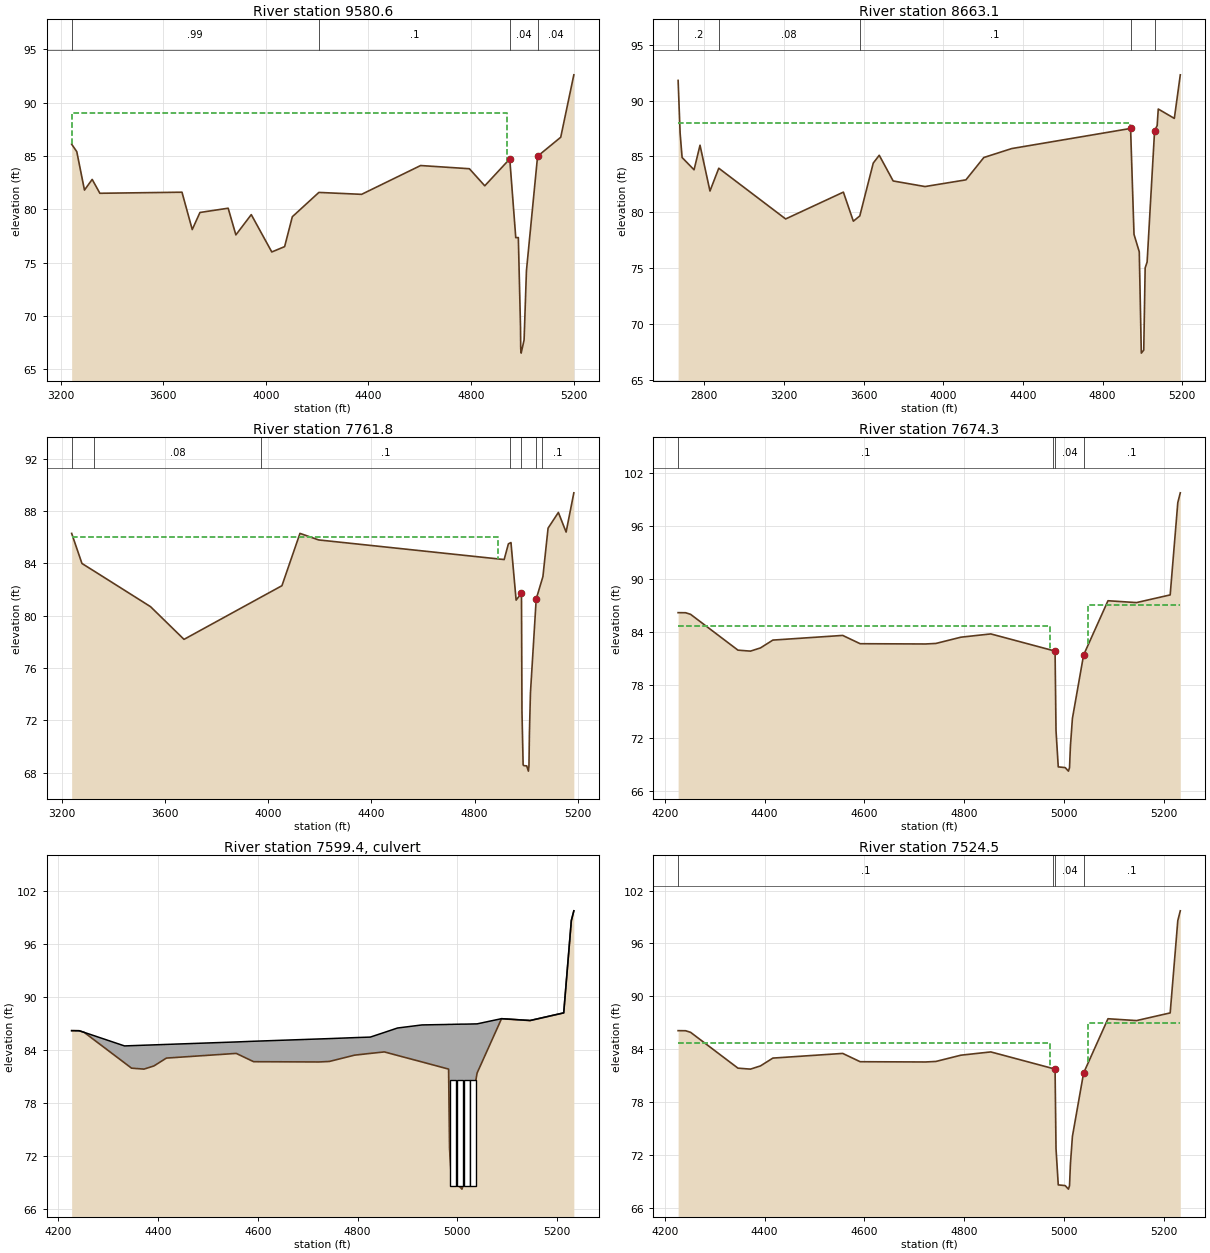
Type RM Length L Ch R = 1 ,9580.6  ,1250,917.5,915.4
BEGIN DESCRIPTION:
Cross Section 9580.6
END DESCRIPTION:
XS GIS Cut Line= 4
      3045022.12     13848615.46      3044613.49     13850027.48
       3044605.1     13850314.47      3044599.48     13850514.42
#Sta/Elev= 30
  3243.3    86.1  3263.3    85.4  3293.3    81.8  3323.3    82.8  3353.3    81.5
  3673.3    81.6  3713.3    78.1  3743.3    79.7  3853.3    80.1  3883.3    77.6
  3943.3    79.5  4023.3      76  4073.3    76.5  4103.3    79.3  4206.8   81.58
  4373.3    81.4  4603.3    84.1  4793.3    83.8  4853.3    82.2  4950.7   84.72
  4974.1   77.34  4984.1   77.35  4992.6   68.93  4993.4   66.93  4995.1   66.52
  5006.5   67.75  5015.7   74.25  5059.1   84.97  5149.3   86.75  5200.4    92.6
#Mann= 4 , 1 , 0
  3243.3     .99       0  4206.8      .1       0  4950.7     .04       0
  5059.1     .04       0
#XS Ineff= 2 , 0
       0    4940      89               0
Permanent Ineff=
       F       F
Bank Sta=4950.7,5059.1
XS Rating Curve= 0
Exp/Cntr=.3,.1

Type RM Length L Ch R = 1 ,8663.1  ,824.8,901.3,999.5
BEGIN DESCRIPTION:
Cross Section 8663.1
END DESCRIPTION:
XS GIS Cut Line= 5
      3044975.35     13848512.36      3044453.44     13849687.07
      3043713.17     13850103.92      3043694.11       13850300.
      3043673.66     13850488.89
#Sta/Elev= 30
  2667.9    91.8  2677.9    87.1  2687.9    84.9  2747.9    83.8  2777.9      86
  2827.9    81.9  2872.1   83.94  3207.9    79.4  3497.9    81.8  3547.9    79.2
  3580.3   79.67  3647.9    84.4  3677.9    85.1  3747.9    82.8  3907.9    82.3
  4113.3    82.9  4203.3    84.9  4343.3    85.7  4940.2    87.5  4957.4   78.02
  4983.8   76.46  4994.1   67.39  5006.3   67.66  5013.4   75.02  5023.2   75.54
  5060.7   87.28  5073.7   87.76  5079.2   89.24  5159.9    88.4  5189.9    92.3
#Mann= 5 , 1 , 0
  2667.9      .2       0  2872.1     .08       0  3580.3      .1       0
  4940.2     .04       0  5060.7     .08       0
#XS Ineff= 2 , 0
       0  4935.3      88               0
Permanent Ineff=
       F       F
Bank Sta=4940.2,5060.7
XS Rating Curve= 0
Exp/Cntr=.3,.1

Type RM Length L Ch R = 1 ,7761.8  ,90.3,87.5,87.3
BEGIN DESCRIPTION:
Cross Section 7761.8-INTERPOLATED
END DESCRIPTION:
XS GIS Cut Line= 6
      3044874.37     13848618.11      3044743.33     13848894.75
      3044453.12      13849479.2      3043717.53     13849444.94
      3043584.52     13849428.81      3043465.78     13849411.54
#Sta/Elev= 30
  3236.5    86.3  3276.5      84  3324.4   83.41  3542.6    80.7  3672.6    78.2
  3970.8   81.42  4052.6    82.3  4122.6    86.3  4195.1    85.8  4915.1    84.3
  4931.5    85.5  4938.3   85.57  4941.5    85.6  4961.5    81.2  4982.3   81.73
  4984.2   72.71  4988.7   68.61  4991.2   68.55  5002.6   68.53  5009.1   68.13
  5011.3   68.52  5013.1      71  5017.1   74.11  5039.5   81.29  5060.2   82.65
  5065.5      83  5085.5    86.7  5125.5    87.9  5155.5    86.4  5185.5    89.4
#Mann= 7 , 1 , 0
  3236.5      .2       0  3324.4     .08       0  3970.8      .1       0
  4938.3     .04       0  4982.3     .04       0  5039.5     .04       0
  5060.2      .1       0
#XS Ineff= 2 , 0
       0    4892      86               0
Permanent Ineff=
       F       F
Bank Sta=4982.3,5039.5
XS Rating Curve= 0
Exp/Cntr=.5,.3

Type RM Length L Ch R = 1 ,7674.3  ,149.8,149.8,149.8
BEGIN DESCRIPTION:
Upstream Section of Bridge/Culvert/Weir
END DESCRIPTION:
XS GIS Cut Line= 6
      3044410.75     13849357.56      3044319.13     13849399.64
      3043989.81     13849404.79      3043737.22      13849388.9
      3043608.66     13849346.33      3043447.66     13849252.17
#Sta/Elev= 28
  4226.5   86.16  4241.5   86.15  4251.5   85.97  4346.5   81.91  4371.5    81.8
  4391.5   82.16  4416.5   83.05  4556.5   83.58  4591.5   82.64  4722.8   82.61
  4743.4   82.67  4793.6   83.38  4853.5   83.75  4978.5   81.86  4982.3    81.8
  4984.2   72.78  4988.7   68.68  5002.6    68.6  5009.1    68.2  5011.3   68.59
  5013.1   71.07  5017.1   74.18  5039.5   81.36  5088.4   87.51  5145.5    87.3
  5213.1   88.17  5228.4   98.64  5233.4   99.74
#Mann= 4 , 1 , 0
  4226.5      .1       0  4978.5     .04       0  4982.3     .04       0
  5039.5      .1       0
#XS Ineff= 2 , 0
       0    4973    84.7    5049       0      87
Permanent Ineff=
       F       F
Bank Sta=4982.3,5039.5
XS Rating Curve= 0
Exp/Cntr=.5,.3

Type RM Length L Ch R = 2 ,7599.4  ,,,
BEGIN DESCRIPTION:
NORTH DAIRY ASHFORD ROAD
Structure ID: W67-8
END DESCRIPTION:
Bridge Culvert--1,0,-1,-1, 0
Deck Dist Width WeirC Skew NumUp NumDn MinLoCord MaxHiCord MaxSubmerge Is_Ogee
10,129.8,3,0, 36, 36, , , .95, 0, 1,1,,
  4226.5  4241.5  4251.5  4332.5  4346.5  4371.5  4391.5  4416.5  4556.5  4591.5
  4722.8  4743.4  4793.6  4825.2  4853.5  4879.8  4929.1  4978.5  4982.3  4984.2
  4988.7  4991.2  5002.6  5009.1  5011.3  5013.1  5017.1  5039.5  5088.4  5107.8
  5143.8  5145.5  5212.4  5213.1  5228.4  5233.4
   86.17   86.16   85.98   84.44   84.47   84.52   84.56   84.61   84.89   84.97
   85.23   85.27   85.38   85.44   85.97   86.47   86.82   86.87   86.88   86.88
   86.88   86.89    86.9   86.91   86.91   86.91   86.91   86.94   87.53   87.46
   87.33   87.32   88.18   88.18   98.65   99.75
   86.17   86.16   85.98   82.52   81.92   81.81   82.17   83.06   83.59   82.65
   82.62   82.68   83.39   83.59   83.76   83.36   82.62   81.87   81.81   72.79
   68.69   68.63   68.61   68.21    68.6   71.08   74.19   81.37   87.52   87.45
   87.32   87.31   88.17   88.18   98.65   99.75
  4226.5  4241.5  4251.5  4332.5  4346.5  4371.5  4391.5  4416.5  4556.5  4591.5
  4722.8  4743.4  4793.6  4825.2  4853.5  4879.8  4929.1  4978.5  4982.3  4984.2
  4988.7  4991.2  5002.6  5009.1  5011.3  5013.1  5017.1  5039.5  5088.4  5107.8
  5143.8  5145.5  5212.4  5213.1  5228.4  5233.4
   86.17   86.16   85.98   84.44   84.47   84.52   84.56   84.61   84.89   84.97
   85.23   85.27   85.38   85.44   85.97   86.47   86.82   86.87   86.88   86.88
   86.88   86.89    86.9   86.91   86.91   86.91   86.91   86.94   87.53   87.46
   87.33   87.32   88.18   88.18   98.65   99.75
   86.14   86.13   85.95   82.49   81.89   81.78   82.14   83.03   83.56   82.62
   82.59   82.65   83.36   83.56   83.73   83.33   82.59   81.84   81.78   72.76
   68.66    68.6   68.58   68.18   68.57   71.05   74.16   81.34   87.49   87.42
   87.29   87.28   88.14   88.15   98.62   99.72
BR Coef= 1 , 0 , 0 ,1.25, 0 ,,,.8,-1,2,0,
WSPro=,,,, 1 ,,,, 0 ,,,, 0 ,,,,-1 ,-1 ,-1 , 0 , 0 , 0 , 0 , 0
Culvert=2,12,12,129.8,.015,.4,1,8,1,68.6,4991.2,68.6,4991.2,Culvert #1  , 0 ,10
Culvert Bottom n=.015
Culvert=2,12,12,129.8,.015,.4,1,8,1,68.59,5004.9,68.59,5004.9,Culvert #2  , 0 ,10
Culvert Bottom n=.015
Culvert=2,12,12,129.8,.015,.4,1,8,1,68.58,5018.5,68.57,5018.5,Culvert #3  , 0 ,10
Culvert Bottom n=.015
Culvert=2,12,12,129.8,.015,.4,1,8,1,68.58,5031.3,68.58,5031.3,Culvert #4  , 0 ,10
Culvert Bottom n=.015
BR U #Sta/Elev= 36
  4226.5   86.17  4241.5   86.16  4251.5   85.98  4332.5   82.52  4346.5   81.92
  4371.5   81.81  4391.5   82.17  4416.5   83.06  4556.5   83.59  4591.5   82.65
  4722.8   82.62  4743.4   82.68  4793.6   83.39  4825.2   83.59  4853.5   83.76
  4879.8   83.36  4929.1   82.62  4978.5   81.87  4982.3   81.81  4984.2   72.79
  4988.7   68.69  4991.2   68.63  5002.6   68.61  5009.1   68.21  5011.3    68.6
  5013.1   71.08  5017.1   74.19  5039.5   81.37  5088.4   87.52  5107.8   87.45
  5143.8   87.32  5145.5   87.31  5212.4   88.17  5213.1   88.18  5228.4   98.65
  5233.4   99.75
BR U #Mann= 4
  4226.5      .1  4978.5     .04  4982.3     .04  5039.5      .1
BR U Banks=4982.3,5039.5
BR D #Sta/Elev= 36
  4226.5   86.14  4241.5   86.13  4251.5   85.95  4332.5   82.49  4346.5   81.89
  4371.5   81.78  4391.5   82.14  4416.5   83.03  4556.5   83.56  4591.5   82.62
  4722.8   82.59  4743.4   82.65  4793.6   83.36  4825.2   83.56  4853.5   83.73
  4879.8   83.33  4929.1   82.59  4978.5   81.84  4982.3   81.78  4984.2   72.76
  4988.7   68.66  4991.2    68.6  5002.6   68.58  5009.1   68.18  5011.3   68.57
  5013.1   71.05  5017.1   74.16  5039.5   81.34  5088.4   87.49  5107.8   87.42
  5143.8   87.29  5145.5   87.28  5212.4   88.14  5213.1   88.15  5228.4   98.62
  5233.4   99.72
BR D #Mann= 4
  4226.5      .1  4978.5     .04  4982.3     .04  5039.5      .1
BR D Banks=4982.3,5039.5
BC Design=,, 0 ,, 0 ,,,,,,
BC HTab HWMax=99.74

Type RM Length L Ch R = 1 ,7524.5  ,169.1,169.1,169.1
BEGIN DESCRIPTION:
Downstream Section of Bridge/Culvert/Weir
END DESCRIPTION:
XS GIS Cut Line= 6
      3044418.19     13849207.94      3044326.57     13849250.02
      3043997.25     13849255.17      3043744.66     13849239.28
       3043616.1     13849196.71       3043455.1     13849102.56
#Sta/Elev= 28
  4226.5   86.12  4241.5   86.11  4251.5   85.93  4346.5   81.87  4371.5   81.76
  4391.5   82.12  4416.5   83.01  4556.5   83.54  4591.5    82.6  4722.8   82.57
  4743.4   82.63  4793.6   83.34  4853.5   83.71  4978.5   81.82  4982.3   81.76
  4984.2   72.74  4988.7   68.64  5002.6   68.56  5009.1   68.16  5011.3   68.55
  5013.1   71.03  5017.1   74.14  5039.5   81.32  5088.4   87.47  5145.5   87.26
  5213.1   88.13  5228.4    98.6  5233.4    99.7
#Mann= 4 , 1 , 0
  4226.5      .1       0  4978.5     .04       0  4982.3     .04       0
  5039.5      .1       0
#XS Ineff= 2 , 0
       0    4973    84.7    5049       0      87
Permanent Ineff=
       F       F
Bank Sta=4982.3,5039.5
XS Rating Curve= 0
Exp/Cntr=.5,.3

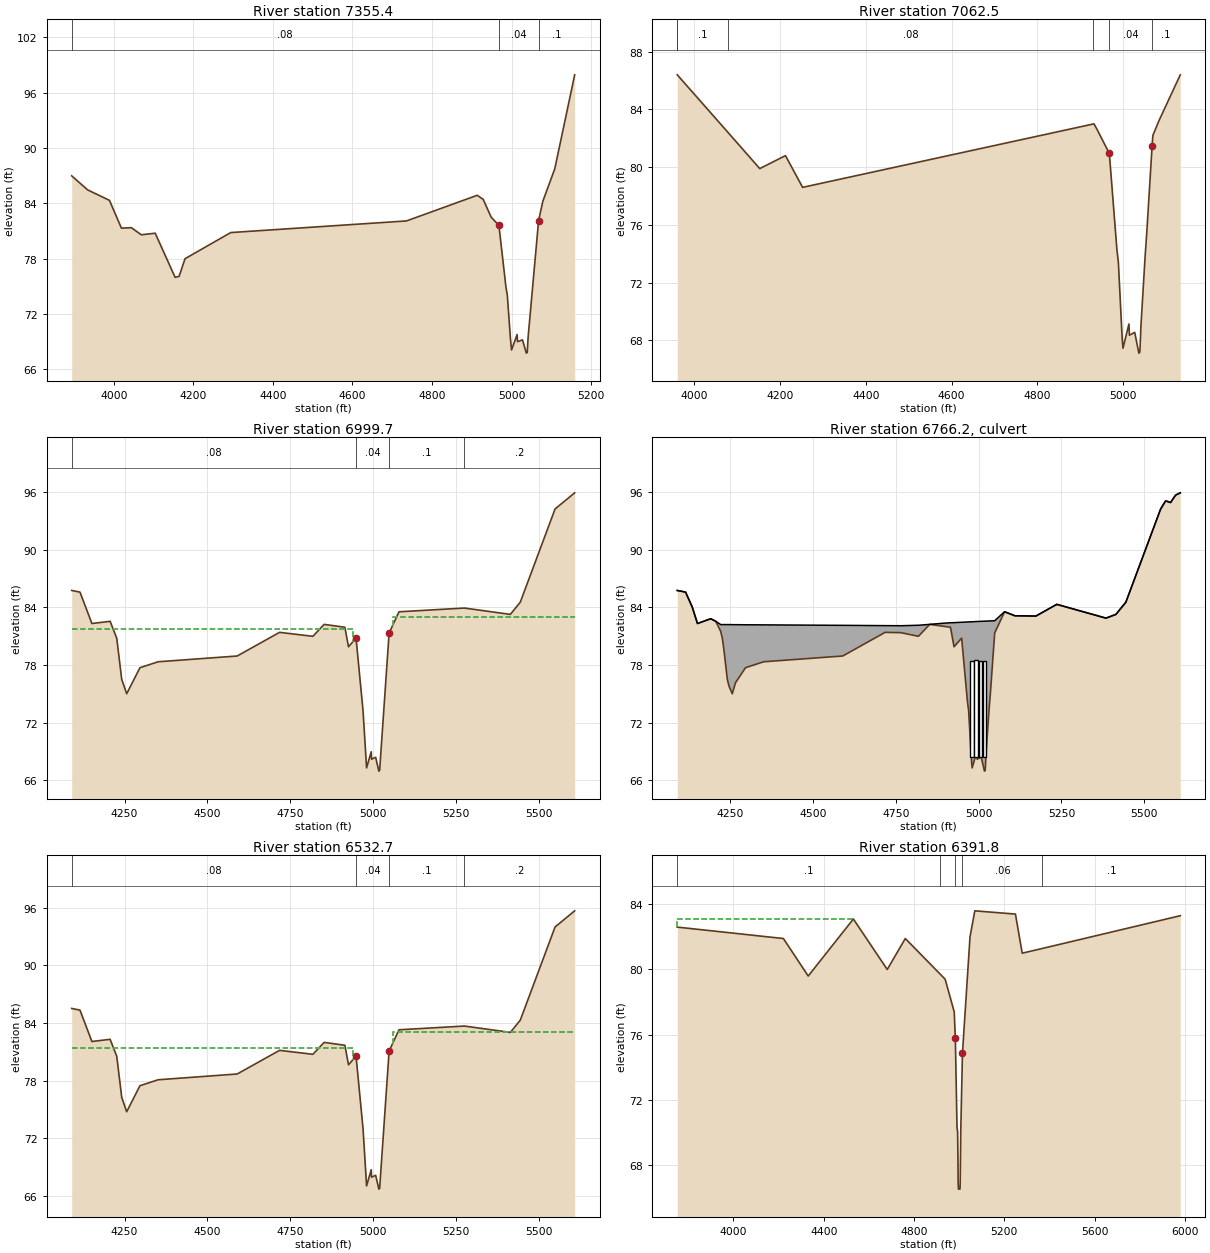
Type RM Length L Ch R = 1 ,7355.4  ,285.1,292.9,304.3
BEGIN DESCRIPTION:
Cross Section 7355.4-INTERPOLATED
END DESCRIPTION:
XS GIS Cut Line= 5
      3044689.04      13848679.1      3044363.22     13848857.89
      3043788.13     13849014.68      3043552.04     13849047.69
       3043499.1     13849022.84
#Sta/Elev= 30
  3894.1   86.99  3934.1   85.47  3989.1   84.33  4019.1   81.32  4044.1   81.37
  4069.1    80.6  4104.1   80.77  4154.1   75.99  4164.1   76.09  4179.1   78.01
  4294.1   80.84  4735.8    82.1  4913.7   84.88  4928.7   84.44  4948.7   82.51
  4968.2   81.61  4985.9   74.93  4989.3   74.06  4997.3   69.27    5000   68.11
    5014   69.79    5015   69.01  5027.4   69.21  5037.1   67.77  5039.4   67.84
  5041.7   69.54    5068   82.14  5078.7   84.24  5108.7   87.76  5158.7   97.94
#Mann= 3 , 1 , 0
  3894.1     .08       0  4968.2     .04       0    5068      .1       0
#XS Ineff= 2 , 0
       0  4913.7   84.88               0
Permanent Ineff=
       F       F
Bank Sta=4968.2,5068
XS Rating Curve= 0
Exp/Cntr=.3,.1

Type RM Length L Ch R = 1 ,7062.5  ,65.4,62.8,59
BEGIN DESCRIPTION:
Cross Section 7062.5-INTERPOLATED
END DESCRIPTION:
XS GIS Cut Line= 6
      3044686.77     13848644.82      3044602.84     13848702.97
      3044514.05     13848719.76      3043727.04     13848747.22
      3043583.41     13848738.97       3043542.3      13848767.4
#Sta/Elev= 27
  3959.9    86.4  4079.1   82.38  4152.4    79.9  4212.4    80.8  4252.4    78.6
    4929   82.98  4932.4      83  4939.8    82.6  4968.2   80.95  4985.9   74.27
  4989.3    73.4  4997.3   68.61  4998.3   68.07    5000   67.45    5014   69.13
    5015   68.35  5027.4   68.55  5037.1   67.11  5039.4   67.18  5041.4   68.53
  5041.7   68.88  5051.6   73.78  5055.7   75.53    5068   81.48  5069.8    82.2
  5083.7    83.2  5133.7    86.4
#Mann= 6 , 1 , 0
  3959.9      .2       0  3959.9      .1       0  4079.1     .08       0
    4929     .04       0  4968.2     .04       0    5068      .1       0
#XS Ineff= 2 , 0
       0  4932.4      83               0
Permanent Ineff=
       F       F
Bank Sta=4968.2,5068
XS Rating Curve= 0
Exp/Cntr=.5,.3

Type RM Length L Ch R = 1 ,6999.7  ,467,467,467
BEGIN DESCRIPTION:
Upstream Section of Bridge/Culvert/Weir
END DESCRIPTION:
XS GIS Cut Line= 3
      3044583.31     13848693.58      3043680.37     13848691.43
      3043065.69     13848664.79
#Sta/Elev= 30
  4090.4   85.76  4115.4   85.59  4151.4   82.32  4206.4   82.55  4226.4   80.79
  4241.4   76.52  4256.4   75.01  4296.4   77.72  4351.4   78.34  4589.9   78.94
  4717.8    81.4  4818.4   80.99  4852.4   82.23    4915   81.93  4925.9    79.9
  4948.7    80.8  4969.8   73.25  4980.5    67.3  4994.5   68.98  4995.5    68.2
  5007.9    68.4  5017.6   66.96  5019.9   67.03  5048.5   81.33  5078.3   83.54
  5275.7   83.93  5414.4   83.27  5444.4   84.54  5549.4   94.24  5608.6   95.92
#Mann= 4 , 1 , 0
  4090.4     .08       0  4948.7     .04       0  5048.5      .1       0
  5275.7      .2       0
#XS Ineff= 2 , 0
       0    4938    81.7    5059       0      83
Permanent Ineff=
       F       F
Bank Sta=4948.7,5048.5
XS Rating Curve= 0
Exp/Cntr=.5,.3

Type RM Length L Ch R = 2 ,6766.2  ,,,
BEGIN DESCRIPTION:
KATY FREEWAY (INTERSTATE 10)
Structure ID: W67-7
END DESCRIPTION:
Bridge Culvert--1,0,-1,-1, 0
Deck Dist Width WeirC Skew NumUp NumDn MinLoCord MaxHiCord MaxSubmerge Is_Ogee
10,447,3,0, 59, 59, , , .95, 0, 1,1,,
  4090.4  4115.4  4135.4  4151.4  4182.3  4191.4  4206.4  4221.4  4226.4  4231.4
  4241.4  4246.4  4256.4  4266.4  4296.4  4351.4  4589.9  4717.8  4764.2  4766.2
  4818.4  4818.8  4852.4  4854.5  4904.9    4915  4925.9  4948.7  4966.5  4969.8
  4977.8  4978.8  4980.5  4994.5  4995.5  5007.9  5017.6  5019.9    5022  5022.2
  5032.1  5036.2  5048.5  5078.3  5109.5  5113.6  5172.7  5172.9  5235.9  5236.8
  5275.7  5384.4  5414.4  5444.4  5549.4  5564.4  5579.4  5594.4  5608.6
   85.74   85.57   84.03    82.3   82.69    82.8   82.54   82.19   82.19   82.19
   82.19   82.19   82.18   82.18   82.17   82.16   82.11   82.08   82.07   82.07
   82.12   82.12   82.21   82.22   82.36   82.38   82.39   82.43   82.46   82.47
   82.48   82.48   82.48   82.51   82.51   82.53   82.54   82.55   82.55   82.55
   82.57   82.57   82.59   83.53   83.11   83.11   83.08   83.08    84.3   84.29
   83.91   82.86   83.25   84.52   94.22   95.06   94.89   95.66    95.9
   85.74   85.57   84.03    82.3   82.68   82.79   82.53   81.49   80.77   79.51
    76.5    75.8   74.99   76.15    77.7   78.32   78.92   81.38   81.35   81.34
   80.97   80.98   82.21    82.2   81.96   81.91   79.88   80.78    74.1   73.23
   68.44    67.9   67.28   68.96   68.18   68.38   66.94   67.01   68.36   68.71
   73.61   75.36   81.31   83.52    83.1    83.1   83.07   83.07   84.29   84.28
   83.91   82.86   83.25   84.52   94.22   95.06   94.89   95.66    95.9
  4090.4  4115.4  4135.4  4151.4  4182.3  4191.4  4206.4  4221.4  4226.4  4231.4
  4241.4  4246.4  4256.4  4266.4  4296.4  4351.4  4589.9  4717.8  4764.2  4766.2
  4818.4  4818.8  4852.4  4854.5  4904.9    4915  4925.9  4948.7  4966.5  4969.8
  4977.8  4978.8  4980.5  4994.5  4995.5  5007.9  5017.6  5019.9    5022  5022.2
  5032.1  5036.2  5048.5  5078.3  5109.5  5113.6  5172.7  5172.9  5235.9  5236.8
  5275.7  5384.4  5414.4  5444.4  5549.4  5564.4  5579.4  5594.4  5608.6
   85.74   85.57   84.03    82.3   82.69    82.8   82.54   82.19   82.19   82.19
   82.19   82.19   82.18   82.18   82.17   82.16   82.11   82.08   82.07   82.07
   82.12   82.12   82.21   82.22   82.36   82.38   82.39   82.43   82.46   82.47
   82.48   82.48   82.48   82.51   82.51   82.53   82.54   82.55   82.55   82.55
   82.57   82.57   82.59   83.53   83.11   83.11   83.08   83.08    84.3   84.29
   83.91   82.86   83.25   84.52   94.22   95.06   94.89   95.66    95.9
   85.51   85.34    83.8   82.07   82.45   82.56    82.3   81.26   80.54   79.28
   76.27   75.57   74.76   75.92   77.47   78.09   78.69   81.15   81.12   81.11
   80.74   80.75   81.98   81.97   81.73   81.68   79.65   80.55   73.87      73
   68.21   67.67   67.05   68.73   67.95   68.15   66.71   66.78   68.13   68.48
   73.38   75.13   81.08   83.29   82.87   82.87   82.84   82.84   84.06   84.05
   83.68   82.63   83.02   84.29   93.99   94.83   94.66   95.43   95.67
BR Coef= 1 , 0 , 0 ,1.25, 0 ,,,.8,-1,2,0,
WSPro=,,,, 1 ,,,, 0 ,,,, 0 ,,,,-1 ,-1 ,-1 , 0 , 0 , 0 , 0 , 0
Culvert=2,10,10,447,.015,.4,1,8,1,68.4,4979.9,67.91,4979.9,Culvert #1  , 0 ,10
Culvert Bottom n=.015
Culvert=2,10,10,447,.015,.4,1,8,1,68.46,4992.1,67.94,4992.1,Culvert #2  , 0 ,10
Culvert Bottom n=.015
Culvert=2,10,10,447,.015,.4,1,8,1,68.45,5004.8,67.99,5004.8,Culvert #3  , 0 ,10
Culvert Bottom n=.015
Culvert=2,10,10,447,.015,.4,1,8,1,68.45,5017,67.95,5017,Culvert #4  , 0 ,10
Culvert Bottom n=.015
BR U #Sta/Elev= 59
  4090.4   85.74  4115.4   85.57  4135.4   84.03  4151.4    82.3  4182.3   82.68
  4191.4   82.79  4206.4   82.53  4221.4   81.49  4226.4   80.77  4231.4   79.51
  4241.4    76.5  4246.4    75.8  4256.4   74.99  4266.4   76.15  4296.4    77.7
  4351.4   78.32  4589.9   78.92  4717.8   81.38  4764.2   81.35  4766.2   81.34
  4818.4   80.97  4818.8   80.98  4852.4   82.21  4854.5    82.2  4904.9   81.96
    4915   81.91  4925.9   79.88  4948.7   80.78  4966.5    74.1  4969.8   73.23
  4977.8   68.44  4978.8    67.9  4980.5   67.28  4994.5   68.96  4995.5   68.18
  5007.9   68.38  5017.6   66.94  5019.9   67.01    5022   68.36  5022.2   68.71
  5032.1   73.61  5036.2   75.36  5048.5   81.31  5078.3   83.52  5109.5    83.1
  5113.6    83.1  5172.7   83.07  5172.9   83.07  5235.9   84.29  5236.8   84.28
  5275.7   83.91  5384.4   82.86  5414.4   83.25  5444.4   84.52  5549.4   94.22
  5564.4   95.06  5579.4   94.89  5594.4   95.66  5608.6    95.9
BR U #Mann= 4
  4090.4     .08  4948.7     .04  5048.5      .1  5275.7      .2
BR U Banks=4948.7,5048.5
BR D #Sta/Elev= 59
  4090.4   85.51  4115.4   85.34  4135.4    83.8  4151.4   82.07  4182.3   82.45
  4191.4   82.56  4206.4    82.3  4221.4   81.26  4226.4   80.54  4231.4   79.28
  4241.4   76.27  4246.4   75.57  4256.4   74.76  4266.4   75.92  4296.4   77.47
  4351.4   78.09  4589.9   78.69  4717.8   81.15  4764.2   81.12  4766.2   81.11
  4818.4   80.74  4818.8   80.75  4852.4   81.98  4854.5   81.97  4904.9   81.73
    4915   81.68  4925.9   79.65  4948.7   80.55  4966.5   73.87  4969.8      73
  4977.8   68.21  4978.8   67.67  4980.5   67.05  4994.5   68.73  4995.5   67.95
  5007.9   68.15  5017.6   66.71  5019.9   66.78    5022   68.13  5022.2   68.48
  5032.1   73.38  5036.2   75.13  5048.5   81.08  5078.3   83.29  5109.5   82.87
  5113.6   82.87  5172.7   82.84  5172.9   82.84  5235.9   84.06  5236.8   84.05
  5275.7   83.68  5384.4   82.63  5414.4   83.02  5444.4   84.29  5549.4   93.99
  5564.4   94.83  5579.4   94.66  5594.4   95.43  5608.6   95.67
BR D #Mann= 4
  4090.4     .08  4948.7     .04  5048.5      .1  5275.7      .2
BR D Banks=4948.7,5048.5
BC Design=,, 0 ,, 0 ,,,,,,
BC HTab HWMax=95.92

Type RM Length L Ch R = 1 ,6532.7  ,140.9,140.9,140.9
BEGIN DESCRIPTION:
Downstream Section of Bridge/Culvert/Weir
END DESCRIPTION:
XS GIS Cut Line= 3
      3044594.57     13848226.72      3043691.63     13848224.57
      3043076.95     13848197.93
#Sta/Elev= 30
  4090.4    85.5  4115.4   85.33  4151.4   82.06  4206.4   82.29  4226.4   80.53
  4241.4   76.26  4256.4   74.75  4296.4   77.46  4351.4   78.08  4589.9   78.68
  4717.8   81.14  4818.4   80.73  4852.4   81.97    4915   81.67  4925.9   79.64
  4948.7   80.54  4969.8   72.99  4980.5   67.04  4994.5   68.72  4995.5   67.94
  5007.9   68.14  5017.6    66.7  5019.9   66.77  5048.5   81.07  5078.3   83.28
  5275.7   83.67  5414.4   83.01  5444.4   84.28  5549.4   93.98  5608.6   95.66
#Mann= 4 , 1 , 0
  4090.4     .08       0  4948.7     .04       0  5048.5      .1       0
  5275.7      .2       0
#XS Ineff= 2 , 0
       0    4938    81.4    5059       0      83
Permanent Ineff=
       F       F
Bank Sta=4948.7,5048.5
XS Rating Curve= 0
Exp/Cntr=.5,.3

Type RM Length L Ch R = 1 ,6391.8  ,1014.7,921.4,913
BEGIN DESCRIPTION:
Cross Section 6391.8-INTERPOLATED
END DESCRIPTION:
XS GIS Cut Line= 4
      3044784.93     13848136.82      3043599.59     13848083.41
      3043541.55     13848201.12      3042631.62     13848189.11
#Sta/Elev= 26
  3751.3    82.6  4221.3    81.9  4331.3    79.6  4531.3    83.1  4681.3      80
  4761.3    81.9  4914.7   79.73  4937.9    79.4  4977.9    77.4  4982.9   75.79
  4990.3   70.32  4992.9   70.06  4994.8   68.05  4995.2      67  4996.5   66.52
  5003.6   66.52  5004.4   66.92  5005.2   67.83    5007   70.13  5014.4   74.86
  5047.9      82  5069.1    83.6  5249.1    83.4  5279.1      81  5368.3   81.29
  5979.1    83.3
#Mann= 5 , 1 , 0
  3751.3      .1       0  4914.7     .06       0  4982.9     .04       0
  5014.4     .06       0  5368.3      .1       0
#XS Ineff= 2 , 0
       0  4531.3    83.1               0
Permanent Ineff=
       F       F
Bank Sta=4982.9,5014.4
XS Rating Curve= 0
Exp/Cntr=.3,.1