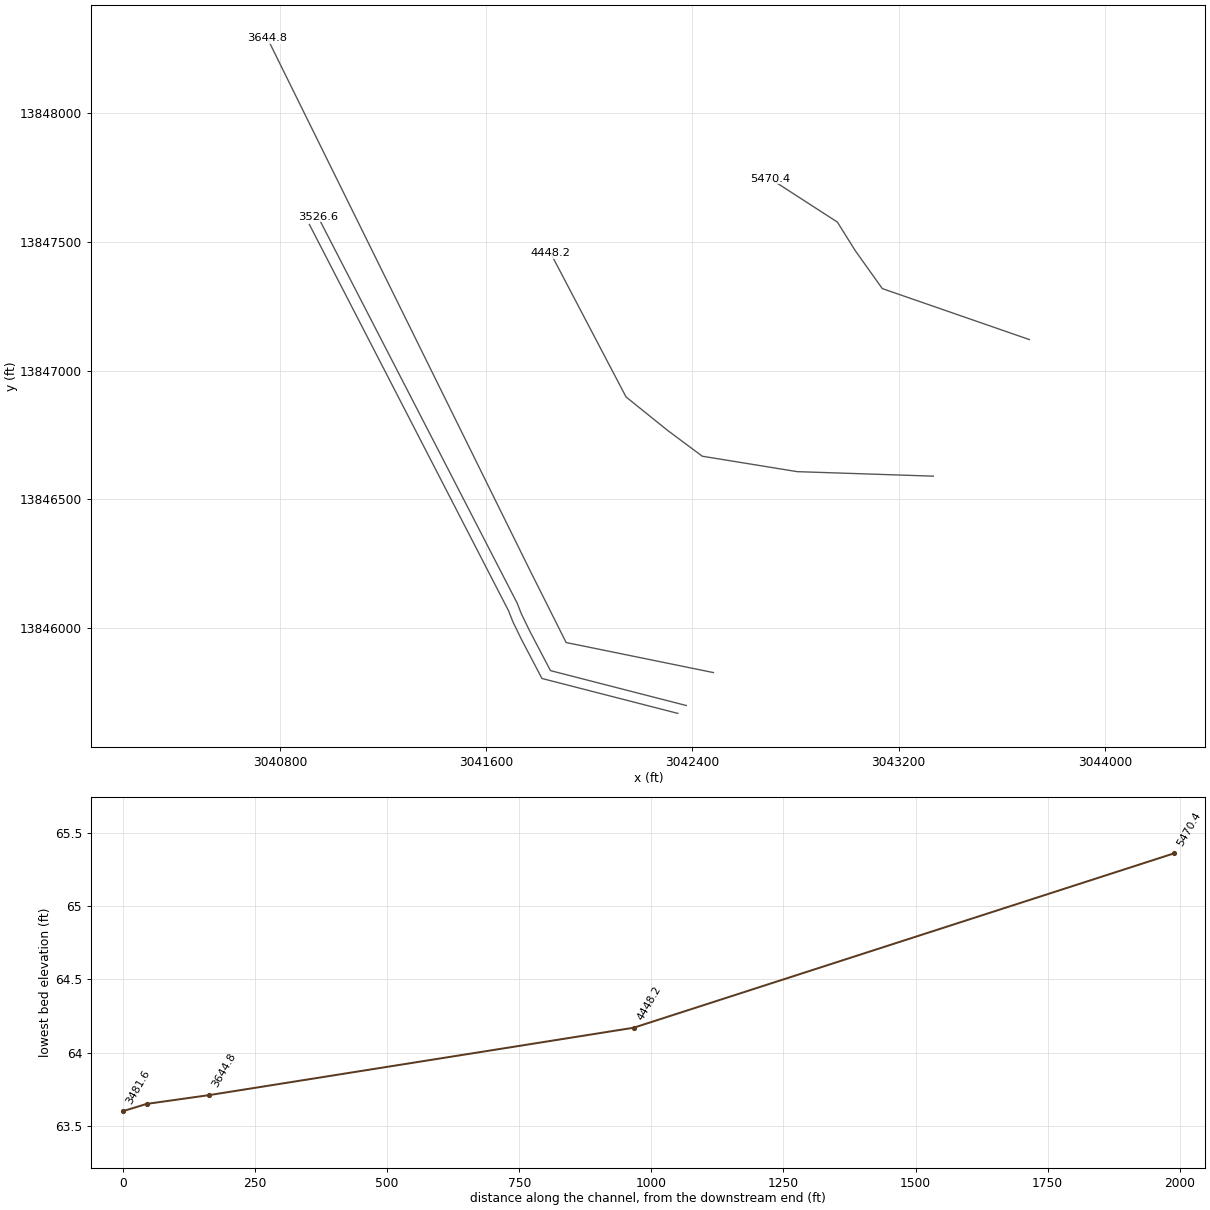
HEC-RAS study W167-00-00pp.prj: W167-00-00

--- W167-00-00pp.g01 (geometry) --- (continued)

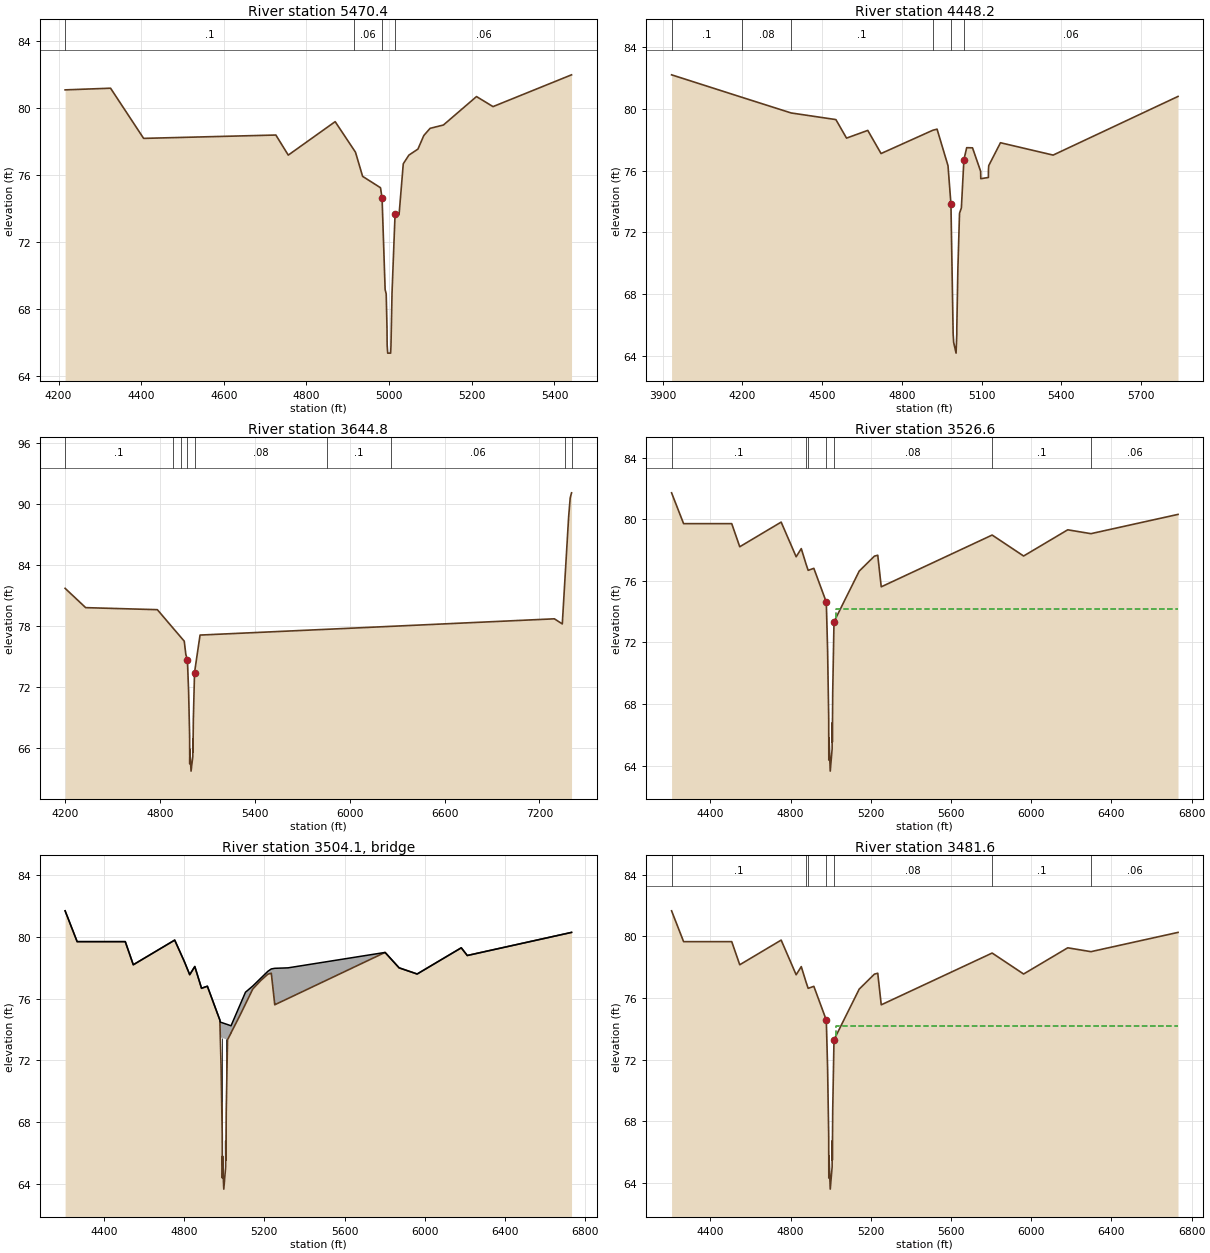
Type RM Length L Ch R = 1 ,5470.4  ,975.7,1022.2,1077.2
BEGIN DESCRIPTION:
Cross Section 5470.4
END DESCRIPTION:
XS GIS Cut Line= 5
       3043706.5     13847121.25      3043136.37     13847319.31
      3043032.18     13847465.67      3042962.07     13847577.85
      3042701.79     13847746.26
#Sta/Elev= 30
  4215.9    81.1  4325.9    81.2  4405.9    78.2  4725.9    78.4  4755.9    77.2
  4869.4    79.2  4914.9   77.51  4918.6   77.37  4935.8   75.93  4979.1   75.25
  4982.9   74.63  4990.3   69.16  4992.9    68.9  4994.8   66.89  4995.2   65.84
  4996.5   65.36  5003.6   65.36  5004.4   65.76    5007   68.97  5014.4    73.7
    5024   73.63  5034.2   76.68  5047.8    77.2  5069.7   77.56  5083.9   78.37
  5099.1    78.8  5131.4      79  5211.4    80.7  5251.4    80.1  5441.4      82
#Mann= 4 , 1 , 0
  4215.9      .1       0  4914.9     .06       0  4982.9     .04       0
  5014.4     .06       0
Bank Sta=4982.9,5014.4
XS Rating Curve= 0
Exp/Cntr=.3,.1

Type RM Length L Ch R = 1 ,4448.2  ,852,803.4,645.9
BEGIN DESCRIPTION:
Cross Section 4448.2
END DESCRIPTION:
XS GIS Cut Line= 6
      3043334.28     13846590.35      3042806.21     13846607.86
      3042438.24     13846667.82      3042304.68     13846767.39
      3042142.58     13846898.11      3041850.46     13847456.28
#Sta/Elev= 30
  3933.4    82.2  4198.8   80.74  4383.3   79.73  4551.8    79.3  4591.8    78.1
  4671.8    78.6  4721.8    77.1  4916.7   78.61  4932.6   78.68  4973.8   76.31
  4984.8   73.83  4993.1   65.42    4995   64.87  5004.1   64.17  5006.8   65.38
  5006.9    65.8  5010.9   69.62  5017.1   73.23  5024.1   73.58  5033.6    76.7
  5044.1   77.48    5066   77.47  5096.6   75.95  5097.1   75.47  5125.8   75.55
  5125.9   76.04  5127.1   76.32  5171.2    77.8  5369.4      77  5839.4    80.8
#Mann= 6 , 1 , 0
  3933.4      .1       0  4198.8     .08       0  4383.3      .1       0
  4916.7     .06       0  4984.8     .04       0  5033.6     .06       0
Bank Sta=4984.8,5033.6
XS Rating Curve= 0
Exp/Cntr=.3,.1

Type RM Length L Ch R = 1 ,3644.8  ,116.4,118.2,124.1
BEGIN DESCRIPTION:
Cross Section 3644.8-INTERPOLATED
END DESCRIPTION:
XS GIS Cut Line= 5
      3042481.46     13845826.96       3042481.4     13845826.96
      3041910.15     13845943.76       3041767.1     13846229.86
      3040751.62     13848291.89
#Sta/Elev= 29
  4201.3    81.7  4331.3    79.8  4784.4    79.6  4881.3   77.83    4933   76.89
  4954.4    76.5  4964.4    75.2  4974.4   74.68  4981.9   71.61  4988.4   67.23
  4989.1   64.43  4990.4   65.85    4991   65.39  4997.5   63.71  5008.5   65.15
  5008.9   66.84  5009.7   65.59    5012   68.82  5019.5    73.4  5034.4      75
  5054.4    77.1  5858.1   77.67  6261.9   77.96  7294.3    78.7  7344.3    78.2
  7358.7   81.98  7384.3    88.7  7394.3    90.6  7402.8    91.1
#Mann= 9 , 1 , 0
  4201.3      .1       0  4881.3     .06       0    4933     .08       0
  4974.4     .04       0  5019.5     .08       0  5858.1      .1       0
  6261.9     .06       0  7358.7      .1       0  7402.8      .2       0
Bank Sta=4974.4,5019.5
XS Rating Curve= 0
Exp/Cntr=.5,.3

Type RM Length L Ch R = 1 ,3526.6  ,45,45,45
BEGIN DESCRIPTION:
Upstream Section of Bridge/Culvert/Weir
END DESCRIPTION:
XS GIS Cut Line= 6
      3042376.22     13845698.92      3041849.49     13845834.55
      3041770.06     13845986.14       3041736.6     13846055.14
      3041720.08     13846097.25      3040947.58     13847598.82
#Sta/Elev= 30
  4206.6   81.71  4266.6   79.71  4506.6   79.71  4546.6   78.21  4753.1   79.81
 4827.96   77.56 4853.38   78.09  4877.6   77.07  4887.8   76.68  4916.1   76.81
 4978.24   74.62 4984.61   71.55 4990.14   67.17 4990.74   64.37 4991.84   65.79
 4997.88   63.65 5007.23   65.09 5007.57   66.78 5008.25   65.53  5010.2   68.76
 5016.58   73.34 5142.38   76.63 5218.03    77.6 5234.85   77.66  5252.2   75.61
  5805.3   78.97  5962.2   77.61  6182.2   79.31    6298   79.06  6732.2   80.31
#Mann= 7 , 1 , 0
  4206.6      .1       0  4877.6     .06       0  4887.8     .08       0
 4978.24     .04       0 5016.58     .08       0  5805.3      .1       0
    6298     .06       0
#XS Ineff= 2 , 0
       0    4970   74.86    5027       0    74.2
Permanent Ineff=
       F       F
Bank Sta=4978.24,5016.58
XS Rating Curve= 0
Exp/Cntr=.5,.3

Type RM Length L Ch R = 3 ,3504.1  ,,,
BEGIN DESCRIPTION:
ACCESS ROAD TO CEMETERY - 32 degree skew
Structure ID: W67-6
END DESCRIPTION:
Bridge Culvert--1,0,-1,-1, 0
Deck Dist Width WeirC Skew NumUp NumDn MinLoCord MaxHiCord MaxSubmerge Is_Ogee
10,25,2.6,0, 26, 26, , , .95, 0, 1,1,,
  4206.6  4266.6  4506.6  4546.6  4753.1 4800.34 4827.96 4853.38 4886.86  4916.1
 4978.24 4980.54 5016.58 5033.99  5106.1 5142.38 5218.03 5234.85  5252.2  5318.2
  5802.2  5872.2  5962.2  6182.2  6212.2  6732.2
    81.7    79.7    79.7    78.2    79.8   78.44   77.56   78.09   76.68   76.81
   74.62   74.48   74.32   74.24   76.42   76.82   77.78   77.93   77.97      78
      79      78    77.6    79.3    78.8    80.3
    81.7    79.7    79.7    78.2    79.8   78.43   77.55   78.08   76.67    76.8
   74.61    73.5   73.33   73.77   75.65   76.62   77.59   77.65    75.6   76.01
      79      78    77.6    79.3    78.8    80.3
  4206.6  4266.6  4506.6  4546.6  4753.1 4800.34 4827.96 4853.38 4886.86  4916.1
 4978.24 4980.54 5016.58 5033.99  5106.1 5142.38 5218.03 5234.85  5252.2  5318.2
  5802.2  5872.2  5962.2  6182.2  6212.2  6732.2
    81.7    79.7    79.7    78.2    79.8   78.44   77.56   78.09   76.68   76.81
   74.62   74.48   74.32   74.24   76.42   76.82   77.78   77.93   77.97      78
      79      78    77.6    79.3    78.8    80.3
   81.66   79.66   79.66   78.16   79.76   78.39   77.51   78.04   76.63   76.76
   74.57   73.46   73.29   73.73   75.61   76.58   77.55   77.61   75.56   75.97
   78.96   77.96   77.56   79.26   78.76   80.26
Pier Skew, UpSta & Num, DnSta & Num=  ,4990.8, 2 ,4990.8, 2 , 0 , 0 , 0 ,,
       1       1
   64.11   74.44
       1       1
   64.07    74.4
Pier Skew, UpSta & Num, DnSta & Num=  ,5007.6, 2 ,5007.6, 2 , 0 , 0 , 0 ,,
       1       1
   64.05   74.36
       1       1
   64.01   74.32
Abutment Skew #Up #Dn= , 2 , 2
 4980.34 4990.14
    73.5   67.16
 4980.34 4990.14
   73.46   67.12
BR Coef= 1 , 1 , 0 ,1.25, 0 ,,,.8,0,2,0,
WSPro=,,,, 1 ,,,, 0 ,,,, 0 ,,,,-1 ,-1 ,-1 , 0 , 0 , 0 , 0 , 0
BR U #Sta/Elev= 61
  4206.6    81.7  4266.6    79.7  4506.6    79.7  4546.6    78.2  4753.1    79.8
  4795.1   78.58 4800.34   78.43 4827.96   77.55  4838.1   77.76 4853.38   78.08
  4872.2   77.29  4877.6   77.06 4886.86   76.67  4887.8   76.67  4906.8   76.76
  4916.1    76.8  4964.2    75.1 4964.29    75.1  4964.4    75.1 4964.51   75.09
 4978.24   74.61 4980.45   73.54 4980.54    73.5 4984.61   71.54 4990.04   67.24
 4990.14   67.16 4990.74   64.36 4991.84   65.78 4992.35   65.32 4997.88   63.64
 5007.23   65.08 5007.57   66.77 5008.25   65.52  5010.2   68.75 5016.58   73.33
 5029.05   73.65 5029.13   73.65 5029.24   73.65 5033.99   73.77  5034.1   73.78
 5034.21   73.78  5034.4   73.79 5078.03    74.9  5106.1   75.65 5142.38   76.62
  5160.9   76.88 5181.82   77.17 5218.03   77.59  5228.9   77.63 5234.85   77.65
  5252.2    75.6  5254.8   75.62  5318.2   76.01  5802.2      79  5805.3   78.96
  5872.2      78  5962.2    77.6  6182.2    79.3  6212.2    78.8    6298   79.05
  6732.2    80.3
BR U #Mann= 7
  4206.6      .1  4877.6     .06  4887.8     .08 4978.24     .04 5016.58     .08
  5805.3      .1    6298     .06
BR U Banks=4978.24,5016.58
BR D #Sta/Elev= 61
  4206.6   81.66  4266.6   79.66  4506.6   79.66  4546.6   78.16  4753.1   79.76
  4795.1   78.54 4800.34   78.39 4827.96   77.51  4838.1   77.72 4853.38   78.04
  4872.2   77.25  4877.6   77.02 4886.86   76.63  4887.8   76.63  4906.8   76.72
  4916.1   76.76  4964.2   75.06 4964.29   75.06  4964.4   75.06 4964.51   75.05
 4978.24   74.57 4980.45    73.5 4980.54   73.46 4984.61    71.5 4990.04    67.2
 4990.14   67.12 4990.74   64.32 4991.84   65.74 4992.35   65.28 4997.88    63.6
 5007.23   65.04 5007.57   66.73 5008.25   65.48  5010.2   68.71 5016.58   73.29
 5029.05   73.61 5029.13   73.61 5029.24   73.61 5033.99   73.73  5034.1   73.74
 5034.21   73.74  5034.4   73.75 5078.03   74.86  5106.1   75.61 5142.38   76.58
  5160.9   76.84 5181.82   77.13 5218.03   77.55  5228.9   77.59 5234.85   77.61
  5252.2   75.56  5254.8   75.58  5318.2   75.97  5802.2   78.96  5805.3   78.92
  5872.2   77.96  5962.2   77.56  6182.2   79.26  6212.2   78.76    6298   79.01
  6732.2   80.26
BR D #Mann= 7
  4206.6      .1  4877.6     .06  4887.8     .08 4978.24     .04 5016.58     .08
  5805.3      .1    6298     .06
BR D Banks=4978.24,5016.58
BC Design=,, 0 ,, 0 ,,,,,,
BC HTab HWMax=81.71

Type RM Length L Ch R = 1 ,3481.6  ,168.9,168.9,168.9
BEGIN DESCRIPTION:
Downstream Section of Bridge/Culvert/Weir
END DESCRIPTION:
XS GIS Cut Line= 6
      3042343.15      13845668.4      3041816.43     13845804.03
        3041737.     13845955.62      3041703.54     13846024.62
      3041687.02     13846066.73      3040914.51      13847568.3
#Sta/Elev= 30
  4206.6   81.66  4266.6   79.66  4506.6   79.66  4546.6   78.16  4753.1   79.76
 4827.96   77.51 4853.38   78.04  4877.6   77.02  4887.8   76.63  4916.1   76.76
 4978.24   74.57 4984.61    71.5 4990.14   67.12 4990.74   64.32 4991.84   65.74
 4997.88    63.6 5007.23   65.04 5007.57   66.73 5008.25   65.48  5010.2   68.71
 5016.58   73.29 5142.38   76.58 5218.03   77.55 5234.85   77.61  5252.2   75.56
  5805.3   78.92  5962.2   77.56  6182.2   79.26    6298   79.01  6732.2   80.26
#Mann= 7 , 1 , 0
  4206.6      .1       0  4877.6     .06       0  4887.8     .08       0
 4978.24     .04       0 5016.58     .08       0  5805.3      .1       0
    6298     .06       0
#XS Ineff= 2 , 0
       0    4970   74.86    5027       0    74.2
Permanent Ineff=
       F       F
Bank Sta=4978.24,5016.58
XS Rating Curve= 0
Exp/Cntr=.5,.3