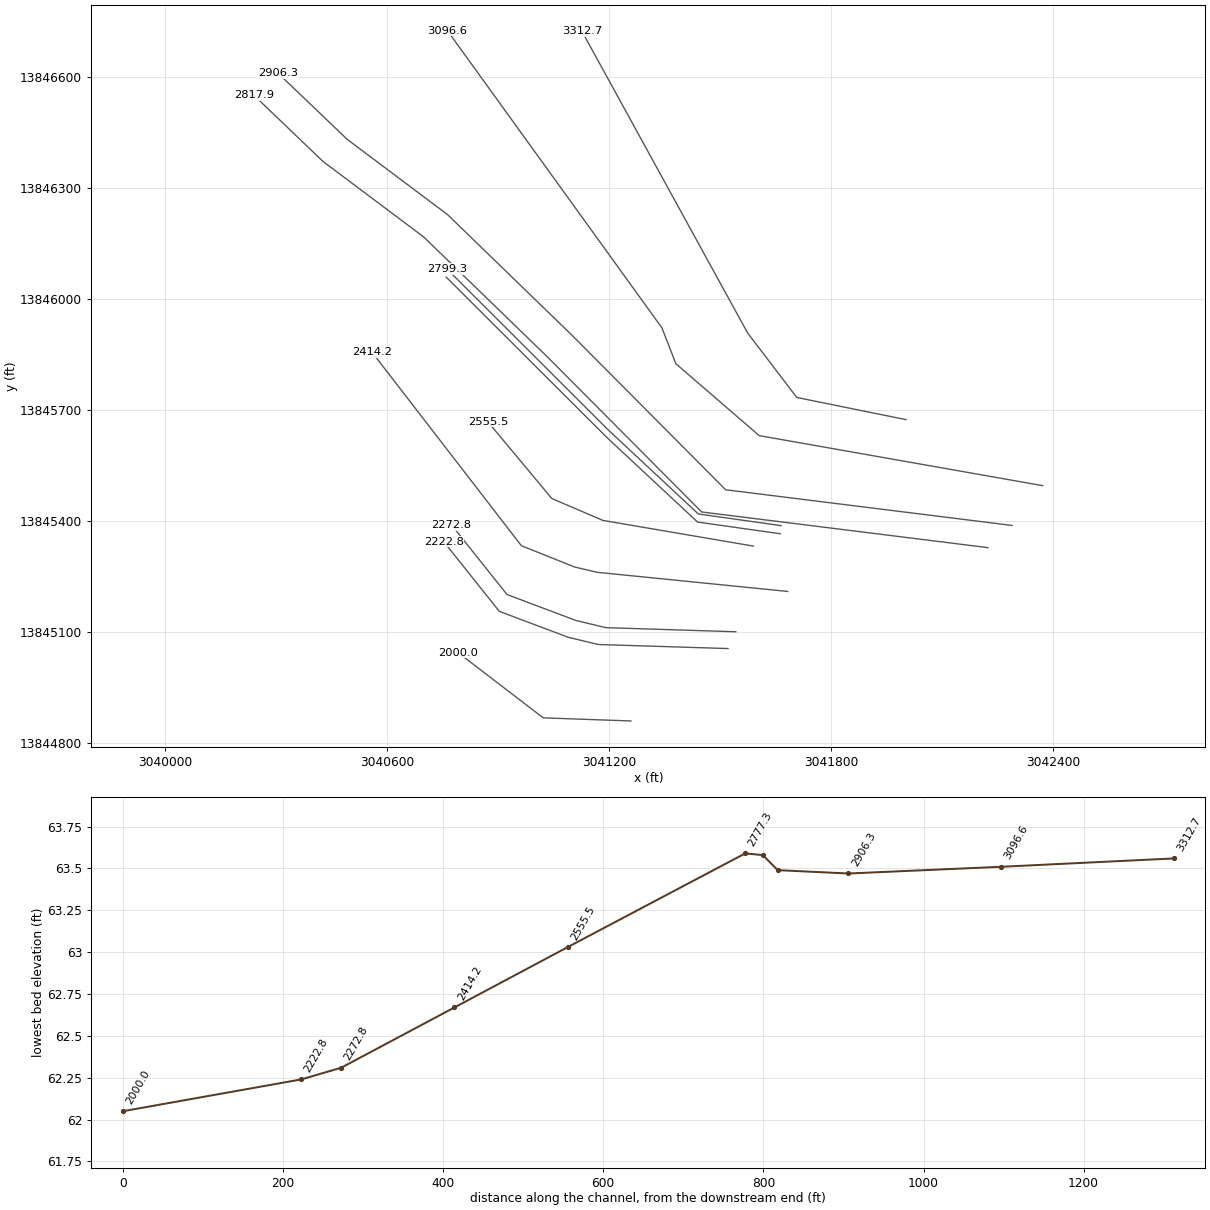
HEC-RAS study W167-00-00pp.prj: W167-00-00

--- W167-00-00pp.g01 (geometry) --- (continued)

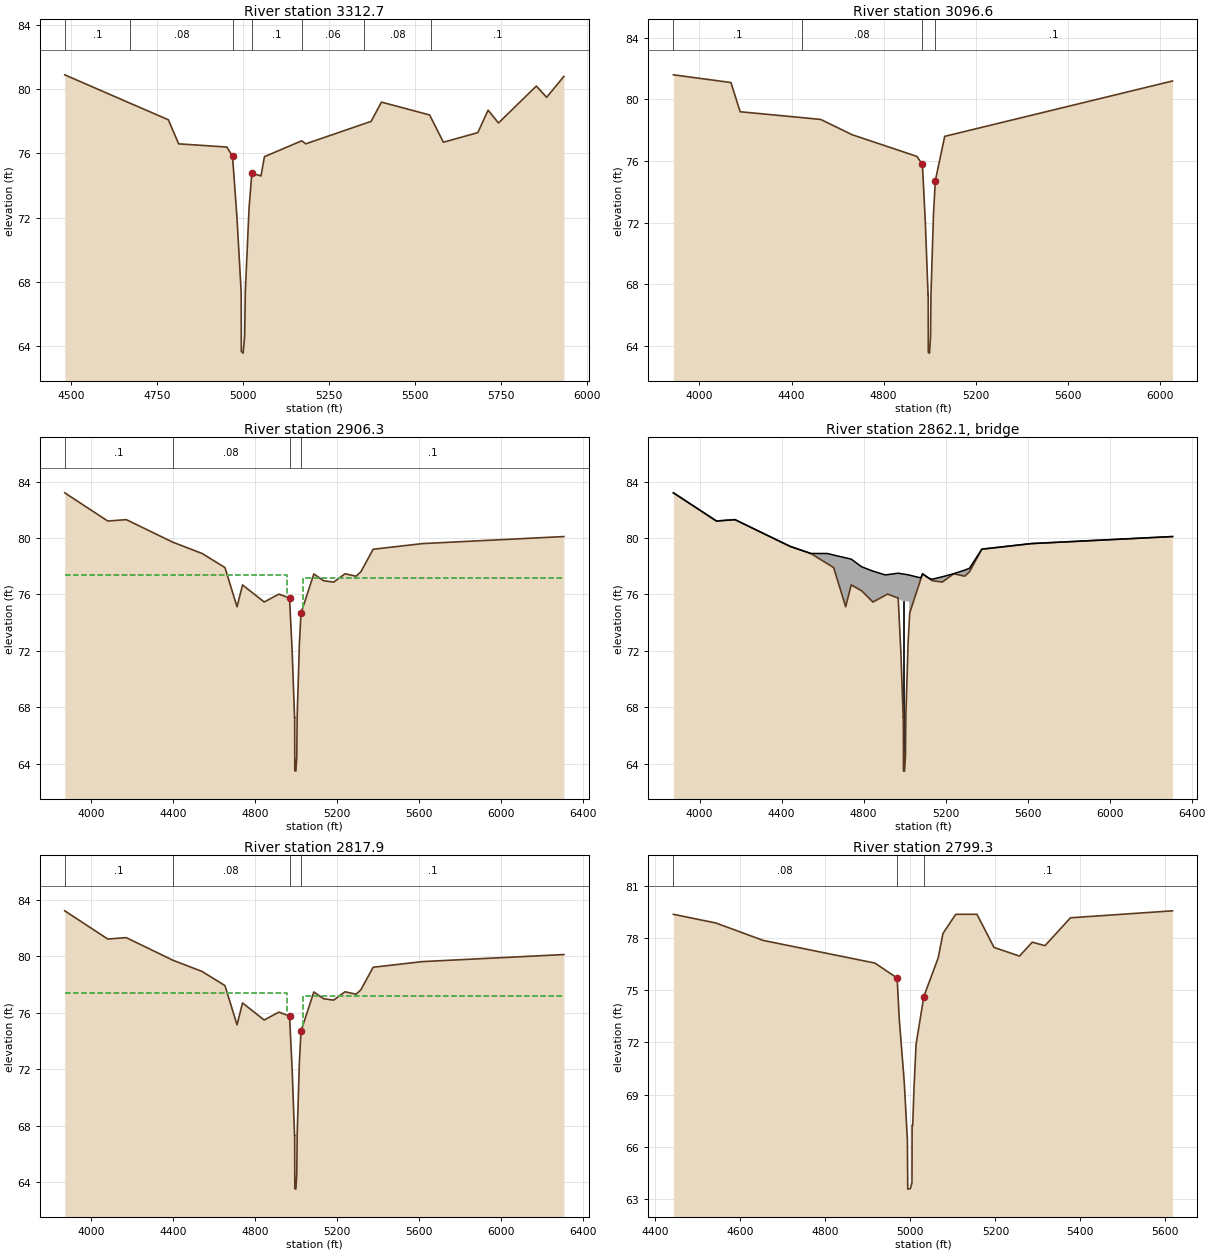
Type RM Length L Ch R = 1 ,3312.7  ,205.2,216.1,242.6
BEGIN DESCRIPTION:
Cross Section 3312.7-INTERPOLATED
END DESCRIPTION:
XS GIS Cut Line= 4
      3042001.96     13845673.07      3041706.95     13845732.96
      3041574.09     13845907.34      3041126.43     13846722.45
#Sta/Elev= 30
  4481.4    80.9  4671.4   79.13  4782.4    78.1  4812.4    76.6  4952.4    76.4
  4968.9   75.83  4981.7   72.05    4994   67.38  4994.5   63.67  4999.7   63.56
  5004.2   64.62  5006.1   67.43    5017   72.61    5025   74.77  5051.6    74.6
  5061.6    75.8    5170   76.79  5181.6    76.6  5351.2   77.85  5371.6      78
  5401.6    79.2  5541.6    78.4  5546.5   78.19  5581.6    76.7  5681.6    77.3
  5711.6    78.7  5741.6    77.9  5851.6    80.2  5881.6    79.5  5931.6    80.8
#Mann= 7 , 1 , 0
  4481.4      .1       0  4671.4     .08       0  4968.9     .04       0
    5025      .1       0    5170     .06       0  5351.2     .08       0
  5546.5      .1       0
#XS Ineff= 2 , 0
       0                  5541.6       0    78.4
Permanent Ineff=
       F       F
Bank Sta=4968.9,5025
XS Rating Curve= 0
Exp/Cntr=.3,.1

Type RM Length L Ch R = 1 ,3096.6  ,179.7,190.3,209.7
BEGIN DESCRIPTION:
Cross Section 3096.6-INTERPOLATED
END DESCRIPTION:
XS GIS Cut Line= 5
      3042371.35     13845494.69      3041605.46     13845629.85
      3041380.34     13845824.12      3041342.69     13845920.93
      3040763.27     13846723.71
#Sta/Elev= 21
  3886.8    81.6  4136.8    81.1  4176.8    79.2  4445.2   78.82  4526.8    78.7
  4664.6    77.7  4944.6    76.3  4968.9   75.78  4981.7      72  4993.4   67.31
    4994   67.33  4994.5   63.62  4994.7   63.54  4999.7   63.51  5004.2   64.57
  5006.1   67.38  5006.6   67.61    5017   72.56    5025   74.72  5065.8    77.6
  6055.8    81.2
#Mann= 4 , 1 , 0
  3886.8      .1       0  4445.2     .08       0  4968.9     .04       0
    5025      .1       0
Bank Sta=4968.9,5025
XS Rating Curve= 0
Exp/Cntr=.5,.3

Type RM Length L Ch R = 1 ,2906.3  ,88.4,88.4,88.4
BEGIN DESCRIPTION:
Upstream Section of Bridge/Culvert/Weir
END DESCRIPTION:
XS GIS Cut Line= 6
      3042288.49     13845387.18      3041514.79     13845483.59
      3041099.74     13845900.98      3040763.43       13846227.
      3040492.06     13846430.53      3040305.58     13846609.07
#Sta/Elev= 30
  3872.6    83.2  4082.6    81.2  4172.6    81.3  4399.6    79.7  4542.6    78.9
    4654    77.9  4712.8   75.12  4739.7   76.67  4845.3   75.46    4917   76.02
  4968.9   75.74  4981.7   71.96  4993.3   67.27  4993.9   67.29  4994.5   63.58
  4994.7    63.5  4999.7   63.47  5004.2   64.53  5006.1   67.34    5017   72.52
    5025   74.68  5087.4   77.45  5134.8   76.97    5184   76.87  5239.3   77.46
  5293.3   77.29  5316.7    77.6  5376.7    79.2  5616.7    79.6  6306.7    80.1
#Mann= 4 , 1 , 0
  3872.6      .1       0  4399.6     .08       0  4968.9     .04       0
    5025      .1       0
#XS Ineff= 2 , 0
       0    4957    77.4    5033       0   77.15
Permanent Ineff=
       F       F
Bank Sta=4968.9,5025
XS Rating Curve= 0
Exp/Cntr=.5,.3

Type RM Length L Ch R = 3 ,2862.1  ,,,
BEGIN DESCRIPTION:
MEMORIAL DRIVE
Structure ID: W67-5
END DESCRIPTION:
Bridge Culvert--1,0,-1,-1, 0
Deck Dist Width WeirC Skew NumUp NumDn MinLoCord MaxHiCord MaxSubmerge Is_Ogee
10,68.4,2.6,0, 58, 58, , , .95, 0, 1,1,,
  3872.6  4082.6  4172.6  4399.6  4442.6  4542.6  4622.7    4654  4712.8  4739.7
  4740.1  4789.9  4790.1  4845.3  4845.9  4905.7    4917 4967.21  4967.3 4967.39
  4967.5 4967.61  4968.3  4968.9  4981.7  4993.3  4993.4  4993.9  4994.5  4994.7
  4999.7  5004.2  5006.1  5006.5  5006.6    5017 5022.69  5022.8  5023.8 5024.29
  5024.4 5024.51    5025  5078.8  5087.4  5119.4  5134.8  5170.1    5184  5238.4
  5239.3  5293.3  5316.7  5376.7  5400.9  5547.5  5616.7  6306.7
    83.2    81.2    81.3    79.7    79.4    78.9    78.9   78.79   78.59    78.5
    78.5   77.96   77.96   77.65   77.65   77.38    77.4    77.5    77.5    77.5
    77.5    77.5    77.5    77.5   77.47   77.44   77.44   77.44   77.44   77.44
   77.43   77.42   77.41   77.41   77.41   77.39   77.37   77.37   77.37   77.36
   77.36   77.36   77.36   77.17   77.46   77.14   77.08    77.2   77.25   77.46
   77.47   77.72   77.85   79.21   79.25   79.49    79.6    80.1
    83.2    81.2    81.3    79.7    79.4    78.9   78.18    77.9   75.12   76.67
   76.67   76.26   76.26   75.46   75.46   75.93   76.02   75.75   75.75   75.75
   75.75   75.75   75.74   75.74   75.57   75.54   75.54   75.54   75.54   75.54
   75.53   75.52   75.51   75.51   75.51   75.49   75.47   74.09   74.36   74.49
   74.52   74.55   74.68   77.07   77.45   77.13   76.97    76.9   76.87   77.45
   77.46   77.29    77.6    79.2   79.24   79.48    79.6    80.1
  3872.6  4082.6  4172.6  4399.6  4442.6  4542.6  4622.7    4654  4712.8  4739.7
  4740.1  4789.9  4790.1  4845.3  4845.9  4905.7    4917 4967.21  4967.3 4967.39
  4967.5 4967.61  4968.3  4968.9  4981.7  4993.3  4993.4  4993.9  4994.5  4994.7
  4999.7  5004.2  5006.1  5006.5  5006.6    5017 5022.69  5022.8  5023.8 5024.29
  5024.4 5024.51    5025  5078.8  5087.4  5119.4  5134.8  5170.1    5184  5238.4
  5239.3  5293.3  5316.7  5376.7  5400.9  5547.5  5616.7  6306.7
    83.2    81.2    81.3    79.7    79.4    78.9    78.9   78.79   78.59    78.5
    78.5   77.96   77.96   77.65   77.65   77.38    77.4    77.5    77.5    77.5
    77.5    77.5    77.5    77.5   77.47   77.44   77.44   77.44   77.44   77.44
   77.43   77.42   77.41   77.41   77.41   77.39   77.37   77.37   77.37   77.36
   77.36   77.36   77.36   77.17   77.46   77.14   77.08    77.2   77.25   77.46
   77.47   77.72   77.85   79.21   79.25   79.49    79.6    80.1
   83.18   81.18   81.28   79.68   79.38   78.88   78.16   77.88    75.1   76.65
   76.65   76.24   76.24   75.44   75.44   75.91      76   75.73   75.73   75.73
   75.73   75.73   75.72   75.72   75.55   75.52   75.52   75.52   75.52   75.52
   75.51    75.5   75.49   75.49   75.49   75.47   75.45   74.07   74.34   74.47
    74.5   74.53   74.66   77.05   77.43   77.11   76.95   76.88   76.85   77.43
   77.44   77.27   77.58   79.18   79.22   79.46   79.58   80.08
Pier Skew, UpSta & Num, DnSta & Num=  ,4994.7, 2 ,4994.7, 2 , 0 , 0 , 0 ,,
     1.4     1.4
    62.5   76.54
     1.4     1.4
   62.48   76.52
Abutment Skew #Up #Dn= , 2 , 2
  4967.1  4993.4
   75.75   67.27
  4967.1  4993.4
   75.73   67.25
Abutment Skew #Up #Dn= , 2 , 2
  5006.6 5022.89
   67.57   75.47
  5006.6 5022.89
   67.55   75.45
BR Coef= 1 , 1 , 0 ,1.25, 0 ,,,.8,-1,2,0,
WSPro=,,,, 1 ,,,, 0 ,,,, 0 ,,,,-1 ,-1 ,-1 , 0 , 0 , 0 , 0 , 0
BR U #Sta/Elev= 58
  3872.6    83.2  4082.6    81.2  4172.6    81.3  4399.6    79.7  4442.6    79.4
  4542.6    78.9  4622.7   78.18    4654    77.9  4712.8   75.12  4739.7   76.67
  4740.1   76.67  4789.9   76.26  4790.1   76.26  4845.3   75.46  4845.9   75.46
  4905.7   75.93    4917   76.02 4967.21   75.75  4967.3   75.75 4967.39   75.75
  4967.5   75.75 4967.61   75.75  4968.3   75.74  4968.9   75.74  4981.7   71.96
  4993.3   67.27  4993.4   67.27  4993.9   67.29  4994.5   63.58  4994.7    63.5
  4999.7   63.47  5004.2   64.53  5006.1   67.34  5006.5   67.52  5006.6   67.57
    5017   72.52 5022.69   74.06  5022.8   74.09  5023.8   74.36 5024.29   74.49
  5024.4   74.52 5024.51   74.55    5025   74.68  5078.8   77.07  5087.4   77.45
  5119.4   77.13  5134.8   76.97  5170.1    76.9    5184   76.87  5238.4   77.45
  5239.3   77.46  5293.3   77.29  5316.7    77.6  5376.7    79.2  5400.9   79.24
  5547.5   79.48  5616.7    79.6  6306.7    80.1
BR U #Mann= 4
  3872.6      .1  4399.6     .08  4968.9     .04    5025      .1
BR U Banks=4968.9,5025
BR D #Sta/Elev= 58
  3872.6   83.18  4082.6   81.18  4172.6   81.28  4399.6   79.68  4442.6   79.38
  4542.6   78.88  4622.7   78.16    4654   77.88  4712.8    75.1  4739.7   76.65
  4740.1   76.65  4789.9   76.24  4790.1   76.24  4845.3   75.44  4845.9   75.44
  4905.7   75.91    4917      76 4967.21   75.73  4967.3   75.73 4967.39   75.73
  4967.5   75.73 4967.61   75.73  4968.3   75.72  4968.9   75.72  4981.7   71.94
  4993.3   67.25  4993.4   67.25  4993.9   67.27  4994.5   63.56  4994.7   63.48
  4999.7   63.45  5004.2   64.51  5006.1   67.32  5006.5    67.5  5006.6   67.55
    5017    72.5 5022.69   74.04  5022.8   74.07  5023.8   74.34 5024.29   74.47
  5024.4    74.5 5024.51   74.53    5025   74.66  5078.8   77.05  5087.4   77.43
  5119.4   77.11  5134.8   76.95  5170.1   76.88    5184   76.85  5238.4   77.43
  5239.3   77.44  5293.3   77.27  5316.7   77.58  5376.7   79.18  5400.9   79.22
  5547.5   79.46  5616.7   79.58  6306.7   80.08
BR D #Mann= 4
  3872.6      .1  4399.6     .08  4968.9     .04    5025      .1
BR D Banks=4968.9,5025
BC Design=,, 0 ,, 0 ,,,,,,
BC HTab HWMax=83.2

Type RM Length L Ch R = 1 ,2817.9  ,18.6,18.6,18.6
BEGIN DESCRIPTION:
Downstream Section of Bridge/Culvert/Weir
END DESCRIPTION:
XS GIS Cut Line= 6
      3042223.53     13845327.22      3041449.83     13845423.63
      3041034.78     13845841.02      3040698.47     13846167.04
       3040427.1     13846370.57      3040240.62     13846549.11
#Sta/Elev= 30
  3872.6   83.22  4082.6   81.22  4172.6   81.32  4399.6   79.72  4542.6   78.92
    4654   77.92  4712.8   75.14  4739.7   76.69  4845.3   75.48    4917   76.04
  4968.9   75.76  4981.7   71.98  4993.3   67.29  4993.9   67.31  4994.5    63.6
  4994.7   63.52  4999.7   63.49  5004.2   64.55  5006.1   67.36    5017   72.54
    5025    74.7  5087.4   77.47  5134.8   76.99    5184   76.89  5239.3   77.48
  5293.3   77.31  5316.7   77.62  5376.7   79.22  5616.7   79.62  6306.7   80.12
#Mann= 4 , 1 , 0
  3872.6      .1       0  4399.6     .08       0  4968.9     .04       0
    5025      .1       0
#XS Ineff= 2 , 0
       0    4957    77.4    5033       0   77.15
Permanent Ineff=
       F       F
Bank Sta=4968.9,5025
XS Rating Curve= 0
Exp/Cntr=.5,.3

Type RM Length L Ch R = 1 ,2799.3  ,22,22,22
BEGIN DESCRIPTION:
Upstream Section of Bridge/Culvert/Weir
END DESCRIPTION:
XS GIS Cut Line= 4
      3041664.66     13845386.63      3041441.02     13845418.24
      3041198.52     13845644.33      3040761.95      13846079.9
#Sta/Elev= 27
  4442.6   79.36  4542.6   78.86    4654   77.86  4916.6   76.56  4968.9    75.7
    4974   73.31  4985.6   69.74  4992.6   66.58  4992.9   66.56  4993.9   63.58
    5000   63.61  5003.8   63.94  5004.1   67.25  5005.5   67.23  5008.7   69.47
  5013.4   71.89  5031.7   74.64  5065.6   76.87  5076.7   78.26  5106.7   79.36
  5156.7   79.36  5196.7   77.46  5256.7   76.96  5286.7   77.76  5316.7   77.56
  5376.7   79.16  5616.7   79.56
#Mann= 3 , 1 , 0
  4442.6     .08       0  4968.9     .03       0  5031.7      .1       0
#XS Ineff= 2 , 0
       0    4930    76.2    5063       0    76.1
Permanent Ineff=
       F       F
Bank Sta=4968.9,5031.7
XS Rating Curve= 0
Exp/Cntr=.5,.3

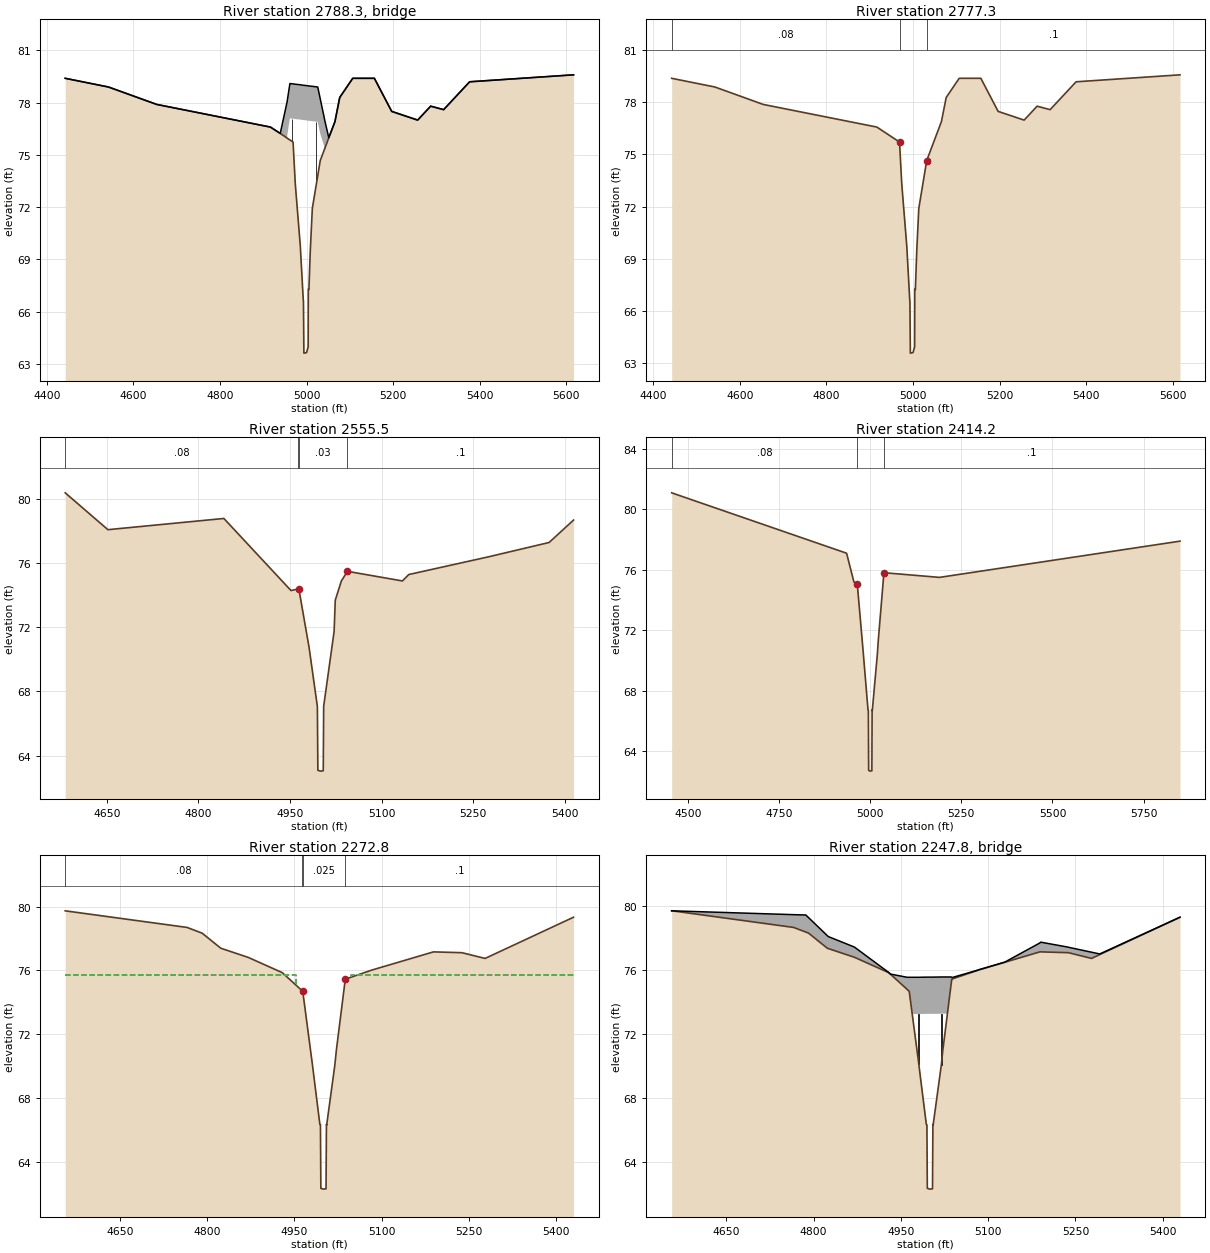
Type RM Length L Ch R = 3 ,2788.3  ,,,
BEGIN DESCRIPTION:
24" PIPELINE
END DESCRIPTION:
Bridge Culvert--1,0,-1,-1, 0
Deck Dist Width WeirC Skew NumUp NumDn MinLoCord MaxHiCord MaxSubmerge Is_Ogee
10,2,2.6,0, 35, 35, , , .95, 0, 1,1,,
  4442.6  4542.6    4654  4916.6  4939.3 4955.21  4955.3  4961.6  4968.9    4974
  4985.6  4992.6  4992.9  4993.9    5000  5003.8  5004.1  5005.5  5008.7  5013.4
  5025.9  5031.7 5042.29  5042.4  5051.4  5065.6  5076.7  5106.7  5156.7  5196.7
  5256.7  5286.7  5316.7  5376.7  5616.7
    79.4    78.9    77.9    76.6   76.24   78.06   78.08    79.1   79.08   79.06
   79.03      79      79      79   78.98   78.97   78.97   78.96   78.95   78.94
    78.9   78.22   76.97   76.95   75.99   76.91    78.3    79.4    79.4    77.5
      77    77.8    77.6    79.2    79.6
    79.4    78.9    77.9    76.6   76.23   75.97   76.08    77.1   77.08   77.06
   77.03      77      77      77   76.98   76.97   76.97   76.96   76.95   76.94
    76.9   76.22   75.38   75.38   75.98   76.91    78.3    79.4    79.4    77.5
      77    77.8    77.6    79.2    79.6
  4442.6  4542.6    4654  4916.6  4939.3 4955.21  4955.3  4961.6  4968.9    4974
  4985.6  4992.6  4992.9  4993.9    5000  5003.8  5004.1  5005.5  5008.7  5013.4
  5025.9  5031.7 5042.29  5042.4  5051.4  5065.6  5076.7  5106.7  5156.7  5196.7
  5256.7  5286.7  5316.7  5376.7  5616.7
    79.4    78.9    77.9    76.6   76.24   78.06   78.08    79.1   79.08   79.06
   79.03      79      79      79   78.98   78.97   78.97   78.96   78.95   78.94
    78.9   78.22   76.97   76.95   75.99   76.91    78.3    79.4    79.4    77.5
      77    77.8    77.6    79.2    79.6
    79.4    78.9    77.9    76.6   76.23   75.97   76.08    77.1   77.08   77.06
   77.03      77      77      77   76.98   76.97   76.97   76.96   76.95   76.94
    76.9   76.22   75.38   75.38   75.98   76.91    78.3    79.4    79.4    77.5
      77    77.8    77.6    79.2    79.6
Pier Skew, UpSta & Num, DnSta & Num=  ,4966.4, 2 ,4966.4, 2 , 0 , 0 , 0 ,,
     1.4     1.4
   74.77   78.09
     1.4     1.4
   74.77   78.09
Pier Skew, UpSta & Num, DnSta & Num=  ,5022.2, 2 ,5022.2, 2 , 0 , 0 , 0 ,,
     1.4     1.4
   72.15   77.91
     1.4     1.4
   72.15   77.91
BR Coef= 1 , 1 , 0 ,1.25, 0 ,,,.8,0,2,0,
WSPro=,,,, 1 ,,,, 0 ,,,, 0 ,,,,-1 ,-1 ,-1 , 0 , 0 , 0 , 0 , 0
BR U #Sta/Elev= 35
  4442.6    79.4  4542.6    78.9    4654    77.9  4916.6    76.6  4939.3   76.23
 4955.21   75.97  4955.3   75.96  4961.6   75.86  4968.9   75.74    4974   73.35
  4985.6   69.78  4992.6   66.62  4992.9    66.6  4993.9   63.62    5000   63.65
  5003.8   63.98  5004.1   67.29  5005.5   67.27  5008.7   69.51  5013.4   71.93
  5025.9   73.81  5031.7   74.68 5042.29   75.38  5042.4   75.38  5051.4   75.98
  5065.6   76.91  5076.7    78.3  5106.7    79.4  5156.7    79.4  5196.7    77.5
  5256.7      77  5286.7    77.8  5316.7    77.6  5376.7    79.2  5616.7    79.6
BR U #Mann= 3
  4442.6     .08  4968.9     .03  5031.7      .1
BR U Banks=4968.9,5031.7
BR D #Sta/Elev= 35
  4442.6    79.4  4542.6    78.9    4654    77.9  4916.6    76.6  4939.3   76.23
 4955.21   75.97  4955.3   75.96  4961.6   75.86  4968.9   75.74    4974   73.35
  4985.6   69.78  4992.6   66.62  4992.9    66.6  4993.9   63.62    5000   63.65
  5003.8   63.98  5004.1   67.29  5005.5   67.27  5008.7   69.51  5013.4   71.93
  5025.9   73.81  5031.7   74.68 5042.29   75.38  5042.4   75.38  5051.4   75.98
  5065.6   76.91  5076.7    78.3  5106.7    79.4  5156.7    79.4  5196.7    77.5
  5256.7      77  5286.7    77.8  5316.7    77.6  5376.7    79.2  5616.7    79.6
BR D #Mann= 3
  4442.6     .08  4968.9     .03  5031.7      .1
BR D Banks=4968.9,5031.7
BC Design=,, 0 ,, 0 ,,,,,,
BC HTab HWMax=79.56

Type RM Length L Ch R = 1 ,2777.3  ,221.8,221.8,221.8
BEGIN DESCRIPTION:
Downstream Section of Bridge/Culvert/Weir
END DESCRIPTION:
XS GIS Cut Line= 4
      3041662.59     13845364.73      3041438.96     13845396.34
      3041196.46     13845622.43      3040759.88       13846058.
#Sta/Elev= 27
  4442.6   79.37  4542.6   78.87    4654   77.87  4916.6   76.57  4968.9   75.71
    4974   73.32  4985.6   69.75  4992.6   66.59  4992.9   66.57  4993.9   63.59
    5000   63.62  5003.8   63.95  5004.1   67.26  5005.5   67.24  5008.7   69.48
  5013.4    71.9  5031.7   74.65  5065.6   76.88  5076.7   78.27  5106.7   79.37
  5156.7   79.37  5196.7   77.47  5256.7   76.97  5286.7   77.77  5316.7   77.57
  5376.7   79.17  5616.7   79.57
#Mann= 3 , 1 , 0
  4442.6     .08       0  4968.9     .03       0  5031.7      .1       0
#XS Ineff= 2 , 0
       0    4930    76.2    5063       0    76.1
Permanent Ineff=
       F       F
Bank Sta=4968.9,5031.7
XS Rating Curve= 0
Exp/Cntr=.5,.3

Type RM Length L Ch R = 1 ,2555.5  ,140.3,141.3,157.4
BEGIN DESCRIPTION:
Cross Section 2555.5-INTERPOLATED
END DESCRIPTION:
XS GIS Cut Line= 4
      3041589.97     13845331.36      3041183.38     13845400.72
      3041045.18     13845459.94      3040872.27     13845667.41
#Sta/Elev= 21
  4581.6    80.4  4651.6    78.1  4841.6    78.8  4951.6    74.3  4963.5    74.4
  4964.4   74.41  4981.2   70.75  4994.8   67.06  4995.6   63.08    5000   63.03
  5004.4   63.05  5005.1   67.08  5022.2   71.74  5024.1    73.7  5034.1    74.9
  5044.1    75.5  5134.1    74.9  5144.5    75.3  5274.5    76.4  5374.5    77.3
  5414.5    78.7
#Mann= 4 , 1 , 0
  4581.6     .08       0  4963.5      .1       0  4964.4     .03       0
  5044.1      .1       0
Bank Sta=4964.4,5044.1
XS Rating Curve= 0
Exp/Cntr=.3,.1

Type RM Length L Ch R = 1 ,2414.2  ,144.6,141.4,138.3
BEGIN DESCRIPTION:
Cross Section 2414.2-INTERPOLATED
END DESCRIPTION:
XS GIS Cut Line= 5
      3041682.49     13845208.86       3041166.9     13845260.68
      3041107.05     13845274.85      3040963.01     13845332.37
      3040559.69     13845854.81
#Sta/Elev= 18
  4455.1    81.1  4935.1    77.1  4955.1    75.2  4964.4   75.05  4980.8   70.52
  4981.2   70.39  4993.9   66.72  4994.8    66.7  4995.6   62.72    5000   62.67
  5004.4   62.69  5005.1   66.72  5005.6   66.68  5019.5   70.42  5022.2   71.38
  5037.5   75.81  5189.9    75.5  5849.9    77.9
#Mann= 3 , 1 , 0
  4455.1     .08       0  4964.4    .025       0  5037.5      .1       0
Bank Sta=4964.4,5037.5
XS Rating Curve= 0
Exp/Cntr=.5,.3

Type RM Length L Ch R = 1 ,2272.8  ,50,50,50
BEGIN DESCRIPTION:
Upstream Section of Bridge/Culvert/Weir
END DESCRIPTION:
XS GIS Cut Line= 5
      3041542.19     13845099.97      3041191.38       13845111.
      3041110.18     13845130.48      3040924.11      13845200.6
      3040774.28     13845388.55
#Sta/Elev= 24
  4556.1   79.73  4765.6   78.69  4791.5   78.33  4823.5   77.39    4871   76.81
  4929.2   75.86  4963.9   74.71  4964.4   74.69  4980.8   70.16  4993.8   66.36
  4994.8   66.34  4995.5   62.36    5000   62.31  5004.4   62.33  5005.1   66.36
  5005.5   66.32  5019.5   70.06  5022.2   71.02  5037.5   75.45    5083   76.02
    5189   77.16  5237.9   77.11  5277.8   76.75  5429.8   79.33
#Mann= 4 , 1 , 0
  4556.1     .08       0  4963.9      .1       0  4964.4    .025       0
  5037.5      .1       0
#XS Ineff= 2 , 0
       0    4953    75.7    5048       0    75.7
Permanent Ineff=
       F       F
Bank Sta=4964.4,5037.5
XS Rating Curve= 0
Exp/Cntr=.5,.3

Type RM Length L Ch R = 3 ,2247.8  ,,,
BEGIN DESCRIPTION:
ACCESS ROAD FOR DAY COMMERCIAL
Structure ID: W67-4
END DESCRIPTION:
Bridge Culvert--1,0,-1,-1, 0
Deck Dist Width WeirC Skew NumUp NumDn MinLoCord MaxHiCord MaxSubmerge Is_Ogee
10,30,2.6,0, 49, 49, , , .95, 0, 1,1,,
  4556.1  4557.1  4765.6  4786.7  4791.5  4823.5  4825.2  4870.3    4871  4929.2
  4932.2 4960.89    4961 4961.11  4963.5  4963.9  4964.4 4969.61  4969.7  4980.8
  4981.2  4993.8  4993.9  4994.8  4995.5    5000  5004.4  5005.1  5005.5  5019.5
  5022.2  5025.7 5029.89    5030  5036.4  5037.5 5038.59  5038.7 5038.81  5082.5
    5083  5128.7    5189  5190.2  5237.1  5237.9  5277.8  5291.8  5429.8
    79.7    79.7   79.46   79.44   79.27   78.15   78.09   77.43   77.41   75.84
   75.74   75.54   75.54   75.54   75.54   75.54   75.54   75.54   75.54   75.54
   75.54   75.55   75.55   75.55   75.55   75.55   75.55   75.55   75.55   75.56
   75.56   75.56   75.56   75.56   75.56   75.54   75.53   75.53   75.53   75.99
      76   76.49   77.69   77.74   77.43   77.42   77.11      77    79.3
    79.7    79.7   78.66   78.37    78.3   77.36   77.34   76.79   76.78   75.83
   75.73   74.78   74.77   74.77   74.69   74.68   74.66   73.22   73.24   73.24
   73.24   73.25   73.25   73.25   73.25   73.25   73.25   73.25   73.25   73.26
   73.26   73.26   73.26   73.25    75.1   75.42   75.43   75.44   75.44   75.98
   75.99   76.48   77.13   77.13   77.08   77.08   76.72   76.96    79.3
  4556.1  4557.1  4765.6  4786.7  4791.5  4823.5  4825.2  4870.3    4871  4929.2
  4932.2 4960.89    4961 4961.11  4963.5  4963.9  4964.4 4969.61  4969.7  4980.8
  4981.2  4993.8  4993.9  4994.8  4995.5    5000  5004.4  5005.1  5005.5  5019.5
  5022.2  5025.7 5029.89    5030  5036.4  5037.5 5038.59  5038.7 5038.81  5082.5
    5083  5128.7    5189  5190.2  5237.1  5237.9  5277.8  5291.8  5429.8
    79.7    79.7   79.46   79.44   79.27   78.15   78.09   77.43   77.41   75.84
   75.74   75.54   75.54   75.54   75.54   75.54   75.54   75.54   75.54   75.54
   75.54   75.55   75.55   75.55   75.55   75.55   75.55   75.55   75.55   75.56
   75.56   75.56   75.56   75.56   75.56   75.54   75.53   75.53   75.53   75.99
      76   76.49   77.69   77.74   77.43   77.42   77.11      77    79.3
   79.67   79.67   78.63   78.34   78.27   77.33   77.31   76.76   76.75    75.8
    75.7   74.75   74.74   74.74   74.66   74.65   74.63   73.19   73.21   73.21
   73.21   73.22   73.22   73.22   73.22   73.22   73.22   73.22   73.22   73.23
   73.23   73.23   73.23   73.22   75.07   75.39    75.4   75.41   75.41   75.95
   75.96   76.45    77.1    77.1   77.05   77.05   76.69   76.93   79.27
Pier Skew, UpSta & Num, DnSta & Num=  ,4980.8, 2 ,4980.8, 2 , 0 , 0 , 0 ,,
     1.4     1.4
   68.91   74.24
     1.4     1.4
   68.88   74.21
Pier Skew, UpSta & Num, DnSta & Num=  ,5019.5, 2 ,5019.5, 2 , 0 , 0 , 0 ,,
     1.4     1.4
   68.84   74.26
     1.4     1.4
   68.81   74.23
Abutment Skew #Up #Dn= , 2 , 2
  4969.5  4993.9
   73.24   66.33
  4969.5  4993.9
   73.21    66.3
Abutment Skew #Up #Dn= , 2 , 2
  5025.7 5030.09
      72   73.26
  5025.7 5030.09
   71.97   73.23
BR Coef= 1 , 1 , 0 ,1.25, 0 ,,,.8,0,2,0,
WSPro=,,,, 1 ,,,, 0 ,,,, 0 ,,,,-1 ,-1 ,-1 , 0 , 0 , 0 , 0 , 0
BR U #Sta/Elev= 49
  4556.1    79.7  4557.1    79.7  4765.6   78.66  4786.7   78.37  4791.5    78.3
  4823.5   77.36  4825.2   77.34  4870.3   76.79    4871   76.78  4929.2   75.83
  4932.2   75.73 4960.89   74.78    4961   74.77 4961.11   74.77  4963.5   74.69
  4963.9   74.68  4964.4   74.66 4969.61   73.22  4969.7    73.2  4980.8   70.13
  4981.2      70  4993.8   66.33  4993.9   66.33  4994.8   66.31  4995.5   62.33
    5000   62.28  5004.4    62.3  5005.1   66.33  5005.5   66.29  5019.5   70.03
  5022.2   70.99  5025.7      72 5029.89   73.22    5030   73.25  5036.4    75.1
  5037.5   75.42 5038.59   75.43  5038.7   75.44 5038.81   75.44  5082.5   75.98
    5083   75.99  5128.7   76.48    5189   77.13  5190.2   77.13  5237.1   77.08
  5237.9   77.08  5277.8   76.72  5291.8   76.96  5429.8    79.3
BR U #Mann= 4
  4556.1     .08  4963.9      .1  4964.4    .025  5037.5      .1
BR U Banks=4964.4,5037.5
BR D #Sta/Elev= 49
  4556.1   79.67  4557.1   79.67  4765.6   78.63  4786.7   78.34  4791.5   78.27
  4823.5   77.33  4825.2   77.31  4870.3   76.76    4871   76.75  4929.2    75.8
  4932.2    75.7 4960.89   74.75    4961   74.74 4961.11   74.74  4963.5   74.66
  4963.9   74.65  4964.4   74.63 4969.61   73.19  4969.7   73.17  4980.8    70.1
  4981.2   69.97  4993.8    66.3  4993.9    66.3  4994.8   66.28  4995.5    62.3
    5000   62.25  5004.4   62.27  5005.1    66.3  5005.5   66.26  5019.5      70
  5022.2   70.96  5025.7   71.97 5029.89   73.19    5030   73.22  5036.4   75.07
  5037.5   75.39 5038.59    75.4  5038.7   75.41 5038.81   75.41  5082.5   75.95
    5083   75.96  5128.7   76.45    5189    77.1  5190.2    77.1  5237.1   77.05
  5237.9   77.05  5277.8   76.69  5291.8   76.93  5429.8   79.27
BR D #Mann= 4
  4556.1     .08  4963.9      .1  4964.4    .025  5037.5      .1
BR D Banks=4964.4,5037.5
BC Design=,, 0 ,, 0 ,,,,,,
BC HTab HWMax=79.73

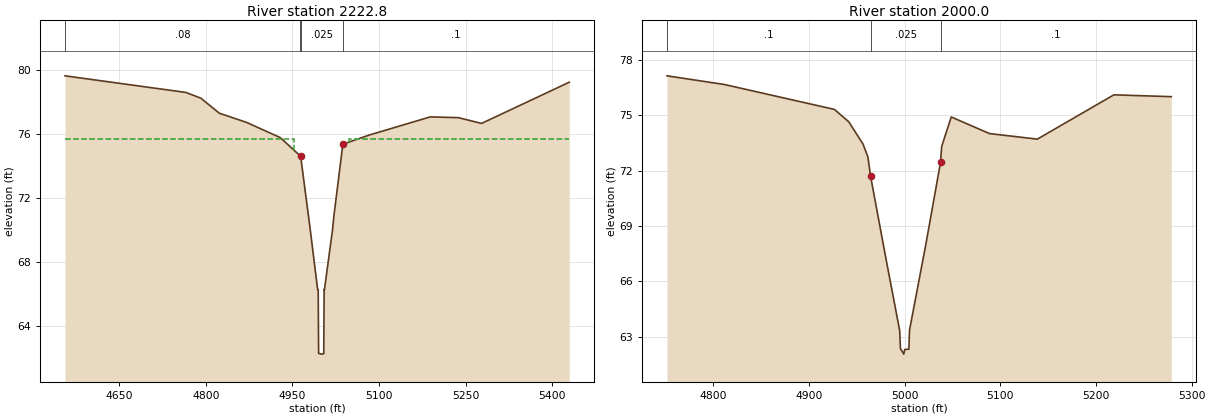
Type RM Length L Ch R = 1 ,2222.8  ,222.8,222.8,222.8
BEGIN DESCRIPTION:
Downstream Section of Bridge/Culvert/Weir
END DESCRIPTION:
XS GIS Cut Line= 5
      3041521.31     13845054.53       3041170.5     13845065.56
       3041089.3     13845085.04      3040903.23     13845155.16
       3040753.4     13845343.12
#Sta/Elev= 24
  4556.1   79.66  4765.6   78.62  4791.5   78.26  4823.5   77.32    4871   76.74
  4929.2   75.79  4963.9   74.64  4964.4   74.62  4980.8   70.09  4993.8   66.29
  4994.8   66.27  4995.5   62.29    5000   62.24  5004.4   62.26  5005.1   66.29
  5005.5   66.25  5019.5   69.99  5022.2   70.95  5037.5   75.38    5083   75.95
    5189   77.09  5237.9   77.04  5277.8   76.68  5429.8   79.26
#Mann= 4 , 1 , 0
  4556.1     .08       0  4963.9      .1       0  4964.4    .025       0
  5037.5      .1       0
#XS Ineff= 2 , 0
       0    4953    75.7    5048       0    75.7
Permanent Ineff=
       F       F
Bank Sta=4964.4,5037.5
XS Rating Curve= 0
Exp/Cntr=.5,.3

Type RM Length L Ch R = 1 ,2000.0  ,0,0,0
BEGIN DESCRIPTION:
Cross Section 2000.0-INTERPOLATED
END DESCRIPTION:
XS GIS Cut Line= 3
      3041258.95     13844858.95      3041022.03     13844867.36
      3040791.74     13845043.67
#Sta/Elev= 22
  4751.6   77.13  4811.6   76.66  4926.6   75.31  4941.6   74.64  4956.6   73.42
  4961.6   72.73  4964.4   71.68  4981.2   67.02  4994.8   63.33  4995.6   62.35
  4999.1   62.05    5000    62.3  5004.4   62.32  5005.1   63.35  5022.2   68.01
  5037.5   72.44  5038.7    73.3  5048.7    74.9  5088.7      74  5138.7    73.7
  5218.7    76.1  5278.7      76
#Mann= 3 , 1 , 0
  4751.6      .1       0  4964.4    .025       0  5037.5      .1       0
Bank Sta=4964.4,5037.5
XS Rating Curve= 0
Exp/Cntr=.3,.1

Chan Stop Cuts=-1